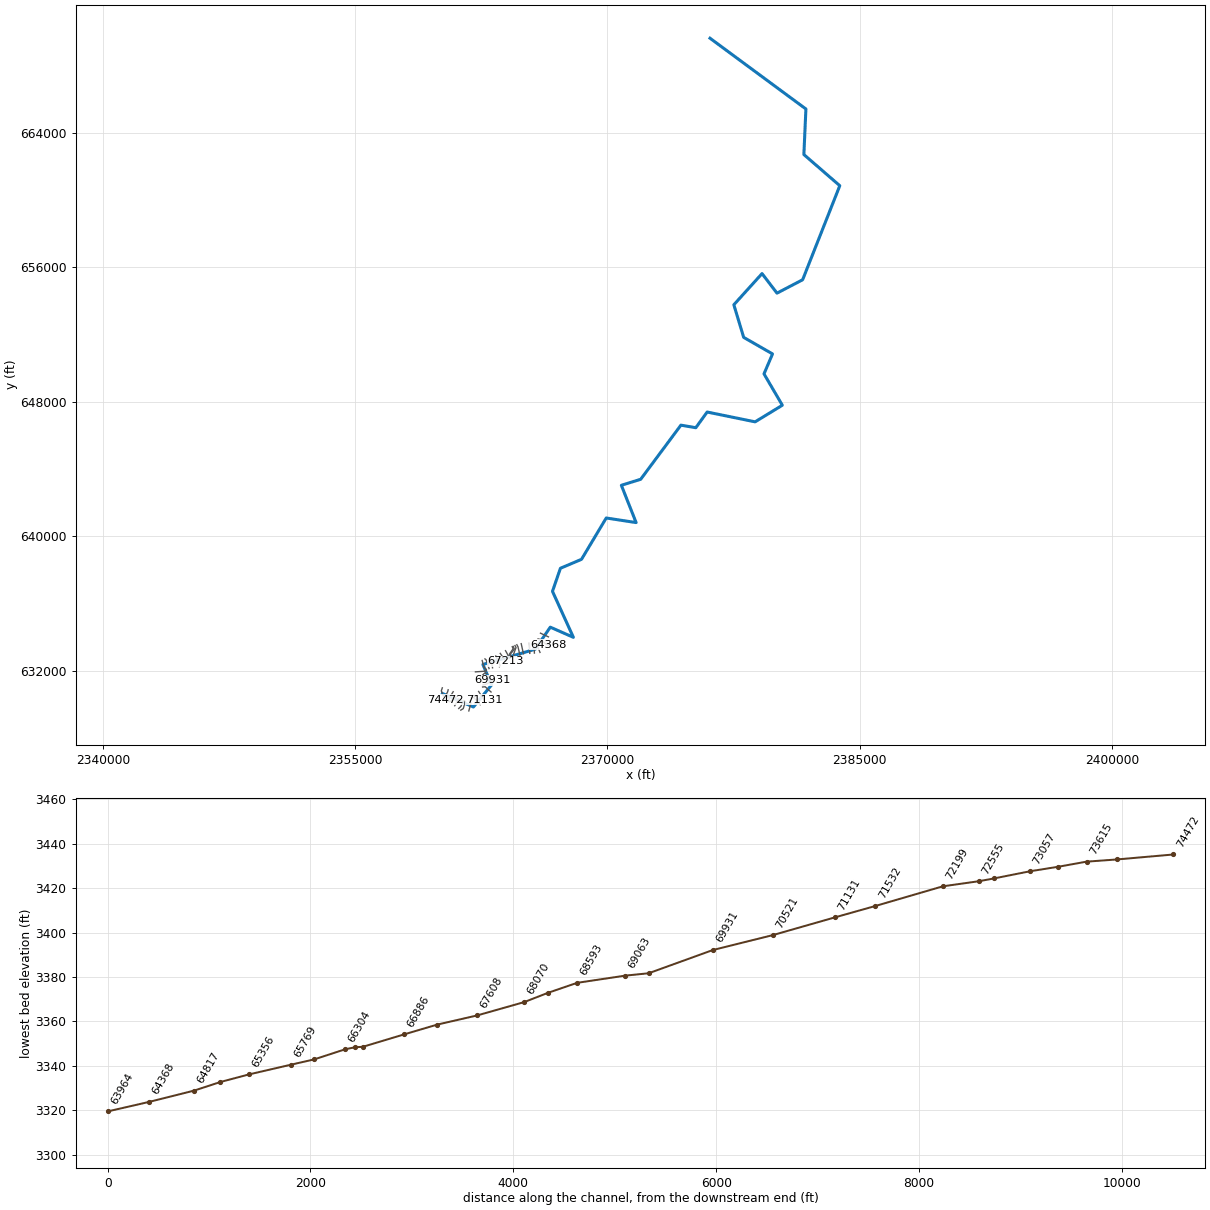
--- GNDYCK_1.prj (project) ---

Proj Title=GNDYCK_1
Current Plan=p01
Default Exp/Contr=0,0
English Units
Geom File=g01
Flow File=f01
Plan File=p01
Background Map Layer=Inundation Boundary (P100yr Value_0)
BEGIN DESCRIPTION:
----------MODEL BY WOOD PLC 2022----------
AFH study
Randolph County, WV
HEC-RAS Version: RAS 6.2
Vertical Datum: NAVD88
Projection: NAD 1983 StatePlane West Virginia S FIPS 4702 (US Feet)
Terrain: 1-meter LIDAR (FEMA Region III 3DEP collected 2016-2018)
Land Use: 2019 NLCD
Hydrologic Method:
WV SIR2010-5033 regression equations
Additional Model Notes:
KWSEL tie-in with DRKFK_2 due to main stem name change
END DESCRIPTION:
DSS Export Rating Curves= 0
DSS Export Rating Curve Sorted= 0
DSS Export Volume Flow Curves= 0
DXF OffsetX= 0
DXF OffsetY= 0
DXF ScaleX= 0
DXF ScaleY= 0

--- GNDYCK_1.p01 (plan) ---

Plan Title=Floodplain
Program Version=6.20
Short Identifier=Floodplain
Geom File=g01
Flow File=f01
Subcritical Flow
K Sum by GR= 0
Std Step Tol= 0.01
Critical Tol= 0.01
Num of Std Step Trials= 20
Max Error Tol= 0.3
Flow Tol Ratio= 0.001
Split Flow NTrial= 30
Split Flow Tol= 0.02
Split Flow Ratio= 0.02
Log Output Level= 0
Friction Slope Method= 1
Unsteady Friction Slope Method= 2
Unsteady Bridges Friction Slope Method= 1
Parabolic Critical Depth
Global Vel Dist= 0 , 0 , 0
Global Log Level= 0
CheckData=True
Encroach Param=-1 ,0,0, 0
Mapping Interval=1HOUR
Computation Time Step Use Courant=        0
Computation Time Step Use Time Series=    0
Computation Time Step Count To Double=0
Computation Time Step Max Doubling=0
Computation Time Step Max Halving=0
Computation Time Step Residence Courant=0
Run HTab= 0
Run UNet= 0
Run Sediment= 0
Run PostProcess= 0
Run WQNet= 0
Run RASMapper=-1
UNET Theta= 0
UNET Theta Warmup= 0
UNET ZTol= 0
UNET ZSATol= 0
UNET MxIter= 0
UNET Max Iter WO Improvement= 0
UNET MaxInSteps= 0
UNET DtIC= 0
UNET DtMin= 0
UNET MaxCRTS= 0
UNET WFStab= 0
UNET SFStab= 0
UNET WFX= 1
UNET SFX= 1
UNET Gravity=32.174
UNET 1D Methodology=Finite Difference
UNET DSS MLevel= 1
UNET Pardiso=0
UNET DZMax Abort= 0
UNET Use Existing IB Tables= 0
UNET Froude Reduction=False
UNET Froude Limit= 0
UNET Froude Power= 0
UNET D1 Cores= 0
UNET WindReference=Eulerian
UNET WindDragFormulation=Hsu (1988)
UNET D2 Coriolis=0
UNET D2 Cores= 0
UNET D2 Theta= 1
UNET D2 Theta Warmup= 1
UNET D2 Z Tol= 0.01
UNET D2 Volume Tol= 0.01
UNET D2 Max Iterations= 20
UNET D2 Equation= 0
UNET D2 RampUpFraction=0.1
UNET D2 TimeSlices= 1
UNET D2 Turbulence Formulation=Non-Conservative (original)
UNET D2 Eddy Viscosity=0.3
UNET D2 Transverse Eddy Viscosity=0.1
UNET D2 Smagorinsky Mixing=0
UNET D2 BCVolumeCheck=0
UNET D2 Cores=0
UNET D2 SolverType=PARDISO (Direct)
UNET D2 Minimum Iterations= 2147483647
UNET D2 Maximum Iterations= 2147483647
UNET D2 Restart Number= 10
UNET D2 Relaxation Coeff=1.3
UNET D2 SOR Precondition Iterations= 10
UNET D2 ILUT Maximum Fill= 8
UNET D2 ILUT Tolerance=1E-08
UNET D1D2 MaxIter= 0
UNET D1D2 ZTol=0.01
UNET D1D2 QTol=0.1
UNET D1D2 MinQTol=1
Write IC File= 0
Write IC File at Fixed DateTime=0
Write IC File at Sim End=0
Echo Input=False
Echo Parameters=False
Echo Output=False
Write Detailed= 0
HDF Write Warmup=0
HDF Write Time Slices=0
HDF Flush=0
HDF Compression= 1
HDF Chunk Size= 1
HDF Spatial Parts= 1
HDF Use Max Rows=0
HDF Fixed Rows= 1
Calibration Method= 0
Calibration Iterations= 20
Calibration Max Change=0.05
Calibration Tolerance=0.2
Calibration Maximum=1.5
Calibration Minimum=0.5
Calibration Optimization Method= 1
WQ AD Non Conservative
WQ ULTIMATE=-1
WQ Max Comp Step=1HOUR
WQ Output Interval=15MIN
WQ Output Selected Increments= 0
WQ Output face flow=0
WQ Output face velocity=0
WQ Output face area=0
WQ Output face dispersion=0
WQ Output cell volume=0
WQ Output cell surface area=0
WQ Output cell continuity=0
WQ Output cumulative cell continuity=0
WQ Output face conc=0
WQ Output face dconc_dx=0
WQ Output face courant=0
WQ Output face peclet=0
WQ Output face adv mass=0
WQ Output face disp mass=0
WQ Output cell mass=0
WQ Output cell source sink temp=0
WQ Output nsm pathways=0
WQ Output nsm derived pathways=0
WQ Create Restart=0
WQ Fixed Restart=0
WQ System Summary=0
WQ Write To DSS=0
Sorting and Armoring Iterations= 10
XS Update Threshold= 0.02
Bed Roughness Predictor= 0
Hydraulics Update Threshold= 0.02
Energy Slope Method= 1
Volume Change Method= 1
Sediment Retention Method= 0
Sediment TS Multiplier= 1
Warm Up Method= 0
XS Weighting Method= 0
Number of US Weighted Cross Sections= 1
Number of DS Weighted Cross Sections= 1
Upstream XS Weight=0
Main XS Weight=1
Downstream XS Weight=0
Number of DS XS's Weighted with US Boundary= 1
Upstream Boundary Weight= 1
Weight of XSs Associated with US Boundary= 0
Number of US XS's Weighted with DS Boundary= 1
Downstream Boundary Weight= 0.5
Weight of XSs Associated with DS Boundary= 0.5
Percentile Method= 0
Sediment Output Level= 3
Mass or Volume Output= 0
Output Increment Type= 1
Profile and TS Output Increment= 1
Transport Output Increment 1
XS Output Flag= 0
XS Output Increment= 10
Read HDF5 Sediment Hotstart= 0
Sediment Hotstart Type= 0
Write Gradation File= 0
Read Gradation Hotstart= 0
Write HDF5 File= 1
Write Binary Output= 1
Write DSS Sediment File= 0
DSS Sediment Output Type= 1
SV Curve= 0
Specific Gage Flag= 0
Subcell Erosion Methods= 0
Subcell Deposition Methods= 0
Advection Scheme= 1
Matrix Solver= 0
Implicit Weighting Factor= 1
Maximum Outer Loop Convergence Iterations= 5
Convergence Maximum Absolute= 0.001
Convergence RMSE= 0.0001
Grain Fractions Max Abs Error= 0.001
Max Subgrid Regions= 1
Max Subgrid Length Scale= 3.402823E+38
Initial Layer Thickness= 3.402823E+38
Min Layer Thickness= 3.402823E+38
Max Layer Thickness= 3.402823E+38
Number of Layers= 5

--- GNDYCK_1.f01 (steady flow) ---

Flow Title=Flow
Program Version=6.20
Number of Profiles= 1
Profile Names=P100yr
River Rch & RM=GNDYCK_1,Main            ,74472
    2510
River Rch & RM=GNDYCK_1,Main            ,67608
    2970
River Rch & RM=GNDYCK_1,Main            ,57241
    3760
River Rch & RM=GNDYCK_1,Main            ,49117
    4210
River Rch & RM=GNDYCK_1,Main            ,35055
    4820
River Rch & RM=GNDYCK_1,Main            ,22189
    5370
River Rch & RM=GNDYCK_1,Main            ,13286
    6000
Boundary for River Rch & Prof#=GNDYCK_1,Main            , 1
Up Type= 0
Dn Type= 1
Dn Known WS=2670.97
DSS Import GetInterval= 0
DSS Import GetPeak= 0
DSS Import FillOption= 0

--- GNDYCK_1.g01 (geometry) ---

Geom Title=Geometry
Program Version=6.20

River Reach=GNDYCK_1        ,Main
Reach XY= 30
     2360191.728630655.7870000152362036.99099998629852.342000008
2363119.90195654631171.1625538622362601.40099999 632379.94600001
2365706.67900002633285.7440000182366608.41100003634601.299999997
     2367980.986633996.4450000082366738.09700003636730.665999994
2367210.12955476638103.7010334582368463.82000001638635.932000011
2369934.98999999641094.6570000052371711.49400003 640821.23800002
2370833.50900002643039.7590000182371982.36438644643396.936553761
2374374.76600003646617.5610000042375260.53744628646464.431223139
     2375934.419647398.4210000192378786.49400002646814.276999995
2380405.00546919647802.342856482     2379315.081649666.960000008
     2379821.669650854.2160000212378106.68400002651838.394999996
2377521.24400002653778.3589999972379198.45100002655632.580000013
2380087.10699998654469.2440000182381612.26400003655265.800999999
2383821.26900002660860.6539999992381685.85300003662713.952999994
2381806.41800001 665424.120000022376104.04961093669633.980724558

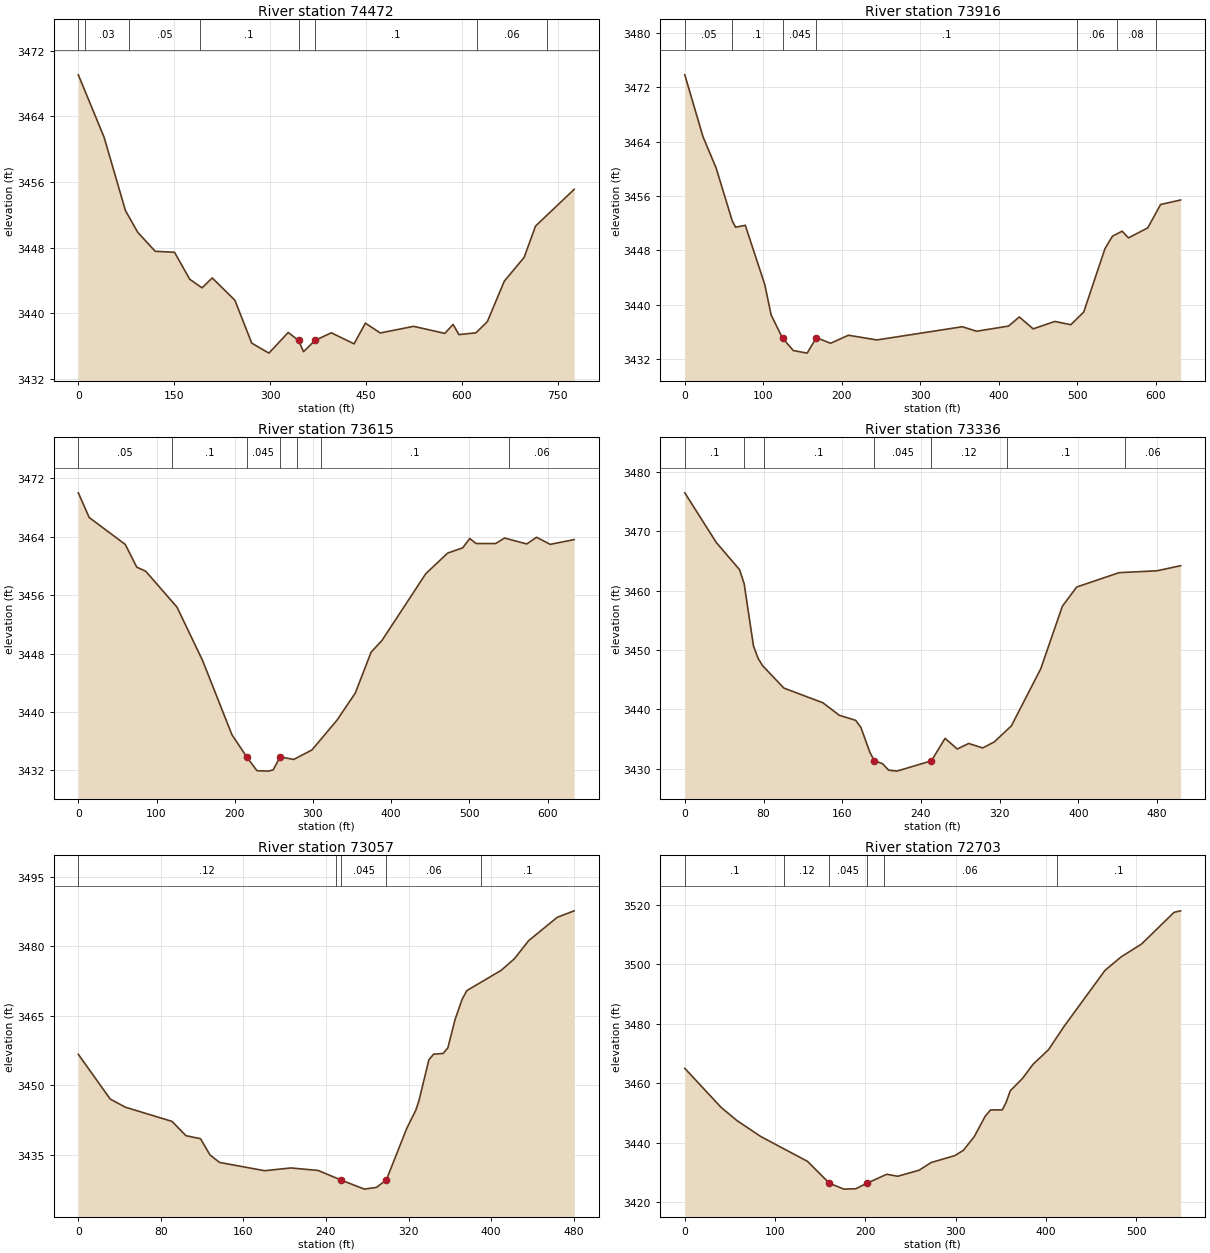
Type RM Length L Ch R = 1 ,74472   ,556,556,556
XS GIS Cut Line= 3
2360186.78904024630991.507112601 2360126.8235474630807.554410706
2360378.08603325630282.724748537
#Sta/Elev= 30
       0 3469.08    40.3 3461.46    73.7 3452.51    92.8 3449.87   120.2 3447.54
   150.4 3447.42   174.3 3444.12   193.5 3443.08   209.4 3444.29   244.9 3441.56
   271.2 3436.33   298.1 3435.11   328.2 3437.63  344.333436.666   352.2 3435.29
   370.2 3436.67   395.7 3437.59   431.2 3436.24   448.9 3438.77   472.2 3437.57
   524.3 3438.38   573.1 3437.52   586.1 3438.61   595.2 3437.37   621.9 3437.59
   639.6 3438.95   666.2  3443.9   697.2  3446.8     715 3450.62   775.4  3455.1
#Mann= 8 ,-1,0
       0     .05       0      10     .03       0      80     .05       0
     190      .1       0  344.33    .045       0   370.2      .1       0
  623.48     .06       0  733.48      .1       0
Bank Sta=344.33,370.2
XS Rating Curve= 0 ,0
Exp/Cntr=0.3,0.1

Type RM Length L Ch R = 1 ,73916   ,300.9,300.9,300.9
XS GIS Cut Line= 4
2360535.82008191630875.7755358162360504.57470696630755.250403999
 2360360.4481107630485.5941916412360400.99630576630288.137369238
#Sta/Elev= 30
       0 3473.81    23.3 3464.67    39.9 3460.12    60.5 3452.32    64.7  3451.4
    77.1 3451.68   101.9 3442.97   110.1 3438.47   124.5 3435.09   138.3 3433.26
   155.9 3432.88   167.7 3435.15   185.8 3434.33   208.5 3435.51   244.8 3434.82
   353.6 3436.76   371.8  3436.1   412.6 3436.86   426.2  3438.2   443.9 3436.45
   471.5 3437.54   491.9 3437.06   508.3 3438.91   535.4 3448.25     545 3450.09
   557.3 3450.81   565.4 3449.83   589.9  3451.3   606.3 3454.74   631.8  3455.4
#Mann= 7 ,-1,0
       0     .05       0      60      .1       0   124.5    .045       0
   167.7      .1       0  500.27     .06       0  550.27     .08       0
  600.27     .06       0
Bank Sta=124.5,167.7
XS Rating Curve= 0 ,0
Exp/Cntr=0.3,0.1

Type RM Length L Ch R = 1 ,73615   ,279.3,279.3,279.3
XS GIS Cut Line= 3
2360834.67110484  630761.06196032360590.58574021630358.902264283
2360565.01489248 630197.34099912
#Sta/Elev= 30
       0 3470.02    13.9 3466.64      60 3462.95    74.7 3459.84    86.2 3459.27
   126.2 3454.35     159 3447.01   196.4 3436.87   215.1 3433.87   228.4 3431.94
   243.2 3431.88   249.2 3432.06     258 3433.83   275.4 3433.48   298.7 3434.78
   330.8 3438.87   354.1 3442.57   374.4 3448.19   388.2 3449.78   444.3 3458.94
   472.2 3461.76   491.5 3462.48   500.5 3463.76   508.6 3463.07   533.5 3463.07
   545.1 3463.82   573.4 3463.01   585.9 3463.93   603.4 3462.96     634 3463.61
#Mann= 7 ,-1,0
       0     .05       0     120      .1       0   215.1    .045       0
     258      .1       0     280     .12       0     310      .1       0
  550.44     .06       0
Bank Sta=215.1,258
XS Rating Curve= 0 ,0
Exp/Cntr(USF)=0,0
Exp/Cntr=0.3,0.1

Type RM Length L Ch R = 1 ,73336   ,278.9,278.9,278.9
XS GIS Cut Line= 3
2361016.01682618 630472.202913192360964.02013034630389.770304382
2360623.80495643630167.433652135
#Sta/Elev= 30
       0 3476.51      32 3468.14    55.6 3463.57    60.3 3461.21    69.8  3450.7
    74.5  3448.6    79.2 3447.34   100.7 3443.59   140.3 3441.12     157 3439.01
   173.7 3438.15     179 3436.95   188.1 3432.76  192.673431.326   200.9 3430.85
   207.2 3429.75   215.5 3429.59  250.653431.326   264.5 3435.12   276.9 3433.32
   288.5 3434.25   302.7  3433.5   314.5 3434.51   331.9 3437.22   361.8 3446.86
   383.7 3457.39   398.3 3460.63   441.3 3463.05   479.6 3463.36   503.9 3464.22
#Mann= 7 ,-1,0
       0      .1       0      60     .12       0      80      .1       0
  192.67    .045       0  250.65     .12       0  327.46      .1       0
  447.46     .06       0
Bank Sta=192.67,250.65
XS Rating Curve= 0 ,0
Exp/Cntr=0.3,0.1

Type RM Length L Ch R = 1 ,73057   ,354,354,354
XS GIS Cut Line= 2
2361163.67878999630343.9572847382360924.96499603629926.938901826
#Sta/Elev= 30
       0 3456.69    30.9 3447.02    45.6 3445.26    90.8 3442.19   104.3  3439.1
   118.4 3438.45   127.6 3434.94   136.9 3433.32   180.5 3431.53     206 3432.13
   232.5 3431.58   254.43429.533   277.2 3427.55   288.9 3427.93  298.49 3429.54
   318.2 3440.64     327 3444.59     330 3446.58   339.7 3455.49   344.3 3456.72
   353.5 3456.88   358.1 3458.09   365.1 3464.22   371.9 3468.57   376.5 3470.47
   409.6 3474.82   422.6 3477.35   436.4 3481.26   464.1 3486.31   480.5 3487.71
#Mann= 5 ,-1,0
       0     .12       0     250     .06       0   254.4    .045       0
  298.49     .06       0     390      .1       0
Bank Sta=254.4,298.49
XS Rating Curve= 0 ,0
Exp/Cntr(USF)=0,0
Exp/Cntr=0.3,0.1

Type RM Length L Ch R = 1 ,72703   ,148,148,148
XS GIS Cut Line= 3
2361443.24314295630225.7720016572361290.88860485629886.924171706
2361163.98520851629763.021501419
#Sta/Elev= 30
       0 3464.98    40.1 3451.87    57.7 3447.42      84 3442.06   135.9 3433.67
   160.1 3426.32   176.1 3424.34   189.2 3424.46  201.91 3426.36   223.6 3429.34
   235.7 3428.67   259.4  3430.7   272.6 3433.28   298.9 3435.61   308.3 3437.37
   320.4 3441.98   332.5 3448.84   338.4 3450.98   351.5 3451.01   355.9 3453.65
   360.3 3457.42     374 3461.64   385.5 3466.34   402.7 3471.27   419.9 3479.11
   465.2 3497.95   482.8 3502.43   505.7 3506.83   541.6 3517.46   548.9 3517.98
#Mann= 6 ,-1,0
       0      .1       0     110     .12       0   160.1    .045       0
  201.91     .12       0     220     .06       0  411.52      .1       0
Bank Sta=160.1,201.91
XS Rating Curve= 0 ,0
Exp/Cntr=0.3,0.1

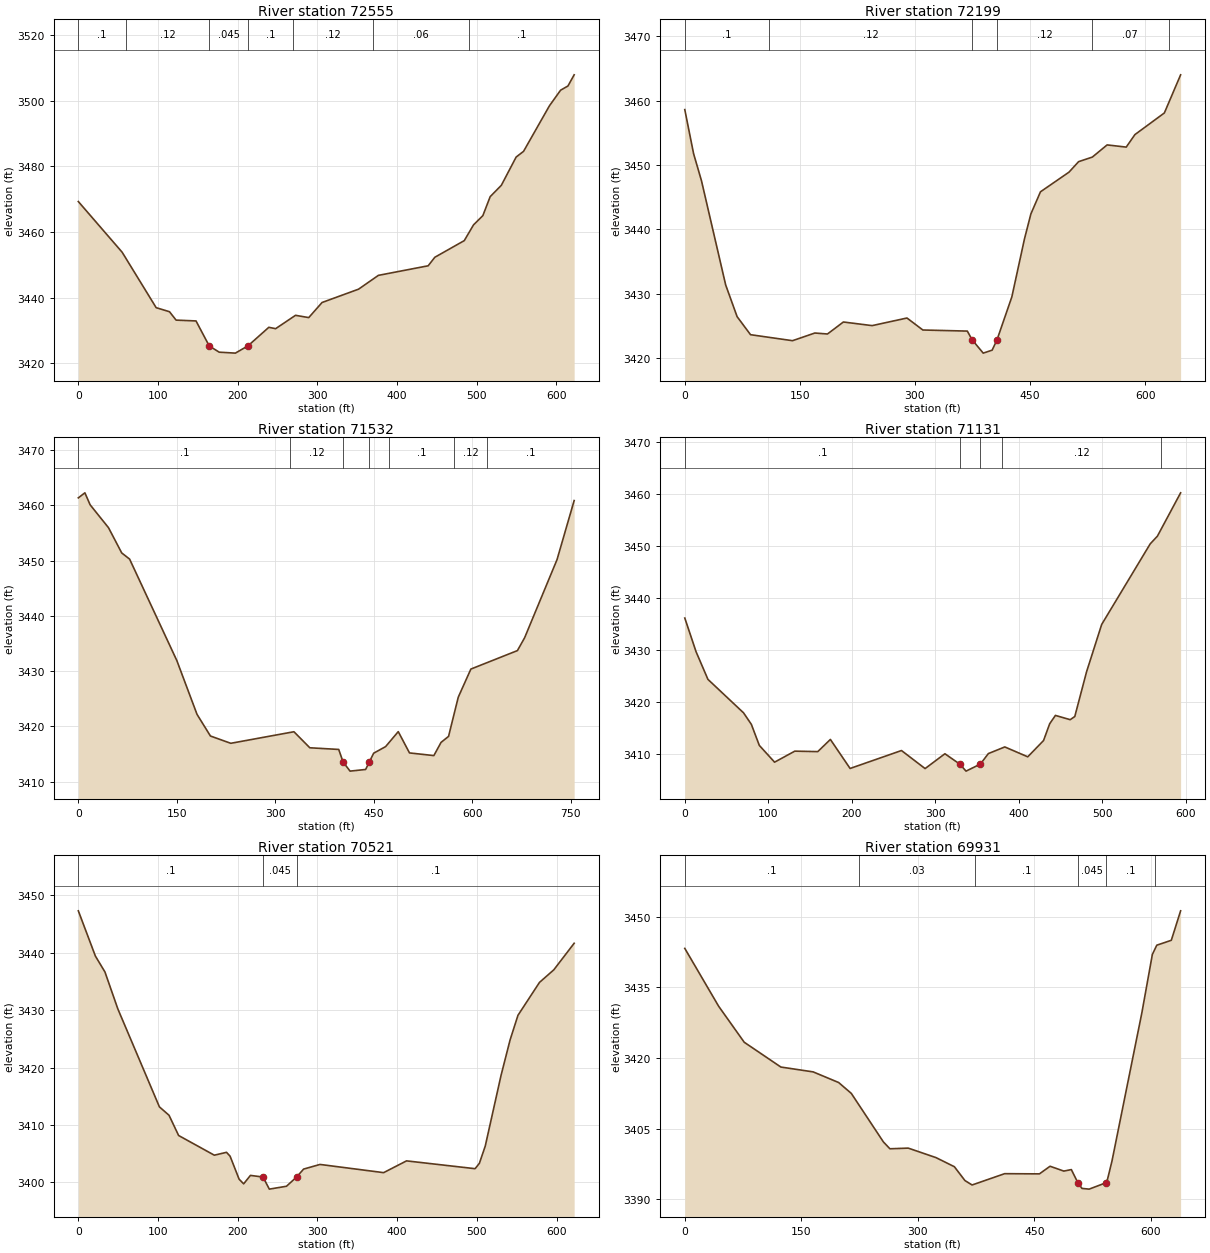
Type RM Length L Ch R = 1 ,72555   ,355.8,355.8,355.8
XS GIS Cut Line= 3
2361558.28730653630187.0882201382361433.57152846629754.480364967
2361285.47154201629666.789583513
#Sta/Elev= 30
       0 3469.29      55 3453.84    97.7 3436.94   114.4 3435.71   122.7 3433.15
   147.7  3432.9   164.3 3425.28   176.8 3423.38   197.1 3423.09  212.89  3425.3
   239.1 3430.96   247.6 3430.54   272.6 3434.61   289.2 3433.92   305.9 3438.52
   351.7 3442.58   376.6 3446.79   439.1 3449.71   447.4  3452.3   484.4 3457.38
     496 3462.18   507.7 3464.99   516.9 3470.78   530.9 3474.23   549.5 3482.85
   558.8 3484.59   591.3 3498.48   605.3 3503.23   614.5  3504.5   622.3 3507.91
#Mann= 7 ,-1,0
       0      .1       0      60     .12       0   164.3    .045       0
  212.89      .1       0     270     .12       0     370     .06       0
  490.23      .1       0
Bank Sta=164.3,212.89
XS Rating Curve= 0 ,0
Exp/Cntr(USF)=0,0
Exp/Cntr=0.3,0.1

Type RM Length L Ch R = 1 ,72199   ,667,667,667
XS GIS Cut Line= 3
2361806.12543615630214.1208613942361894.89716321630104.947949155
2361763.61985329629616.695688421
#Sta/Elev= 30
       0  3458.6    11.5 3451.75    21.8 3447.53    53.3 3431.38    68.2 3426.46
    85.7 3423.66   140.4 3422.73   169.5 3423.92     186 3423.77   206.7 3425.63
   244.2 3425.07   289.6 3426.25   310.3 3424.39   368.3 3424.22   374.5 3422.87
     389  3420.8   400.6 3421.26   406.9 3422.84   426.3 3429.53   442.8 3438.55
   451.1  3442.4   463.6 3445.84   500.8 3448.89   513.3 3450.52   531.2 3451.23
   550.5 3453.12   575.4 3452.78   586.7 3454.72   625.1 3458.08   646.3    3464
#Mann= 6 ,-1,0
       0      .1       0     110     .12       0   374.5    .045       0
   406.9     .12       0  530.71     .07       0  630.71      .1       0
Bank Sta=374.5,406.9
XS Rating Curve= 0 ,0
Exp/Cntr=0.3,0.1

Type RM Length L Ch R = 1 ,71532   ,401,401,401
XS GIS Cut Line= 3
2361878.15331049630417.2890985162362070.86321591630411.515129759
2362441.38970736629988.448677997
#Sta/Elev= 30
       0 3461.33      10 3462.24      18 3460.07      46 3455.93    66.1 3451.37
    78.1 3450.26   150.1  3431.9   180.8 3422.19   201.2 3418.28   232.2 3416.96
   328.4 3419.05   352.6 3416.15   396.6 3415.85   403.3 3413.57   413.9 3411.93
   437.6 3412.23   443.33413.598   449.8 3415.17     468 3416.36   487.3 3419.07
   504.4 3415.22   541.5 3414.74   552.5 3417.13   563.9 3418.21   578.7  3425.3
   597.9 3430.38   668.8 3433.72   679.8 3436.05   729.1 3450.16   755.2 3460.84
#Mann= 7 ,-1,0
       0      .1       0   322.8     .12       0   403.3    .045       0
   443.3     .12       0   472.8      .1       0   572.8     .12       0
   622.8      .1       0
Bank Sta=403.3,443.3
XS Rating Curve= 0 ,0
Exp/Cntr=0.3,0.1

Type RM Length L Ch R = 1 ,71131   ,610.2,610.2,610.2
XS GIS Cut Line= 2
2362347.33996703630776.6318541462362663.75242386630274.348403455
#Sta/Elev= 30
       0 3436.21    13.5 3429.73    27.7 3424.42    70.3 3417.99    79.7 3415.77
    89.2 3411.73   107.5  3408.5   131.7 3410.62   159.2 3410.53   174.3 3412.87
   197.9 3407.29   259.4 3410.74   287.7 3407.27   311.4 3410.12  329.193408.131
   336.7 3406.78   353.9 3408.14   363.4 3410.15   383.1 3411.43   410.6 3409.53
   429.5 3412.66   436.8 3415.87   443.7 3417.49   461.4 3416.67   466.9 3417.28
     481 3425.88   499.1 3434.98   557.2 3450.47   565.8 3451.95   593.6 3460.28
#Mann= 5 ,-1,0
       0      .1       0  329.19    .045       0   353.9      .1       0
     380     .12       0     570      .1       0
Bank Sta=329.19,353.9
XS Rating Curve= 0 ,0
Exp/Cntr=0.3,0.1

Type RM Length L Ch R = 1 ,70521   ,589.8,589.8,589.8
XS GIS Cut Line= 3
2362582.88405609631041.8029498012362737.24114607631056.201298545
2363084.61938209630744.153387536
#Sta/Elev= 30
       0  3447.3    21.4 3439.42    33.4 3436.65    49.5 3430.24   101.7 3413.16
   113.8 3411.69   125.8 3408.17   170.6 3404.74   185.9 3405.24   190.4 3404.56
   201.7 3400.56   207.4 3399.75   215.9 3401.22   231.73400.936   239.6 3398.83
   261.1 3399.33   273.73400.916   282.6 3402.32   303.2 3403.13     383  3401.7
   411.7 3403.75   497.7 3402.39   503.1 3403.32   510.5 3406.34   530.3 3418.65
   541.6  3424.8   551.5  3429.1   578.5 3434.83   596.5 3437.03     622 3441.65
#Mann= 3 ,-1,0
       0      .1       0   231.7    .045       0   273.7      .1       0
Bank Sta=231.7,273.7
XS Rating Curve= 0 ,0
Exp/Cntr=0.3,0.1

Type RM Length L Ch R = 1 ,69931   ,633.2,633.2,633.2
XS GIS Cut Line= 4
  2362600.314814631159.9246293192362807.74857672631213.069672885
2363097.92166443631372.8776590282363163.29210078631439.070753101
#Sta/Elev= 30
       0 3443.27    43.6 3430.98    76.5 3423.34   123.7 3418.07   165.3 3417.04
   198.1 3414.78   214.4 3412.47   255.7 3402.17   264.1 3400.71   287.7 3400.85
   323.5 3398.83   347.1  3396.9   360.7 3393.96   369.9 3393.02   411.8 3395.42
   456.6 3395.38   470.3    3397     488 3395.97   497.7 3396.29   506.1  3393.5
   511.4 3392.29   520.6 3392.14  541.77 3393.46   544.3 3394.24     550 3398.09
   588.5 3429.59     602 3441.98   607.7 3443.95   626.4 3444.99   638.4 3451.25
#Mann= 6 ,-1,0
       0      .1       0  224.13     .03       0  374.13      .1       0
   506.1    .045       0  541.77      .1       0   605.4     .06       0
Bank Sta=506.1,541.77
XS Rating Curve= 0 ,0
Exp/Cntr=0.3,0.1

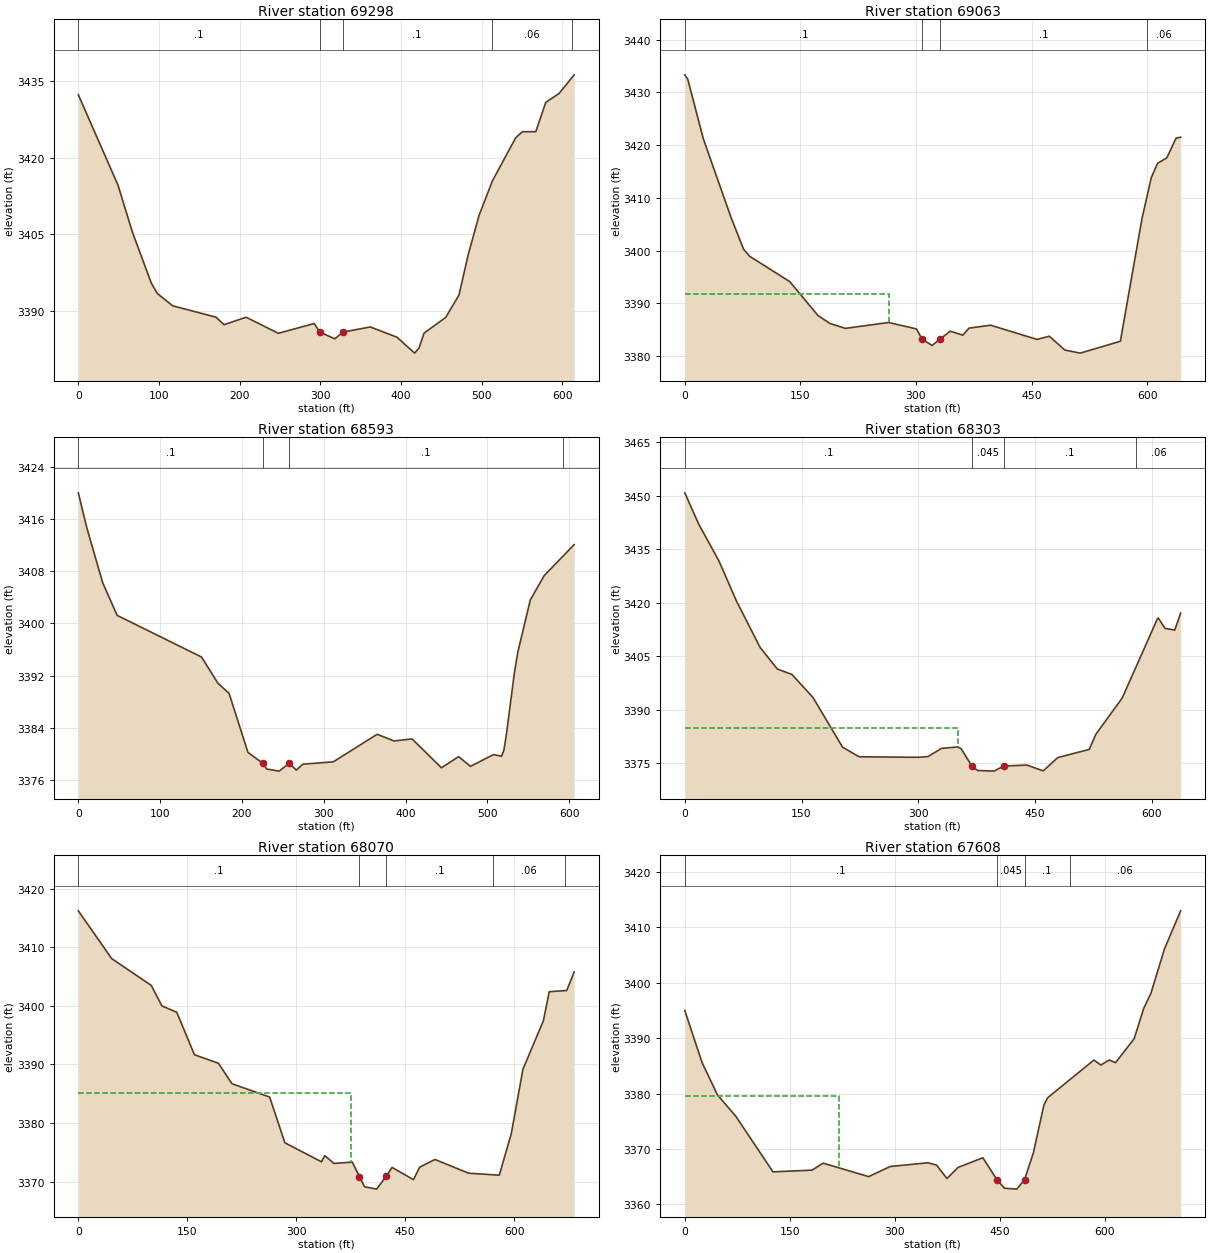
Type RM Length L Ch R = 1 ,69298   ,235.4,235.4,235.4
XS GIS Cut Line= 3
2362368.78716531 631551.076158132362712.44086649631875.105854017
2362850.16395289631838.642516531
#Sta/Elev= 30
       0 3432.38    49.2 3414.64    67.2 3405.36    90.5 3395.43    98.1 3393.36
   117.1 3390.97   170.8 3388.74   180.6 3387.27   208.1 3388.73     248 3385.58
   292.5  3387.5  299.42 3385.81     318  3384.5   328.1 3385.81     362 3386.82
     395 3384.82     417 3381.69   422.5 3382.71   428.7 3385.62   455.5 3388.69
     472 3393.08   483.5 3401.05   496.9 3408.71   513.4 3415.47   542.4 3423.97
   550.7 3425.13   567.2 3425.13   579.6 3430.88   596.2 3432.65   614.8 3436.29
#Mann= 5 ,-1,0
       0      .1       0  299.42    .045       0   328.1      .1       0
  512.33     .06       0  612.33      .1       0
Bank Sta=299.42,328.1
XS Rating Curve= 0 ,0
Exp/Cntr=0.3,0.1

Type RM Length L Ch R = 1 ,69063   ,470.1,470.1,470.1
XS GIS Cut Line= 2
2362156.18400667631941.6420144272362798.16378612 631986.21014877
#Sta/Elev= 30
       0 3433.34       4 3432.44      24 3421.23    60.1 3406.27    76.2 3400.31
    84.2 3398.94   136.3 3394.14   172.8 3387.72   188.4 3386.21   208.5 3385.28
   264.6  3386.4   300.7 3385.17  307.83 3383.26   320.8 3382.04  331.31 3383.25
   344.5 3384.75   360.9    3384   368.9 3385.33   396.9 3385.88   457.1 3383.19
   473.1 3383.79   493.2 3381.18   513.2 3380.59   565.3 3382.84   593.4 3406.12
   605.4 3413.84   613.5 3416.55   625.7 3417.63   637.5 3421.32   643.5 3421.53
#Mann= 4 ,-1,0
       0      .1       0  307.83    .045       0  331.31      .1       0
     600     .06       0
#XS Ineff= 2 , 0
          264.84  3391.8
Permanent Ineff=
       F       F
Bank Sta=307.83,331.31
XS Rating Curve= 0 ,0
Exp/Cntr(USF)=0,0
Exp/Cntr=0.3,0.1

Type RM Length L Ch R = 1 ,68593   ,289.4,289.4,289.4
XS GIS Cut Line= 3
2362557.87005926632619.0529070462362657.63629788632228.949701807
2362802.22405208632085.892291644
#Sta/Elev= 30
       0 3419.99    10.2 3414.72    29.7 3406.25    47.4 3401.23   150.6 3394.85
   170.7 3390.83   184.3 3389.28   207.3 3380.26  225.45 3378.58   230.3  3377.7
   245.5 3377.38   257.9 3378.59   266.5 3377.54   274.4 3378.44   311.6  3378.8
   365.3 3383.02   385.9    3382     408 3382.31   443.9 3377.89   464.9  3379.6
   479.4 3378.11   507.5 3379.91   517.4 3379.66   520.3 3380.64   523.1 3382.85
   533.1 3392.48   537.2 3395.58   552.5 3403.59   569.4  3407.3   606.1 3412.07
#Mann= 4 ,-1,0
       0      .1       0  225.45    .045       0   257.9      .1       0
  592.66     .06       0
Bank Sta=225.45,257.9
XS Rating Curve= 0 ,0
Exp/Cntr=0.3,0.1

Type RM Length L Ch R = 1 ,68303   ,233.3,233.3,233.3
XS GIS Cut Line= 3
 2362723.1353555632713.3708768652362787.05526494632665.430944784
2362967.19319155632138.091691891
#Sta/Elev= 30
       0 3450.76      18 3441.94    43.7 3431.78    66.3 3420.51    96.7 3407.51
   118.8 3401.45   137.7 3399.91   164.7 3393.48   202.7 3379.58   223.9 3376.87
     300 3376.72   312.6 3376.93   329.9 3379.22   350.7 3379.62   355.1 3379.15
  368.773374.327   376.1 3373.04   397.2 3372.85   409.9 3374.26   439.5 3374.55
   460.6 3372.92   479.3 3376.65   519.8 3378.93   528.2 3383.14     562 3393.27
   607.1 3415.36   608.5 3415.73     617 3412.83   629.7 3412.33   637.2 3417.09
#Mann= 4 ,-1,0
       0      .1       0  368.77    .045       0   409.9      .1       0
   579.9     .06       0
#XS Ineff= 2 , 0
           350.7    3385
Permanent Ineff=
       T       F
Bank Sta=368.77,409.9
XS Rating Curve= 0 ,0
Exp/Cntr(USF)=0,0
Exp/Cntr=0.3,0.1

Type RM Length L Ch R = 1 ,68070   ,461.8,461.8,461.8
XS GIS Cut Line= 4
 2363084.2979136632842.2938343722363045.14131098632634.313629449
2363164.45080099632275.4575102952363173.43135714632182.974569874
#Sta/Elev= 30
       0 3416.21    45.9 3408.06   100.4 3403.48   115.1 3399.97   135.5  3398.9
   159.9 3391.64   192.9 3390.19   211.6 3386.69   263.4 3384.42   284.4 3376.61
   334.9 3373.36   339.3 3374.42   351.9 3373.09   377.2 3373.31  387.063370.842
   394.1  3369.1   410.7  3368.7   423.7 3370.86     432  3372.4   461.5 3370.32
     470 3372.45     491 3373.76   537.4 3371.42   579.6 3371.08   596.1 3378.15
   612.2 3389.18   640.3 3397.43   648.4  3402.4   672.5 3402.61   682.7 3405.77
#Mann= 5 ,-1,0
       0      .1       0  387.06    .045       0   423.7      .1       0
  571.63     .06       0   669.8      .1       0
#XS Ineff= 2 , 0
          374.86 3385.17
Permanent Ineff=
       F       F
Bank Sta=387.06,423.7
XS Rating Curve= 0 ,0
Exp/Cntr=0.3,0.1

Type RM Length L Ch R = 1 ,67608   ,395,395,395
XS GIS Cut Line= 3
2363364.90872177632887.4533774162363624.01643699632329.326403613
2363581.70591328632246.350450407
#Sta/Elev= 30
       0    3395    24.6 3385.62    46.6 3379.77    73.1 3375.86     126 3365.85
   181.9 3366.16   197.7 3367.42   262.7 3364.99   293.6 3366.82   347.5 3367.49
   359.7 3367.08   374.6 3364.65   390.6 3366.66   425.9  3368.4  445.933364.454
   456.7  3362.9   474.4 3362.73  485.553364.455   498.1 3369.29   513.2 3377.95
   518.5 3379.24   584.6 3386.05   594.5 3385.15   606.5 3386.05   615.5 3385.58
   642.1  3389.9   655.9 3395.43   665.9 3398.05   685.4 3406.12   708.5 3413.01
#Mann= 4 ,-1,0
       0      .1       0  445.93    .045       0  485.55      .1       0
     550     .06       0
#XS Ineff= 2 , 0
          220.04 3379.63
Permanent Ineff=
       F       F
Bank Sta=445.93,485.55
XS Rating Curve= 0 ,0
Exp/Cntr=0.3,0.1

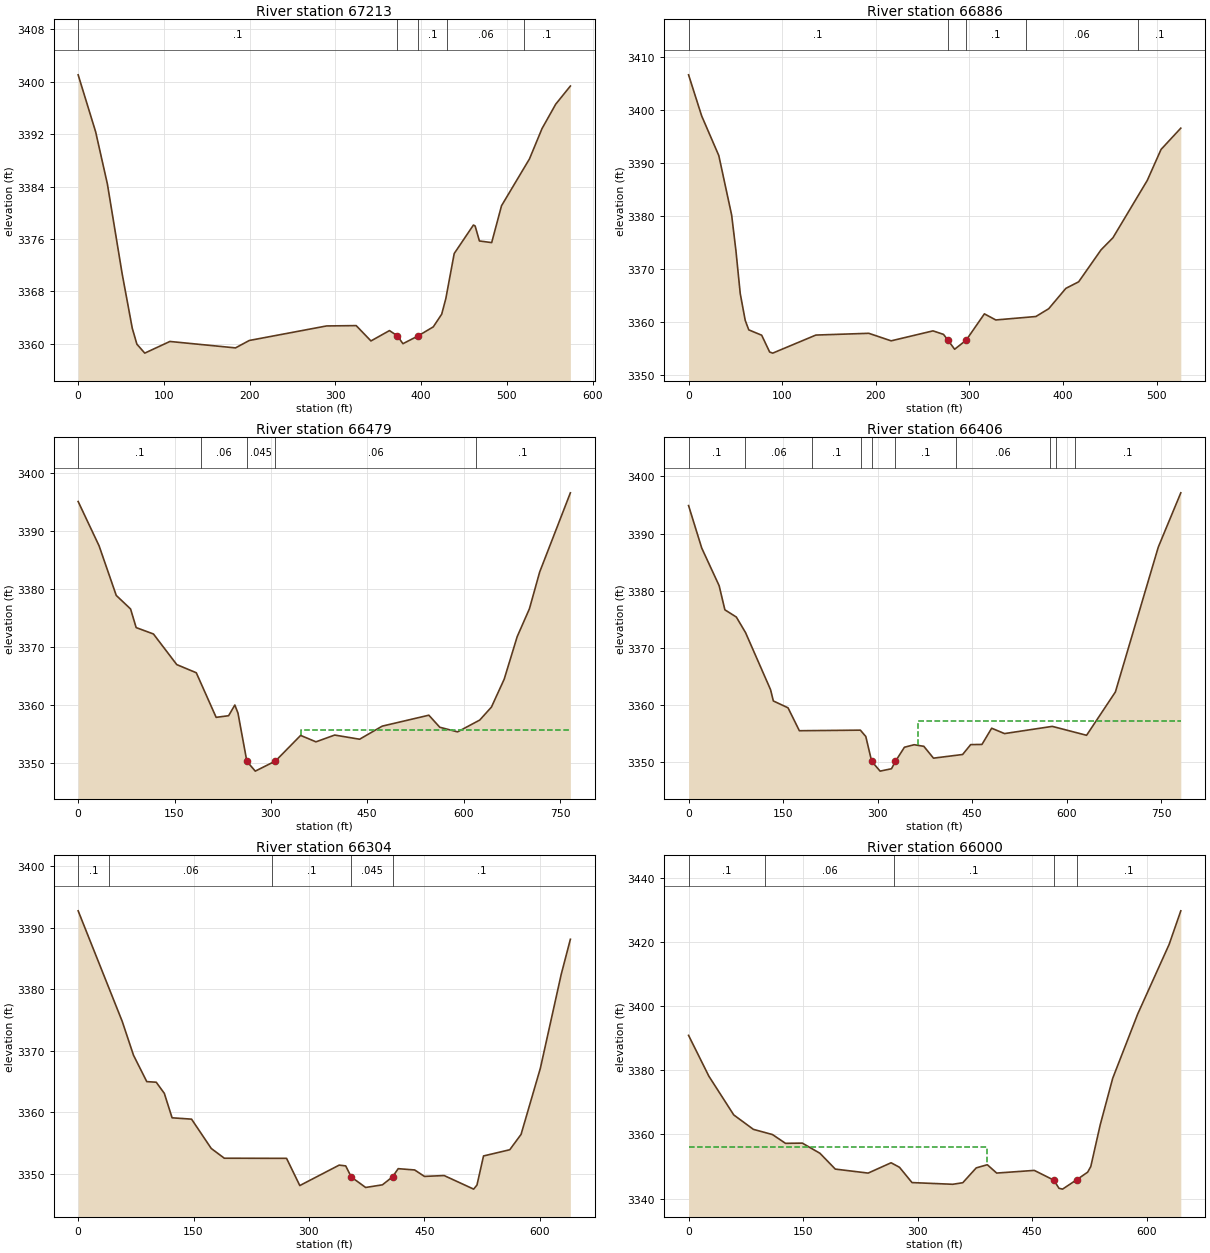
Type RM Length L Ch R = 1 ,67213   ,327.2,327.2,327.2
XS GIS Cut Line= 2
2363632.50225883633040.9416812612363960.86639272632570.006514443
#Sta/Elev= 30
       0 3401.07    20.4 3392.37    34.1 3384.41    51.3 3370.72    63.1  3362.4
    68.5 3359.96    77.7 3358.59     107 3360.37   183.5 3359.39   199.6 3360.52
   289.8 3362.74   324.3 3362.79   341.5 3360.45   363.1 3362.03  372.32 3361.23
   378.8 3360.03  396.39 3361.21   414.2  3362.6     424 3364.53   428.8  3366.9
   438.6 3373.79     461 3378.14     463    3378     468 3375.71   482.3 3375.46
   493.8 3381.09   526.4 3388.24     541 3392.86     557 3396.59   574.1 3399.36
#Mann= 5 ,-1,0
       0      .1       0  372.32    .045       0  396.39      .1       0
     430     .06       0     520      .1       0
Bank Sta=372.32,396.39
XS Rating Curve= 0 ,0
Exp/Cntr(USF)=0,0
Exp/Cntr=0.3,0.1

Type RM Length L Ch R = 1 ,66886   ,407.1,407.1,407.1
XS GIS Cut Line= 2
2363946.11727412633201.4146710132364201.58686977632741.824475967
#Sta/Elev= 30
       0  3406.7      14 3398.94    32.3 3391.46      46 3380.25    50.6 3373.49
    55.2 3365.41    60.5 3360.37    64.3 3358.57    78.1 3357.56    86.6 3354.39
    89.9 3354.18     136 3357.59   192.5 3357.92   216.4  3356.5   261.1 3358.38
   272.3 3357.72  276.98 3356.65   284.2 3354.91  296.55 3356.63     316 3361.59
   328.2 3360.44     371 3361.09   384.7 3362.56     403  3366.4   416.7 3367.64
   440.6 3373.67   453.3 3375.95     490 3386.78   504.7 3392.62   525.8 3396.64
#Mann= 5 ,-1,0
       0      .1       0  276.98    .045       0  296.55      .1       0
     360     .06       0     480      .1       0
Bank Sta=276.98,296.55
XS Rating Curve= 0 ,0
Exp/Cntr=0.3,0.1

Type RM Length L Ch R = 1 ,66479   ,73,73,73
XS GIS Cut Line= 5
2364344.79382137633438.5219861542364403.13990001633318.831923349
2364379.51928811633289.3061584722364171.13055688632986.310272289
 2364330.0205619 632823.47813722
#Sta/Elev= 30
       0 3395.16    32.6  3387.5    59.3 3378.94    81.6  3376.6    90.3 3373.38
   117.2 3372.28   153.5 3366.99   183.9 3365.58   214.8 3357.88   234.2 3358.16
   243.9 3360.01   248.8 3358.61   262.6 3350.29   275.7 3348.59   307.1 3350.33
   346.3 3354.76   370.2 3353.65   399.3 3354.82   438.1  3354.1   473.3 3356.36
   545.9 3358.25   562.9 3356.17   590.6 3355.37   625.1 3357.41   643.3 3359.65
   663.2 3364.48   683.4 3371.82   702.4 3376.62   718.4 3382.98   766.2 3396.66
#Mann= 5 ,-1,0
       0      .1       0  190.97     .06       0   262.6    .045       0
   307.1     .06       0   618.7      .1       0
#XS Ineff= 2 , 0
                          346.25         3355.66
Permanent Ineff=
       F       F
Bank Sta=262.6,307.1
XS Rating Curve= 0 ,0
Exp/Cntr(USF)=0,0
Exp/Cntr=0.3,0.1

Type RM Length L Ch R = 1 ,66406   ,101.6,101.6,101.6
XS GIS Cut Line= 5
2364403.43542272633456.3401347052364474.05821076633295.435404617
2364450.43759886 633265.909639742364213.48213748632969.772027324
2364340.43223345632830.773391996
#Sta/Elev= 30
       0 3394.91    20.9 3387.47    48.5 3380.89    57.6 3376.67    75.8  3375.4
    90.4 3372.68   130.1 3362.69   134.5 3360.72   157.8 3359.52   175.8 3355.51
   272.6 3355.61   281.2  3354.5   290.5 3350.16   303.9 3348.44     322 3348.86
   328.13350.139   342.5 3352.62   357.9 3353.06   373.3 3352.78   388.6 3350.71
   434.8 3351.35   447.6 3353.08   465.5 3353.11   480.9 3355.95   501.3 3355.01
   577.1 3356.27   631.5 3354.71   677.2 3362.29   745.3 3387.65     781 3397.14
#Mann= 10 ,-1,0
       0      .1       0      90     .06       0  195.72      .1       0
  273.53     .06       0   290.5    .045       0   328.1      .1       0
  423.53     .06       0  573.53      .1       0  583.53     .06       0
   612.8      .1       0
#XS Ineff= 2 , 0
                          364.48         3357.22
Permanent Ineff=
       F       F
Bank Sta=290.5,328.1
XS Rating Curve= 0 ,0
Exp/Cntr(USF)=0,0
Exp/Cntr=0.3,0.1

Type RM Length L Ch R = 1 ,66304   ,304.5,304.5,304.5
XS GIS Cut Line= 4
2364508.85749192633507.5074460672364572.13888275633391.276320051
2364418.45550501632975.427180304  2364448.159015632918.603074252
#Sta/Elev= 30
       0 3392.77    57.3 3374.77      72 3369.25    89.2 3364.97   101.5 3364.87
     112 3363.06   122.1 3359.08   147.4 3358.86     173 3354.09     190  3352.5
   270.9 3352.48   288.1 3348.05   339.3 3351.38   347.8 3351.25     355 3349.44
   373.7 3347.74   395.5 3348.17  408.653349.471     416  3350.8   437.4 3350.59
   450.1 3349.54   475.7 3349.68   514.1 3347.47   518.4 3348.14   526.9 3352.87
     561 3353.88   575.7 3356.38   600.8 3367.16   627.9 3382.44   639.8 3388.14
#Mann= 5 ,-1,0
       0      .1       0      40     .06       0  252.34      .1       0
     355    .045       0  408.65      .1       0
Bank Sta=355,408.65
XS Rating Curve= 0 ,0
Exp/Cntr(USF)=0,0
Exp/Cntr=0.3,0.1

Type RM Length L Ch R = 1 ,66000   ,231,231,231
XS GIS Cut Line= 3
 2364619.4024986633556.8189727062364686.22785847633434.790054681
2364800.99315042632942.316206938
#Sta/Elev= 30
       0 3390.89    26.6 3378.16    59.2 3366.08    84.9 3361.58   109.9 3359.96
     127 3357.22     149 3357.29   172.1 3354.12   192.2 3349.19   235.2 3347.94
   265.3 3351.16   276.3 3349.75   292.7 3344.98   346.1 3344.45   359.2 3344.94
   376.8 3349.56   391.3 3350.55   403.6 3347.95   452.9 3348.78   478.5 3345.74
   485.2 3343.21   489.9 3342.94   508.2 3345.83   522.8 3348.23   526.9    3350
   539.2 3362.96   555.6 3377.51   588.4 3397.58   629.5 3419.25   644.8 3429.73
#Mann= 5 ,-1,0
       0      .1       0     100     .06       0  269.13      .1       0
   478.5    .045       0   508.2      .1       0
#XS Ineff= 2 , 0
           391.3    3356
Permanent Ineff=
       F       F
Bank Sta=478.5,508.2
XS Rating Curve= 0 ,0
Exp/Cntr(USF)=0,0
Exp/Cntr=0.3,0.1

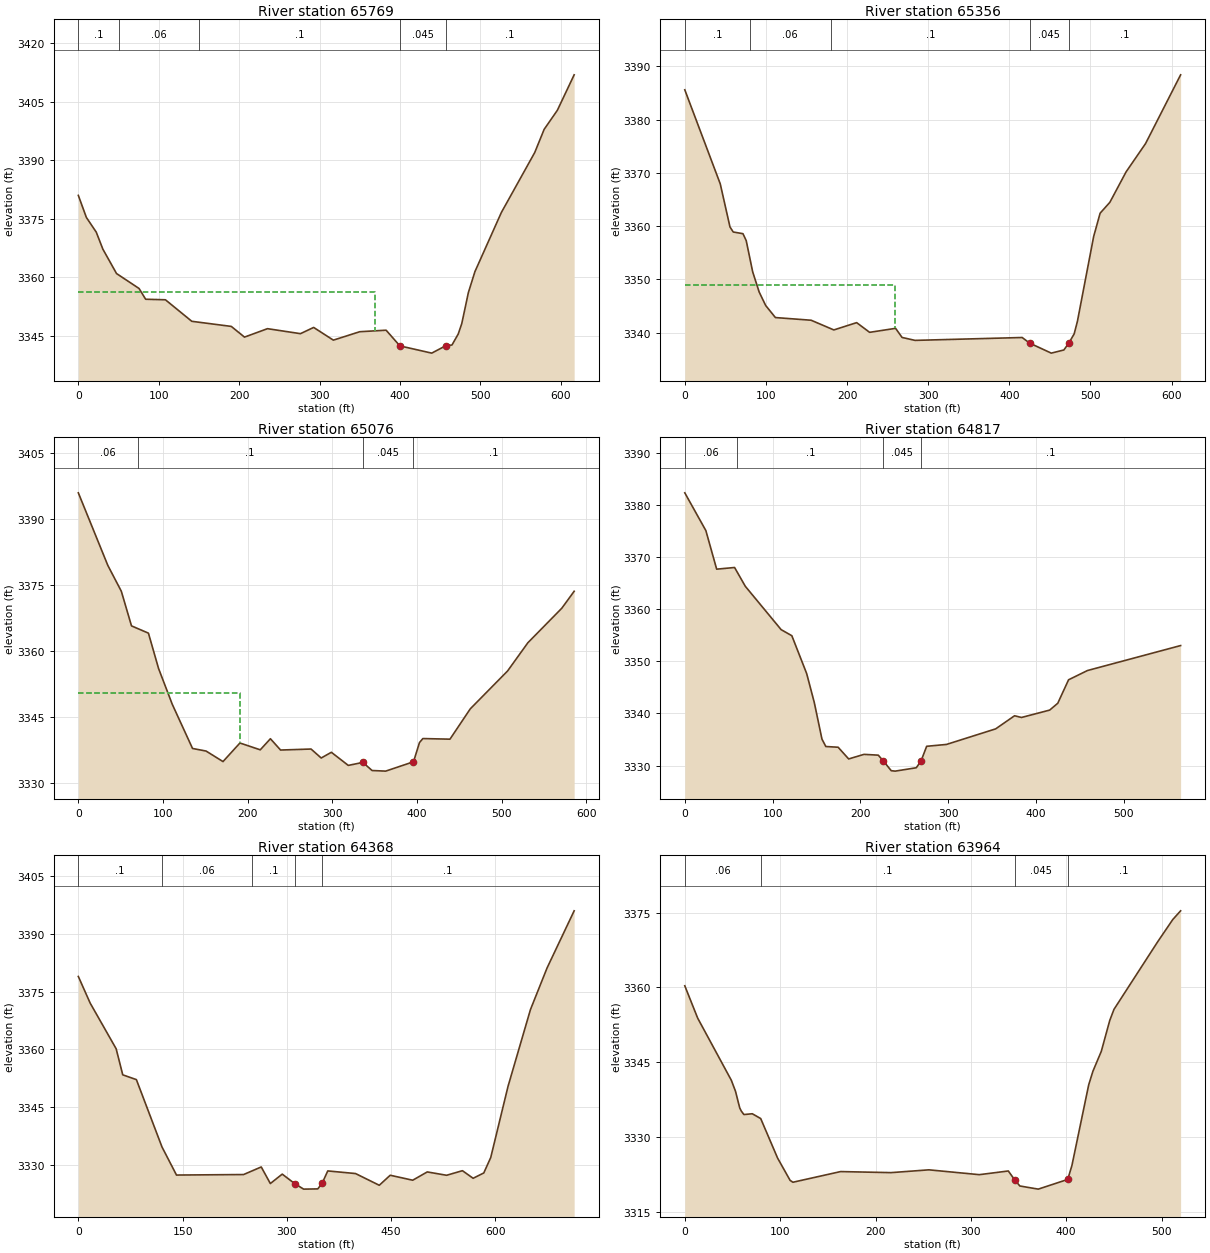
Type RM Length L Ch R = 1 ,65769   ,412.1,412.1,412.1
XS GIS Cut Line= 2
2364878.64513201633618.9596713582365010.67566554633016.724611849
#Sta/Elev= 30
       0 3380.98      10 3375.33    22.3 3371.55    30.5  3367.2    47.5 3360.94
    75.5 3357.11    83.7 3354.35   108.3 3354.21   141.1 3348.69   190.2 3347.38
   206.6 3344.64   235.2  3346.8   276.2 3345.52   292.6 3347.12   317.1 3343.86
   349.9 3346.02   382.7 3346.41  399.793342.387   439.4 3340.53   456.6 3342.39
   464.6 3342.62   472.4 3345.45   476.8 3348.14     485 3356.08   493.1 3361.42
     526  3376.6   567.5 3391.98   579.2 3397.92   595.6  3402.8   616.5  3411.9
#Mann= 5 ,-1,0
       0      .1       0      50     .06       0     150      .1       0
  399.79    .045       0   456.6      .1       0
#XS Ineff= 2 , 0
          368.49 3356.25
Permanent Ineff=
       F       F
Bank Sta=399.79,456.6
XS Rating Curve= 0 ,0
Exp/Cntr=0.3,0.1

Type RM Length L Ch R = 1 ,65356   ,280.6,280.6,280.6
XS GIS Cut Line= 2
2365371.88022082633652.8521318032365388.77968352633041.947770116
#Sta/Elev= 30
       0 3385.57    43.7 3367.93    55.7 3359.84    59.7  3358.9    71.7 3358.58
    75.7 3357.28    83.7 3351.41    91.7 3347.63    99.7 3345.11   111.7 3342.85
   155.7 3342.35   183.7 3340.53   211.8  3341.9   227.8 3340.08   259.8 3340.83
   267.8 3339.12   283.8 3338.57   415.8 3339.11  425.063338.052   451.7 3336.18
   467.2 3336.77  473.283338.053   479.9 3339.79   483.9 3342.14   503.9 3358.04
   511.9 3362.43   523.9 3364.47   543.9 3370.18   567.9 3375.49   611.1 3388.38
#Mann= 5 ,-1,0
       0      .1       0      80     .06       0     180      .1       0
  425.06    .045       0  473.28      .1       0
#XS Ineff= 2 , 0
          258.83    3349
Permanent Ineff=
       F       F
Bank Sta=425.06,473.28
XS Rating Curve= 0 ,0
Exp/Cntr=0.3,0.1

Type RM Length L Ch R = 1 ,65076   ,258.7,258.7,258.7
XS GIS Cut Line= 2
 2365645.0265001633643.9824855812365662.45920267633058.534224104
#Sta/Elev= 30
       0 3396.01    34.8 3379.54    50.8 3373.64    62.8 3365.78    82.8 3364.13
    94.8 3356.09     111 3347.95   134.9 3337.93   150.9 3337.34   170.9 3334.95
   190.9 3339.17   214.9 3337.62   226.9 3340.14   238.9 3337.57   274.9  3337.8
   286.9 3335.76   298.9 3337.06   318.9 3334.08   336.1 3334.76     347 3332.92
     363 3332.78  395.91  3334.9     403 3339.27     407 3340.18     439 3340.04
     463 3346.93     507 3355.52     531 3361.94   571.1 3369.79   585.7 3373.64
#Mann= 4 ,-1,0
       0     .06       0      70      .1       0   336.1    .045       0
  395.91      .1       0
#XS Ineff= 2 , 0
          191.26  3350.5
Permanent Ineff=
       F       F
Bank Sta=336.1,395.91
XS Rating Curve= 0 ,0
Exp/Cntr(USF)=0,0
Exp/Cntr=0.3,0.1

Type RM Length L Ch R = 1 ,64817   ,448.7,448.7,448.7
XS GIS Cut Line= 6
2365808.07945255633628.7270196422365833.47536927 633502.05389006
2365867.87123386633421.1234628022365893.20024094633372.671102749
2365909.84324571633312.5201294692365995.75710269633098.772206855
#Sta/Elev= 30
       0  3382.4      24 3375.14    36.3 3367.73    56.7 3368.05    68.9 3364.44
   109.7 3356.11   121.9 3354.94   138.8 3347.66   147.5 3342.07   156.2 3335.07
   160.6 3333.65   174.6 3333.51   186.6 3331.26     204 3332.14   220.3 3331.99
   225.9 3330.91   235.1    3329   239.6 3328.92   263.6 3329.57   269.1  3330.9
   275.4 3333.69     298 3334.05     354 3337.04   375.5 3339.56   383.4 3339.23
   415.5 3340.65   424.7 3341.96     437 3346.47   458.5 3348.25   564.6 3353.05
#Mann= 4 ,-1,0
       0     .06       0      60      .1       0   225.9    .045       0
   269.1      .1       0
Bank Sta=225.9,269.1
XS Rating Curve= 0 ,0
Exp/Cntr=0.3,0.1

Type RM Length L Ch R = 1 ,64368   ,404.8,404.8,404.8
XS GIS Cut Line= 4
2365879.64328853633903.0410880332365995.77796372 633871.54693883
2366367.80260117633580.2260587072366483.93727636633548.731909504
#Sta/Elev= 30
       0 3378.93    17.1    3372    54.4 3360.18    63.9 3353.42    83.5 3352.18
   120.3 3334.73   141.2 3327.43   237.7 3327.56   263.1 3329.53   276.2 3325.23
   293.3 3327.67  311.373325.192   324.1 3323.78   344.4 3323.84  350.573325.249
   358.8  3328.5   398.7 3327.82   432.9 3324.78   448.6 3327.38     481 3326.09
   501.9 3328.24   529.7 3327.37   552.5 3328.56   567.9 3326.59   583.2 3327.97
   593.2 3331.97   618.1 3350.44   650.3 3370.32   674.3 3381.16   713.2 3395.95
#Mann= 5 ,-1,0
       0      .1       0     120     .06       0  250.33      .1       0
  311.37    .045       0  350.57      .1       0
Bank Sta=311.37,350.57
XS Rating Curve= 0 ,0
Exp/Cntr(USF)=0,0
Exp/Cntr=0.3,0.1

Type RM Length L Ch R = 1 ,63964   ,564.1,564.1,564.1
XS GIS Cut Line= 2
2366023.94686951634243.5805271062366495.63530427634024.626744522
#Sta/Elev= 30
       0 3360.33    13.5 3353.85    48.8 3341.38    53.2 3339.16    57.6 3335.84
    59.2 3335.22      62  3334.5    70.8 3334.66    79.6  3333.7    97.3 3325.78
   110.4 3321.31   113.4 3320.92   163.4 3323.06   216.3 3322.85     256 3323.41
   308.9 3322.44   339.3 3323.18  345.853321.436   351.4 3320.17   370.7 3319.54
  401.613321.486     406 3324.28   423.6 3340.46     428 3343.18   436.8 3347.18
   445.7 3353.39   450.1  3355.6   495.9 3369.15   511.8 3373.63     520 3375.37
#Mann= 4 ,-1,0
       0     .06       0      80      .1       0  345.85    .045       0
  401.61      .1       0
Bank Sta=345.85,401.61
XS Rating Curve= 0 ,0
Exp/Cntr=0.3,0.1