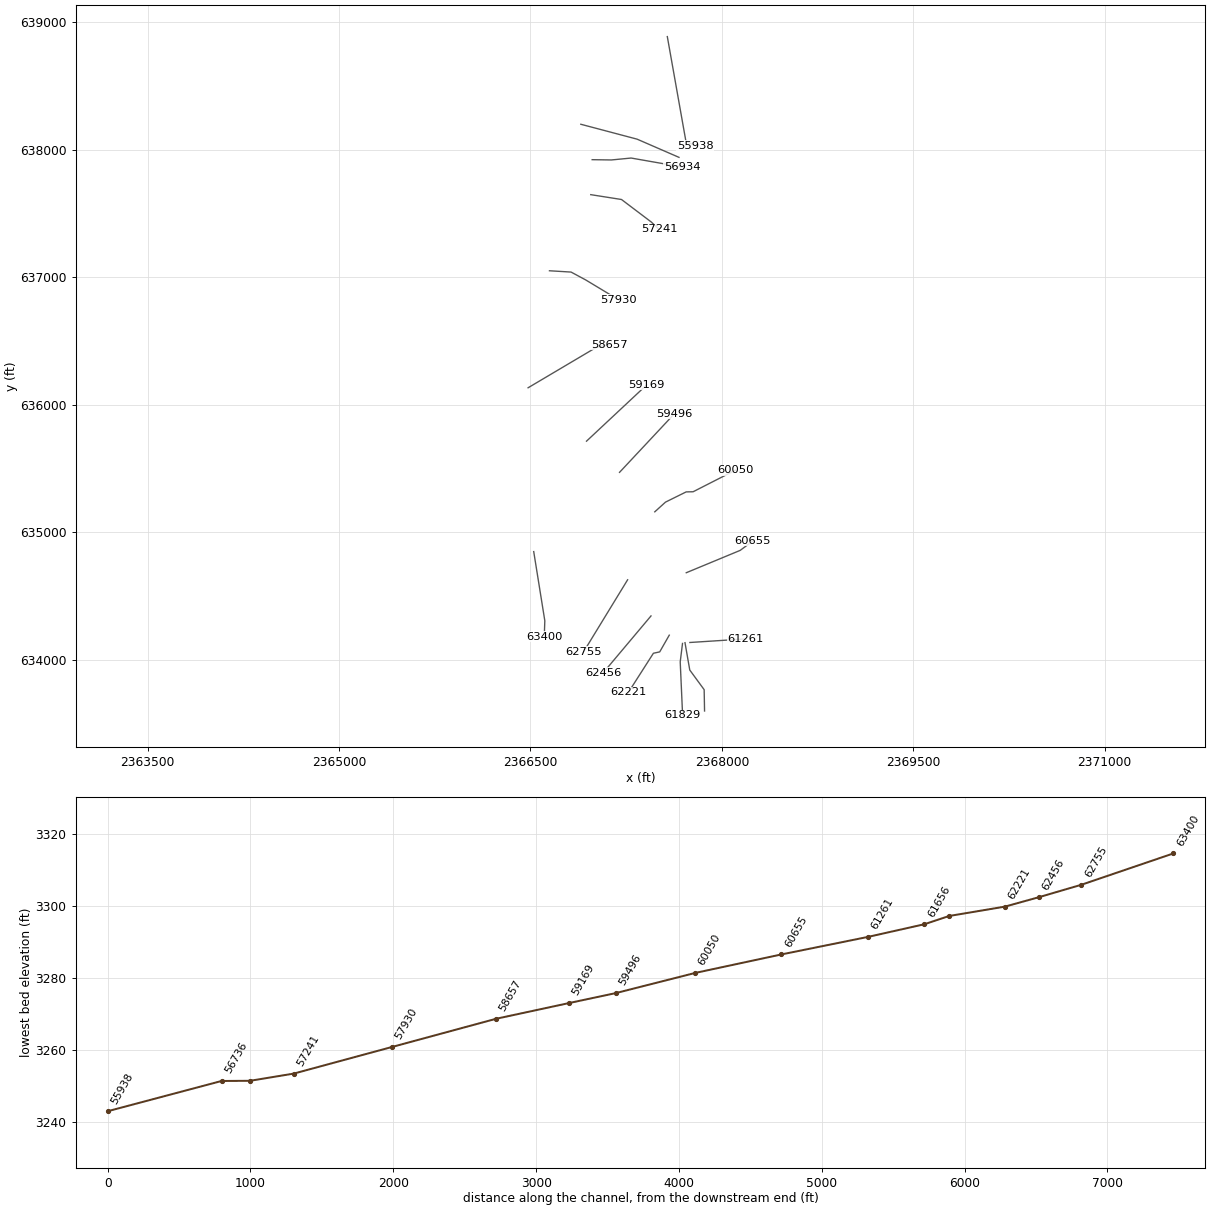
HEC-RAS study GNDYCK_1.prj: GNDYCK_1

--- GNDYCK_1.g01 (geometry) --- (continued)

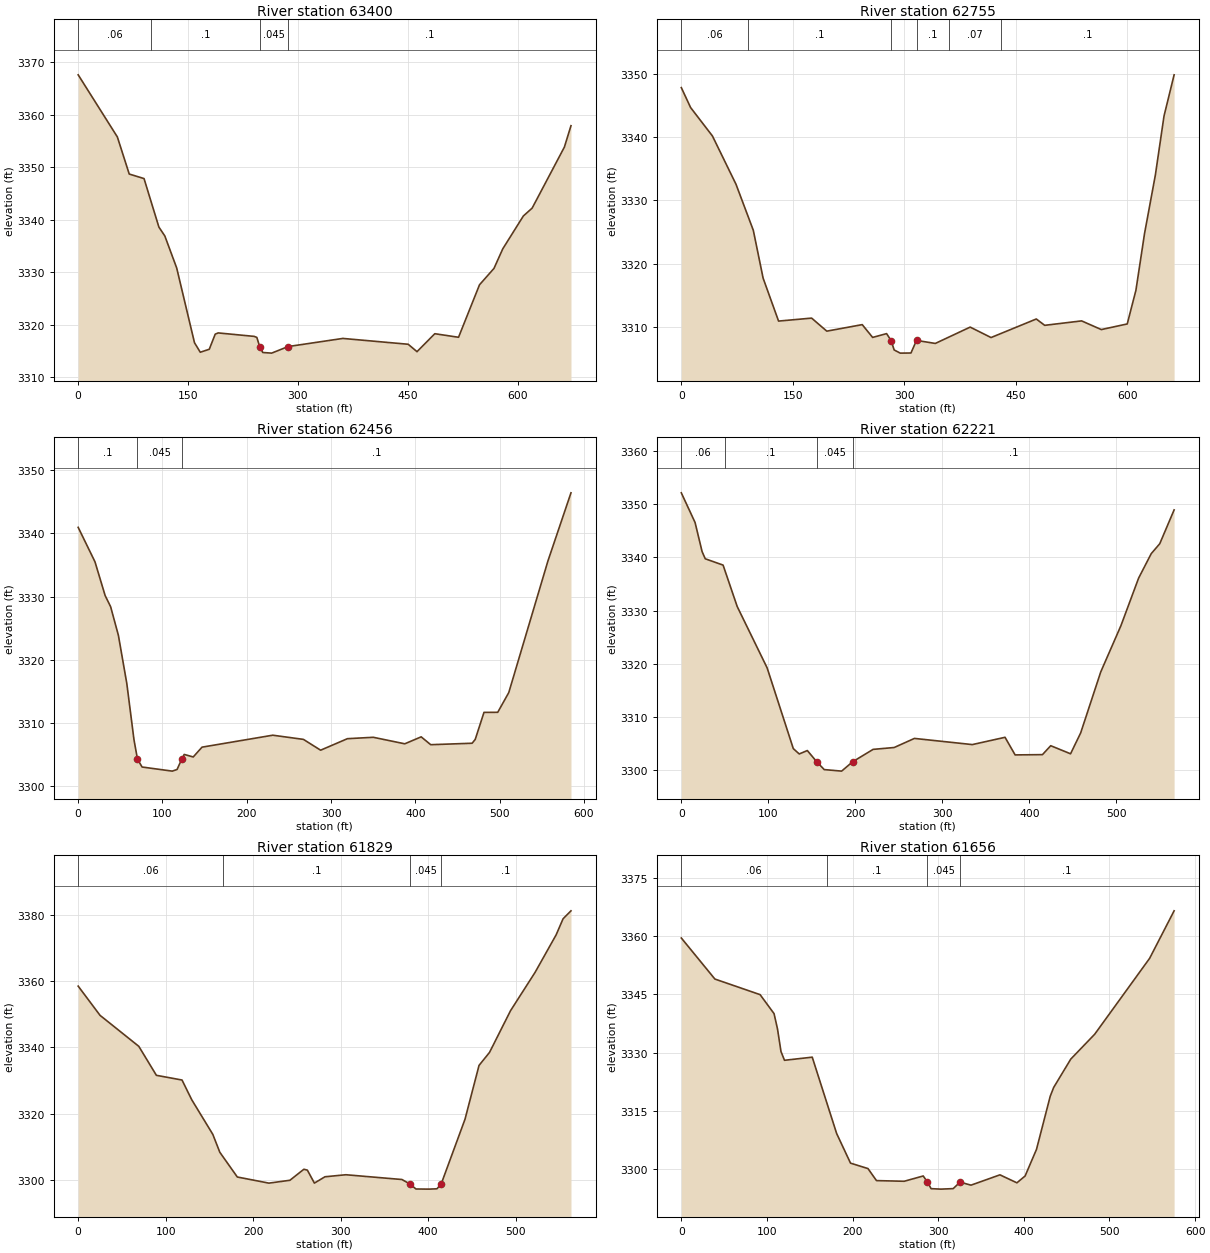
Type RM Length L Ch R = 1 ,63400   ,644.7,644.7,644.7
XS GIS Cut Line= 3
2366525.58434782634849.9617824282366612.59138615634307.822327623
2366608.30752186 634184.13008681
#Sta/Elev= 30
       0 3367.63    53.5 3355.79    69.7 3348.72    89.9 3347.86   110.2 3338.61
   118.3 3336.92   134.5 3330.82   158.8 3316.57   166.7 3314.76     179 3315.33
   187.1 3318.21   191.2 3318.44   240.3 3317.78   243.9 3317.59   247.9 3315.79
     252 3314.71   264.1 3314.59  286.633315.841   361.3 3317.39   450.5 3316.28
   462.6 3314.87   486.9 3318.29   519.3 3317.61   547.9 3327.61   567.7 3330.74
   579.7 3334.47   607.8 3340.73   619.8 3342.23   663.8 3353.86   672.8 3357.93
#Mann= 4 ,-1,0
       0     .06       0     100      .1       0   247.9    .045       0
  286.63      .1       0
Bank Sta=247.9,286.63
XS Rating Curve= 0 ,0
Exp/Cntr=0.3,0.1

Type RM Length L Ch R = 1 ,62755   ,299.2,299.2,299.2
XS GIS Cut Line= 2
2367261.57834764 634628.917608632366915.73986957634062.961391237
#Sta/Elev= 30
       0 3347.81    12.5 3344.66    41.9 3340.17    73.6 3332.55    96.9 3325.28
   110.1 3317.72   130.9 3310.94   175.4 3311.41   195.8 3309.35   243.5 3310.38
   257.5 3308.36   276.3 3308.96  282.34 3307.87   286.5 3306.38   294.7 3305.88
   309.1  3305.9  316.563307.888   341.9 3307.41   388.8 3309.99   416.9 3308.34
   477.8 3311.27   489.1 3310.27   538.8 3310.97   565.3  3309.6   600.2 3310.49
   611.9 3315.81   623.5 3324.77   638.1 3334.03   649.7 3343.32   663.3 3349.83
#Mann= 6 ,-1,0
       0     .06       0      90      .1       0  282.34    .045       0
  316.56      .1       0     360     .07       0     430      .1       0
Bank Sta=282.34,316.56
XS Rating Curve= 0 ,0
Exp/Cntr=0.3,0.1

Type RM Length L Ch R = 1 ,62456   ,235.1,235.1,235.1
XS GIS Cut Line= 2
2367444.95304096634345.6487642242367068.69721039633898.209398133
#Sta/Elev= 30
       0 3340.96    19.9 3335.52      32 3330.17    38.5 3328.41    47.7 3323.89
    57.7 3316.26    66.2 3307.38   70.323304.311    75.8 3303.06   111.6 3302.41
   117.3 3302.67     123 3304.34   125.8 3305.05   136.5 3304.65   146.9  3306.2
   230.8 3308.09   267.2 3307.43   287.6 3305.72   319.4 3307.54   350.1 3307.76
   387.4 3306.73   406.9 3307.83   418.2 3306.59   467.3 3306.82     471 3307.42
   481.4  3311.7   497.7 3311.71   510.8 3314.83   557.3 3335.66   584.6 3346.42
#Mann= 3 ,-1,0
       0      .1       0   70.32    .045       0     123      .1       0
Bank Sta=70.32,123
XS Rating Curve= 0 ,0
Exp/Cntr(USF)=0,0
Exp/Cntr=0.3,0.1

Type RM Length L Ch R = 1 ,62221   ,391.9,391.9,391.9
XS GIS Cut Line= 4
2367588.05000388634194.7996720132367513.20342925634063.818166413
2367463.75122816634053.1257986092367267.27896976 633745.72022424
#Sta/Elev= 30
       0 3352.15    15.8 3346.57    23.9 3341.09    27.5 3339.75      48 3338.56
    64.2 3330.78    98.6 3319.24   128.7 3304.05   135.5 3303.05   144.8 3303.69
   155.6 3301.59   164.2 3300.11   184.2 3299.82   196.9 3301.58   220.4 3303.91
   244.6 3304.26   267.9 3305.97   334.4 3304.81     372 3306.18   383.6 3302.87
     415 3302.92   424.5  3304.6   447.3 3303.08   458.9    3307     482 3318.48
   505.2 3327.18   525.5 3336.11     540 3340.71   549.8 3342.58   566.3 3348.94
#Mann= 4 ,-1,0
       0     .06       0      50      .1       0   155.6    .045       0
   196.9      .1       0
Bank Sta=155.6,196.9
XS Rating Curve= 0 ,0
Exp/Cntr(USF)=0,0
Exp/Cntr=0.3,0.1

Type RM Length L Ch R = 1 ,61829   ,173,173,173
XS GIS Cut Line= 3
 2367691.9401009634129.9386314222367673.95911598633985.952581446
2367692.66364208633568.185240616
#Sta/Elev= 30
       0 3358.48      25 3349.66    69.3 3340.31    89.4 3331.56   118.7 3330.14
   129.8 3324.19   153.9 3313.74   161.9 3308.34   181.9 3300.87     218 3299.02
     242 3299.88     258 3303.21     262 3302.94     270 3299.03   282.1 3300.94
     306 3301.55   370.1 3300.11   379.33298.732   386.1 3297.25   400.9 3297.21
   410.1 3297.31  414.94 3298.76   442.2 3318.33   458.2 3334.55   470.2 3338.48
   494.2 3351.06   522.3 3362.65   546.3 3373.94   554.3 3378.82   563.3 3381.21
#Mann= 4 ,-1,0
       0     .06       0   165.1      .1       0   379.3    .045       0
  414.94      .1       0
Bank Sta=379.3,414.94
XS Rating Curve= 0 ,0
Exp/Cntr=0.3,0.1

Type RM Length L Ch R = 1 ,61656   ,395.1,395.1,395.1
XS GIS Cut Line= 4
2367711.44220008634135.8426824512367748.80922855633921.554213051
2367861.67290638633767.5105446572367864.72327606633600.502805161
#Sta/Elev= 30
       0 3359.46    39.2 3348.91      92  3344.9   108.3 3340.02   112.3 3336.12
   116.4 3330.28   120.5 3328.03   152.9 3328.83   181.4 3309.21   197.6  3301.6
     218  3300.2   227.9 3297.11   260.3 3296.94   282.5  3298.3   287.4 3296.75
   291.7 3295.04   303.2 3294.92   317.5 3295.05  325.46 3296.72   338.3 3295.94
   372.1 3298.59   391.9 3296.54   401.5  3298.3   414.8 3305.15   430.8 3318.77
   434.8 3321.03   454.8 3328.33   482.8 3334.74   546.9 3354.23   575.5 3366.44
#Mann= 4 ,-1,0
       0     .06       0     170      .1       0   287.4    .045       0
  325.46      .1       0
Bank Sta=287.4,325.46
XS Rating Curve= 0 ,0
Exp/Cntr(USF)=0,0
Exp/Cntr=0.3,0.1

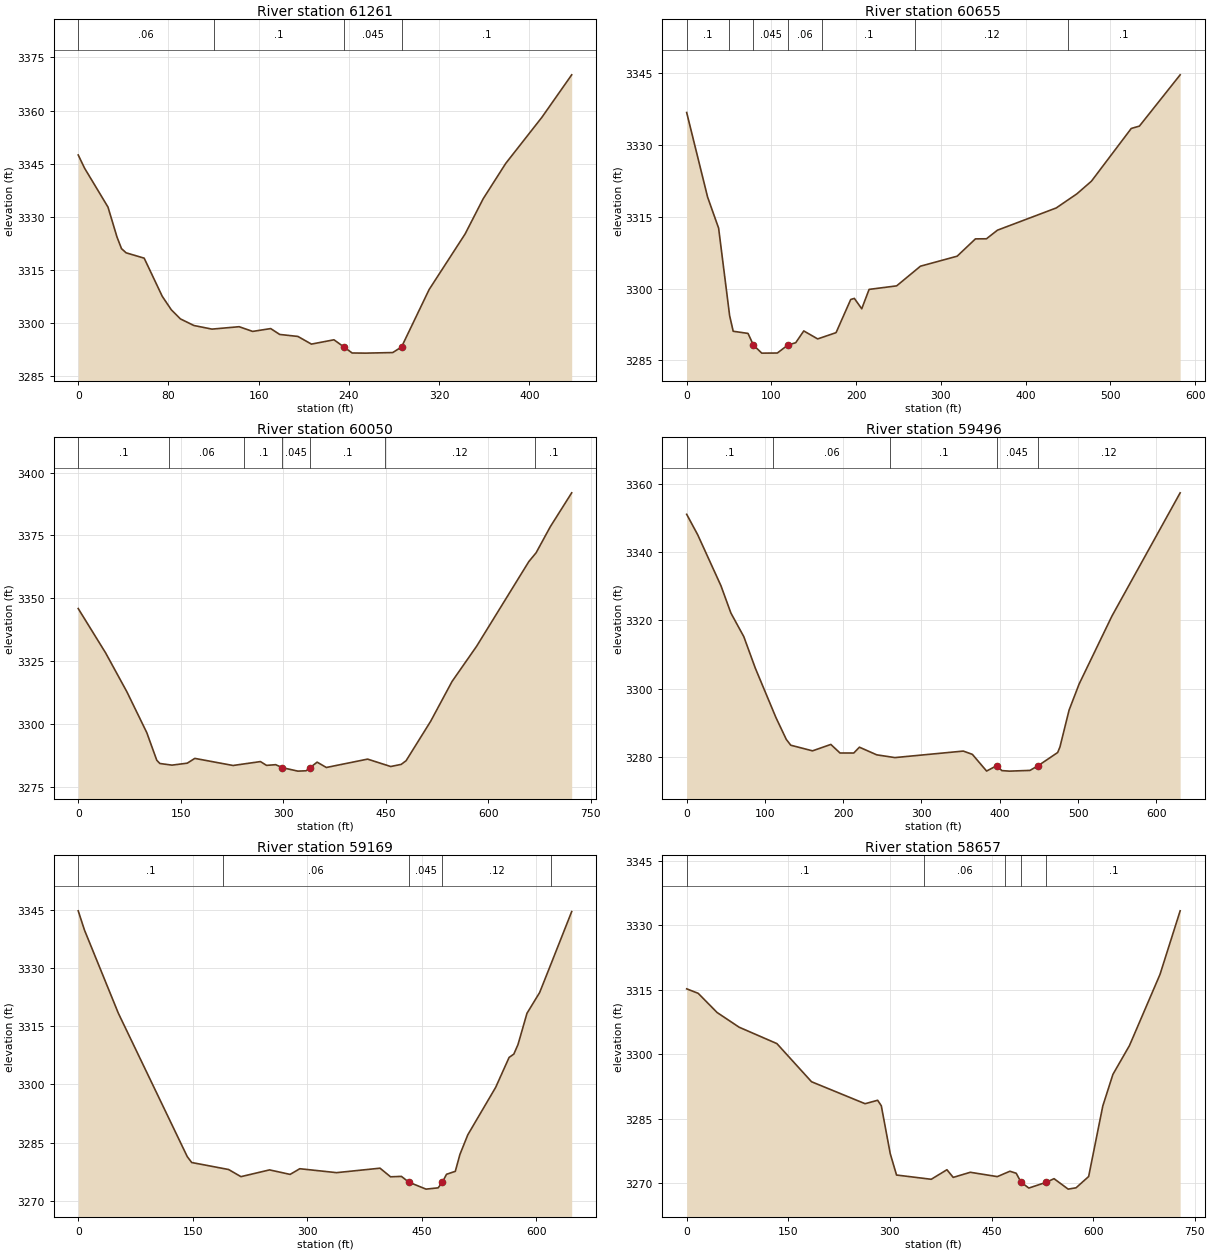
Type RM Length L Ch R = 1 ,61261   ,605.2,605.2,605.2
XS GIS Cut Line= 2
2367749.80879883634137.4756676382368186.52236958634165.494173009
#Sta/Elev= 30
       0 3347.43     5.7 3343.66    26.4  3332.7    34.4 3324.22    38.4 3320.94
    42.5 3319.76    58.5 3318.25    74.5 3307.48    82.5 3303.68    90.6 3301.08
   102.6 3299.21   118.6 3298.19   142.7 3298.87   154.7 3297.54   170.7 3298.34
   178.7 3296.68   194.8 3296.12   206.8 3293.95   226.8 3295.17  235.713293.127
   242.9 3291.44   254.9  3291.4   278.9 3291.56   286.73293.128   311.2 3309.39
   343.1  3325.1   359.1 3335.04   379.1 3345.04   411.2 3358.09   437.6 3370.09
#Mann= 4 ,-1,0
       0     .06       0     120      .1       0  235.71    .045       0
   286.7      .1       0
Bank Sta=235.71,286.7
XS Rating Curve= 0 ,0
Exp/Cntr=0.3,0.1

Type RM Length L Ch R = 1 ,60655   ,605,605,605
XS GIS Cut Line= 3
2367721.32555153634684.2549073922368144.13955908634859.544776196
2368244.31983948634933.860701595
#Sta/Elev= 30
       0 3336.83    24.7 3319.15    37.7 3312.66    50.7 3294.36    54.9 3291.11
    72.4 3290.66   78.74 3288.22    88.6 3286.54     107 3286.56   119.2  3288.2
   128.7 3288.72   138.2 3291.18   154.6 3289.51   176.3 3290.82   193.6 3297.75
   197.9 3297.98   206.6 3295.81   215.3 3299.86   247.8  3300.6   275.9 3304.71
   319.2  3306.8   340.8 3310.42   353.8 3310.44   366.8 3312.24   436.1 3316.88
   460.5 3319.83   477.7 3322.48   524.7  3333.5   534.3 3333.99   582.4 3344.71
#Mann= 7 ,-1,0
       0      .1       0      50     .06       0   78.74    .045       0
   119.2     .06       0     160      .1       0     270     .12       0
     450      .1       0
Bank Sta=78.74,119.2
XS Rating Curve= 0 ,0
Exp/Cntr=0.3,0.1

Type RM Length L Ch R = 1 ,60050   ,554.1,554.1,554.1
XS GIS Cut Line= 5
2367474.68312656635161.7592502142367558.53315475635237.773795756
2367720.53066733635317.8989787932367775.08809734635319.081256915
2368108.16022476635488.844543639
#Sta/Elev= 30
       0 3345.97    40.3 3328.27    71.4 3312.82   100.4 3296.66     115  3285.7
   119.5 3284.42   137.3 3283.77   159.6 3284.55   170.7 3286.45   226.6 3283.63
   266.7 3285.18   275.7 3283.67     289 3283.95  298.88 3282.76   321.6 3281.39
   333.6 3281.53   339.3 3282.77   349.7 3284.95   363.2 3282.84   423.6 3286.16
   457.4 3283.22   472.8 3284.07   479.9 3285.52   515.8 3301.16   547.2 3317.01
   583.2 3331.02   659.5  3364.6   670.2 3368.12   690.9 3378.44   722.3 3391.94
#Mann= 7 ,-1,0
       0      .1       0  133.18     .06       0  243.18      .1       0
  298.88    .045       0   339.3      .1       0  448.48     .12       0
  668.48      .1       0
Bank Sta=298.88,339.3
XS Rating Curve= 0 ,0
Exp/Cntr=0.3,0.1

Type RM Length L Ch R = 1 ,59496   ,327.6,327.6,327.6
XS GIS Cut Line= 2
2367198.26473763635471.1649715442367629.17395389635931.448180256
#Sta/Elev= 30
       0 3351.14    14.1 3345.13    43.8 3330.18    56.5 3322.18      73 3315.25
    87.7 3306.01     114 3291.55   127.3  3285.1     133 3283.41   160.8 3281.76
   184.2 3283.64   195.9 3281.13   213.5 3281.12   220.7 3282.83   242.8 3280.59
     266 3279.78   353.4 3281.69     365 3280.73   383.2 3275.83   396.1  3277.4
   402.7 3275.96   412.5 3275.81   438.6 3276.02  448.98 3277.39     474 3281.27
   476.9 3282.89   488.6 3293.72   501.4 3301.36   543.3 3321.28   630.5 3357.44
#Mann= 5 ,-1,0
       0      .1       0     110     .06       0     260      .1       0
   396.1    .045       0  448.98     .12       0
Bank Sta=396.1,448.98
XS Rating Curve= 0 ,0
Exp/Cntr=0.3,0.1

Type RM Length L Ch R = 1 ,59169   ,511.4,511.4,511.4
XS GIS Cut Line= 2
2366939.40466629635715.5686415742367411.54036103636157.197106807
#Sta/Elev= 30
       0 3344.66     8.2 3339.71    52.6  3318.3   142.9 3281.39   148.7 3279.89
     197 3278.09   213.2 3276.25   250.7 3277.99   277.6 3276.83   290.3 3278.29
   338.5 3277.28   395.4 3278.43   409.2 3276.21   423.4 3276.32  433.183274.826
   455.7 3273.04   471.5 3273.37   477.1 3274.83   482.5 3276.86     494 3277.62
   500.1 3281.98   510.4 3287.02   546.9 3299.23   564.5 3306.93   570.7 3307.79
   576.2 3310.27   587.9 3318.28   604.5 3323.63     620 3331.29   646.5 3344.46
#Mann= 5 ,-1,0
       0      .1       0     190     .06       0  433.18    .045       0
   477.1     .12       0     620      .1       0
Bank Sta=433.18,477.1
XS Rating Curve= 0 ,0
Exp/Cntr(USF)=0,0
Exp/Cntr=0.3,0.1

Type RM Length L Ch R = 1 ,58657   ,727,727,727
XS GIS Cut Line= 3
2366481.57355071636134.2074010982367014.02840087 636449.51469573
2367121.32013538636472.145488064
#Sta/Elev= 30
       0 3315.26      17 3314.22    44.9 3309.76    77.4 3306.34   133.2 3302.52
   184.3 3293.65   263.4 3288.54   281.9 3289.34   287.3 3288.07   300.5 3276.93
   309.8 3271.95     361 3270.96   384.2 3273.18   393.5  3271.4   418.7 3272.59
   458.6 3271.58   477.2 3272.83   486.5 3272.36  493.513270.292   505.1 3268.92
  531.083270.274   542.3  3271.1   563.2 3268.67   574.8 3268.98   593.4  3271.6
   614.3 3288.01   629.2 3295.35   653.7 3302.08   698.7  3318.6   728.5 3333.41
#Mann= 5 ,-1,0
       0      .1       0     350     .06       0     470      .1       0
  493.51    .045       0  531.08      .1       0
Bank Sta=493.51,531.08
XS Rating Curve= 0 ,0
Exp/Cntr=0.3,0.1

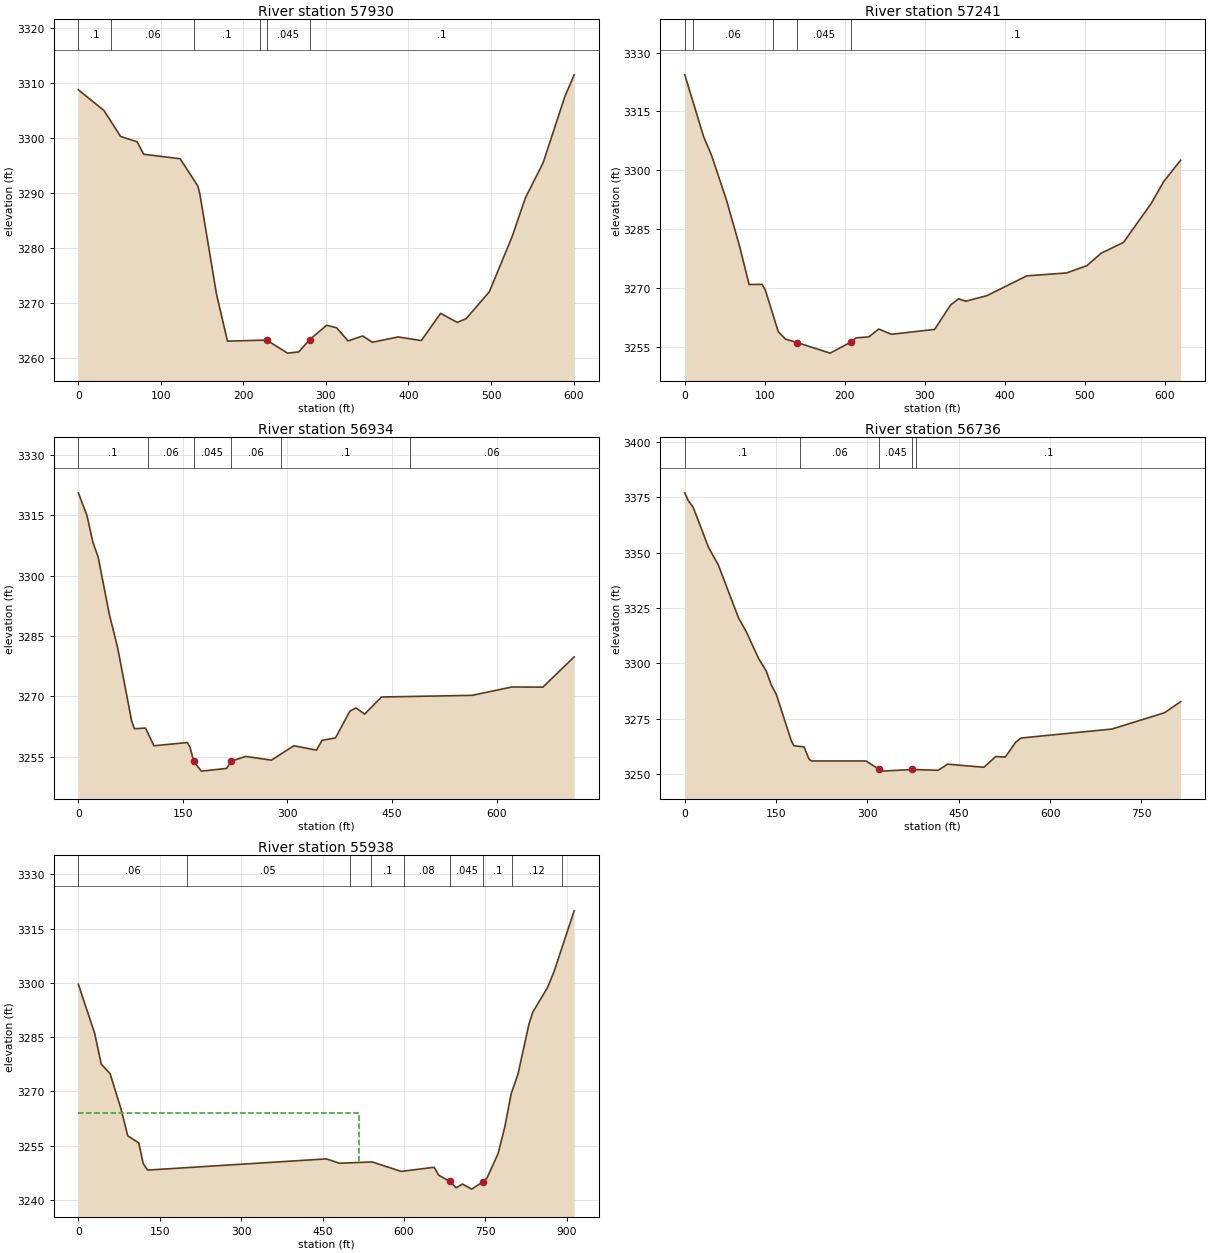
Type RM Length L Ch R = 1 ,57930   ,689.4,689.4,689.4
XS GIS Cut Line= 4
2366649.09754228637051.2743069332366818.27769769637041.109149519
2366932.31918877636979.8848594152367190.76765142636824.119743717
#Sta/Elev= 30
       0 3308.73    31.1 3304.96    51.2 3300.25    71.2 3299.28    79.2 3297.01
   123.3  3296.2   144.8 3291.24   147.3 3289.74   167.4 3271.58   180.7 3263.04
   228.23263.234   253.4 3260.86     267 3261.08   280.33263.326   300.8 3265.92
   312.8 3265.48   326.8 3263.08   344.5 3263.98   356.2 3262.84   387.5  3263.8
   415.5 3263.14   438.9 3268.09   459.1 3266.45   469.8 3267.12   497.9    3272
   525.2  3281.9   541.6 3289.06   563.1 3295.46   589.3 3307.45   600.7 3311.45
#Mann= 6 ,-1,0
       0      .1       0      40     .06       0     140      .1       0
  219.49    .025       0   228.2    .045       0   280.3      .1       0
Bank Sta=228.2,280.3
XS Rating Curve= 0 ,0
Exp/Cntr=0.3,0.1

Type RM Length L Ch R = 1 ,57241   ,306.4,306.4,306.4
XS GIS Cut Line= 4
2366972.72798389637647.8686919082367213.62347671637609.959419078
2367446.84179487637433.5983704612367507.47246568637375.963290825
#Sta/Elev= 30
       0 3324.34    23.7 3308.49    33.4 3303.87    52.1 3292.44    68.3 3280.82
    80.4 3270.93    96.6 3270.97   100.7 3269.51   116.9 3258.89   125.9 3257.02
   140.3 3256.15   181.7 3253.45   207.63256.245     214 3257.34   230.2 3257.59
   242.4 3259.59   258.4 3258.25   312.3 3259.49   332.3 3265.71   342.3 3267.29
   351.3 3266.67   377.8 3268.09   427.6 3273.13   477.5 3273.88   502.8 3275.74
   520.4 3278.88   548.5 3281.66   582.8 3291.47   598.8 3297.16   619.9 3302.58
#Mann= 5 ,-1,0
       0      .1       0      10     .06       0     110      .1       0
   140.3    .045       0   207.6      .1       0
Bank Sta=140.3,207.6
XS Rating Curve= 0 ,0
Exp/Cntr=0.3,0.1

Type RM Length L Ch R = 1 ,56934   ,198.8,198.8,198.8
XS GIS Cut Line= 4
2366983.82685355637922.0755129212367134.50692686637919.916309412
2367289.19346534 637934.911433042367688.28889925637864.853238314
#Sta/Elev= 30
       0 3320.56    12.3 3314.98    20.9 3308.29    28.4 3304.63    44.4 3290.43
    56.4 3282.09    76.4 3263.99    80.4 3261.98    96.4 3262.14   108.4 3257.75
   156.4 3258.55   160.4 3257.31  165.33  3253.9   176.5 3251.45   212.7 3252.12
   219.3 3253.91   240.1  3255.1     277 3254.17   309.1 3257.75   341.6 3256.67
   349.7  3259.1   368.9 3259.69   389.6 3266.37   398.5 3267.14   410.7  3265.6
     435 3269.86     565 3270.27   621.8 3272.34   666.5 3272.32   711.3 3279.81
#Mann= 6 ,-1,0
       0      .1       0     100     .06       0  165.33    .045       0
   219.3     .06       0   290.7      .1       0  476.11     .06       0
Bank Sta=165.33,219.3
XS Rating Curve= 0 ,0
Exp/Cntr=0.3,0.1

Type RM Length L Ch R = 1 ,56736   ,797.8,797.8,797.8
XS GIS Cut Line= 3
2366894.86625276638199.690648093   2367336.09829638082.855524772
2367664.31270478  637940.2274575
#Sta/Elev= 30
       0 3376.92     5.5 3373.48    13.8 3370.38    39.1 3352.23    55.1 3344.37
    88.2 3320.54   100.7 3314.44   120.9 3302.37   133.8 3296.48     142 3290.28
   150.3    3286   175.1 3264.93   179.3 3262.84   195.8 3262.34   204.1 3256.78
   208.2 3255.98   297.6 3255.98  319.47 3252.15   324.1  3251.4   373.8 3252.14
   416.1 3251.78   431.7 3254.53   491.2 3253.14   510.8    3258   526.3 3257.74
   543.7 3264.51   552.5 3266.34   701.5 3270.38     788 3277.75   814.3 3282.73
#Mann= 5 ,-1,0
       0      .1       0     190     .06       0  319.47    .045       0
   373.8     .06       0     380      .1       0
Bank Sta=319.47,373.8
XS Rating Curve= 0 ,0
Exp/Cntr=0.3,0.1

Type RM Length L Ch R = 1 ,55938   ,413.8,413.8,413.8
XS GIS Cut Line= 3
2367572.79285985638886.867785006 2367718.0653813638068.983489197
2367792.15436725638031.212633618
#Sta/Elev= 30
       0 3299.63    30.2 3285.99    42.3 3277.53    58.6 3274.89    78.9 3265.02
    91.1 3257.74   111.4 3255.78   119.5 3250.11   127.7 3248.26   457.3 3251.36
   481.1 3250.15   541.3 3250.52   594.9  3247.9   655.8 3249.04   663.9 3246.87
   684.6 3245.13   696.4 3243.38   708.1  3244.4   724.9    3243   746.1 3245.04
   753.3 3246.12   773.7 3252.84   785.8 3260.06   797.8 3269.41   810.2 3274.72
   830.5  3288.6   837.5 3291.89   864.8 3298.72   876.7 3303.08   913.8  3319.9
#Mann= 9 ,-1,0
       0     .06       0     200     .05       0     500     .08       0
     540      .1       0     600     .08       0   684.6    .045       0
   746.1      .1       0     800     .12       0  890.69      .1       0
#XS Ineff= 2 , 0
           517.3 3264.06
Permanent Ineff=
       F       F
Bank Sta=684.6,746.1
XS Rating Curve= 0 ,0
Exp/Cntr(USF)=0,0
Exp/Cntr=0.3,0.1