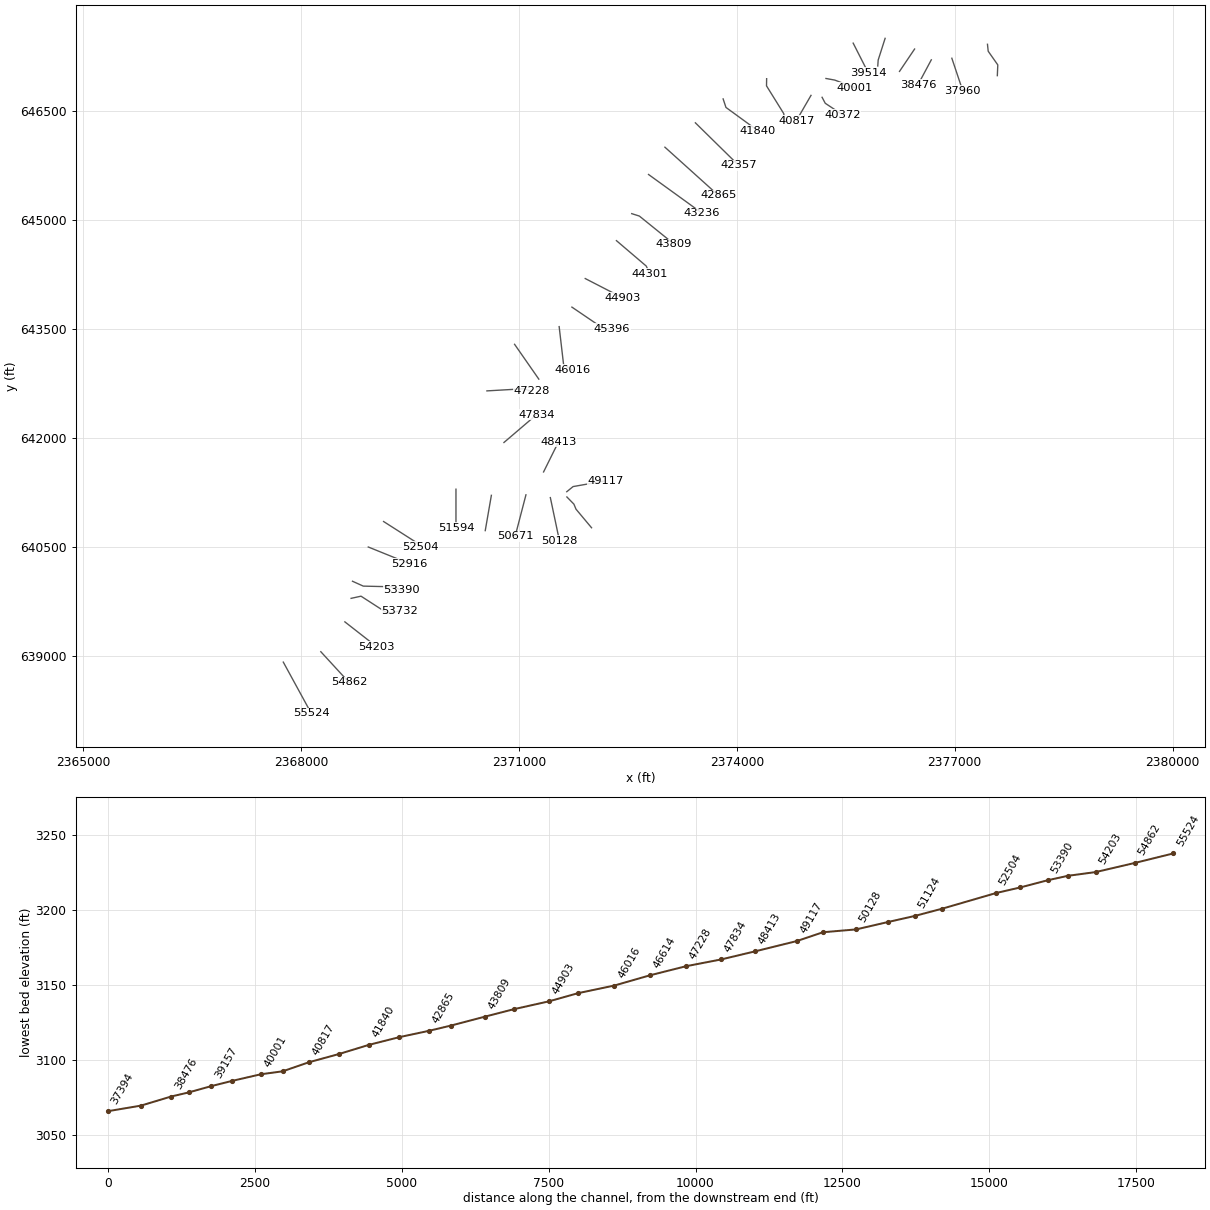
HEC-RAS study GNDYCK_1.prj: GNDYCK_1

--- GNDYCK_1.g01 (geometry) --- (continued)

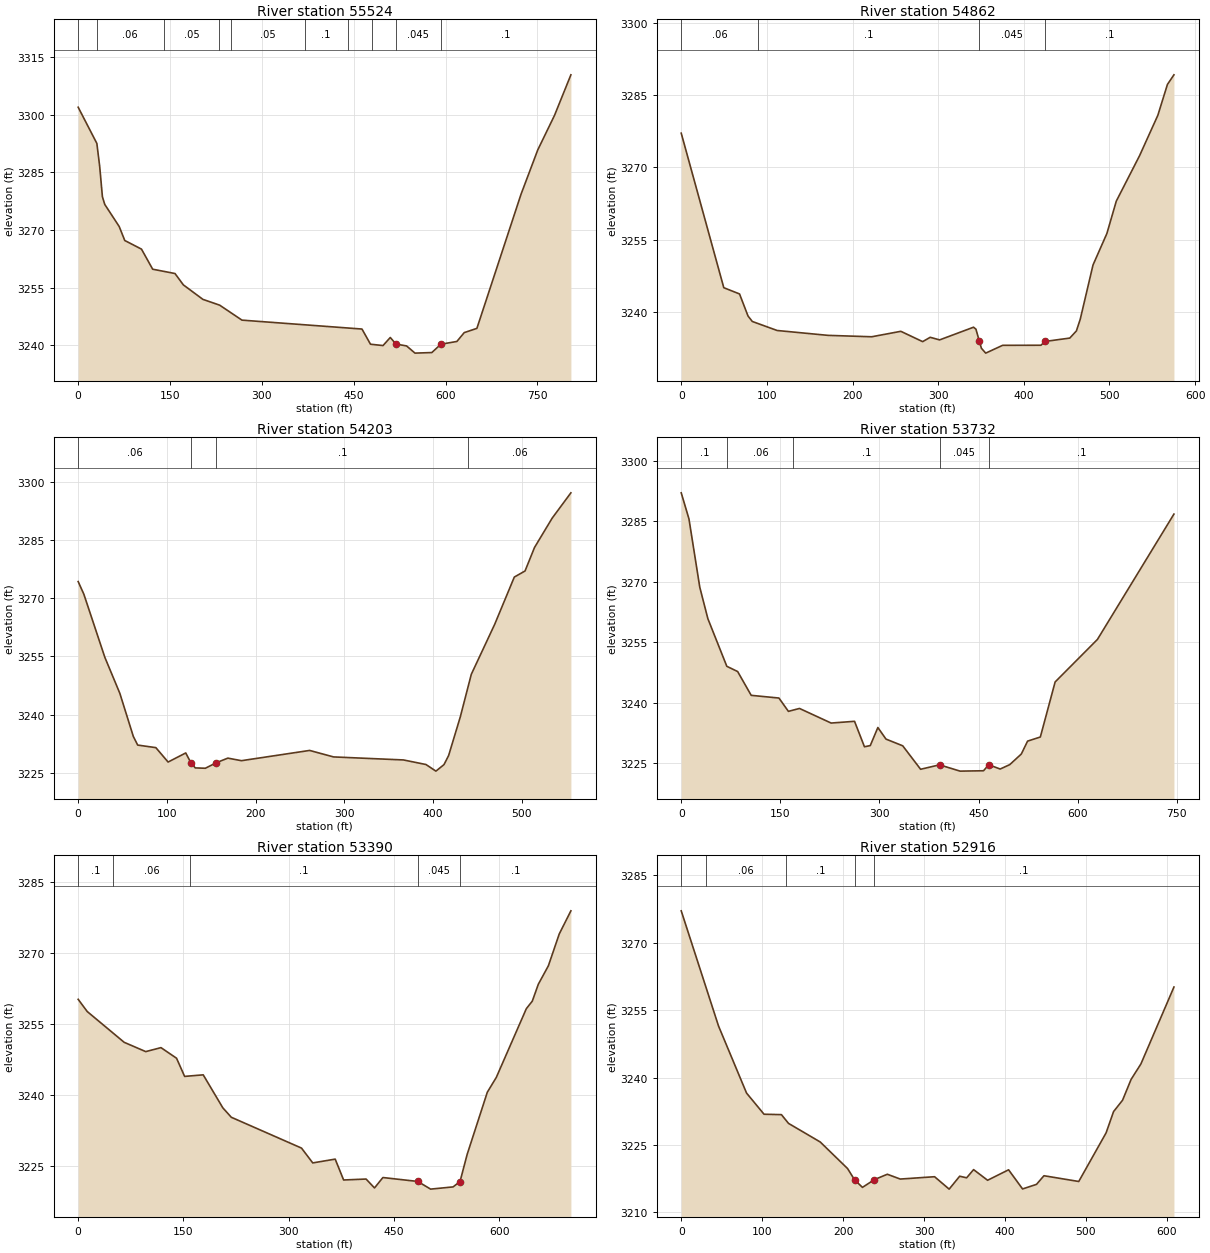
Type RM Length L Ch R = 1 ,55524   ,662.1,662.1,662.1
XS GIS Cut Line= 2
2367755.35560392638911.970584512 2368141.0449083 638205.70565209
#Sta/Elev= 30
       0 3301.95    30.5 3292.53    35.1  3286.6    39.6 3278.63    43.4 3276.65
      67 3270.89    76.1 3267.25   103.4    3265   121.7 3259.77   158.1 3258.65
   171.8 3255.69   203.7 3251.92   231.1 3250.41   267.5 3246.51   463.5 3244.19
   477.4 3240.24   497.9 3239.89   509.7 3241.99   519.1 3240.28   536.4 3239.79
   550.1 3237.92   577.6 3238.07  592.293240.235   618.5 3240.96   630.5 3243.26
   651.2 3244.37   723.3 3279.31   750.6 3290.84     778 3299.85   804.7 3310.39
#Mann= 10 ,-1,0
       0      .1       0      30     .06       0     140     .05       0
     230     .06       0     250     .05       0     370      .1       0
     440     .05       0     480      .1       0   519.1    .045       0
  592.29      .1       0
Bank Sta=519.1,592.29
XS Rating Curve= 0 ,0
Exp/Cntr=0.3,0.1

Type RM Length L Ch R = 1 ,54862   ,659,659,659
XS GIS Cut Line= 2
2368272.05399993639055.3046521572368661.20773903638631.627521775
#Sta/Elev= 30
       0 3277.09    49.7 3245.07    68.1 3243.77      78  3239.2      83 3238.07
     112  3236.2   171.4 3235.19   222.4  3234.9   256.4 3236.03   281.9 3233.89
   290.7 3234.79   301.7 3234.25   341.3 3236.88   344.1 3236.48  348.033234.015
   350.5 3232.52   355.5 3231.51   375.3 3233.13     420 3233.14  424.853233.932
   453.7 3234.63   461.4 3236.11   465.9 3238.53   480.8 3249.77     497  3256.3
     508 3263.01   535.2 3272.44   556.5 3280.79   567.7 3287.19   575.3 3289.18
#Mann= 4 ,-1,0
       0     .06       0      90      .1       0  348.03    .045       0
  424.85      .1       0
Bank Sta=348.03,424.85
XS Rating Curve= 0 ,0
Exp/Cntr=0.3,0.1

Type RM Length L Ch R = 1 ,54203   ,471.1,471.1,471.1
XS GIS Cut Line= 2
2368603.16018368639466.4847793112369040.91574943639124.284113403
#Sta/Elev= 30
       0  3274.3     6.4 3271.05    30.1 3254.77      47  3245.5    62.2  3234.4
    67.1 3232.18    87.6 3231.52   101.4 3227.81   121.3 3230.15  127.04 3227.65
     132  3226.3   143.4 3226.21  155.75 3227.63   168.8 3228.82   184.1 3228.16
     261  3230.8   287.9 3229.13   366.8 3228.35   392.2 3227.17   403.4 3225.47
   412.5 3227.15   417.7 3229.47   430.8 3239.37   443.3 3250.41   469.7  3263.3
   491.8 3275.46   503.9 3277.03   514.6 3283.09   534.5 3290.64   555.6 3297.16
#Mann= 4 ,-1,0
       0     .06       0  127.04    .045       0  155.75      .1       0
     440     .06       0
Bank Sta=127.04,155.75
XS Rating Curve= 0 ,0
Exp/Cntr=0.3,0.1

Type RM Length L Ch R = 1 ,53732   ,341.5,341.5,341.5
XS GIS Cut Line= 4
2368688.77352177 639790.416739282368825.40821762639820.426695707
 2369193.0687784639582.7824021282369357.72400018 639616.24221755
#Sta/Elev= 30
       0 3291.99    11.7 3285.53    28.1 3268.57    40.3  3260.8      69 3248.98
    85.4 3247.68   105.9 3241.78   147.9 3241.11   162.2 3237.81     179 3238.53
   226.9 3234.91   262.3 3235.34   277.3 3229.03   286.1 3229.32   297.6  3233.8
   309.9 3230.93   335.2 3229.27   362.3 3223.45   390.9 3224.55     422 3222.99
   457.5 3223.08   465.4 3224.57   482.7 3223.51   497.2  3224.6   514.7 3227.23
   524.2 3230.43   543.5 3231.45   565.9  3245.1   629.9 3255.64   745.7 3286.72
#Mann= 5 ,-1,0
       0      .1       0      70     .06       0  169.89      .1       0
   390.9    .045       0   465.4      .1       0
Bank Sta=390.9,465.4
XS Rating Curve= 0 ,0
Exp/Cntr=0.3,0.1

Type RM Length L Ch R = 1 ,53390   ,474.3,474.3,474.3
XS GIS Cut Line= 4
2368708.37382218640026.0231844672368856.65221339639959.058749725
2369264.81638705639949.4924019052369387.58451741639903.255054107
#Sta/Elev= 30
       0 3260.17    12.9 3257.59    65.6 3251.08    96.3 3249.12     118 3249.96
   140.2 3247.72   151.7 3243.88   178.2 3244.21   206.2 3237.23   218.2 3235.25
   318.3 3228.73   334.3  3225.6   366.3  3226.4   378.3 3221.99   410.3 3222.19
   422.3 3220.31   434.3 3222.51     484 3221.68   502.3 3220.06   534.3 3220.53
  544.213221.664   554.3 3227.37   583.1 3240.54   595.9 3243.67   638.7 3258.19
   647.2 3259.79   655.8 3263.36   670.1 3267.25   685.6 3273.98   702.2 3278.87
#Mann= 5 ,-1,0
       0      .1       0      50     .06       0     160      .1       0
     484    .045       0  544.21      .1       0
Bank Sta=484,544.21
XS Rating Curve= 0 ,0
Exp/Cntr(USF)=0,0
Exp/Cntr=0.3,0.1

Type RM Length L Ch R = 1 ,52916   ,412.1,412.1,412.1
XS GIS Cut Line= 2
2368925.41095665640498.041391236 2369489.4918262640269.323043461
#Sta/Elev= 30
       0  3277.1    46.1 3251.47    80.7 3236.56   102.3 3231.85   123.8 3231.76
   132.5 3229.82   171.7 3225.68   205.5 3219.77  214.163217.261   223.9 3215.58
  238.623217.304   254.6  3218.5   270.6 3217.43     313 3217.95     331 3215.19
     344 3218.06   352.6 3217.71   361.2 3219.53   378.5 3217.16   404.4 3219.49
   421.7 3215.23   438.9 3216.25   448.1 3218.17   491.1 3216.89   524.9 3227.71
   534.1 3232.44   545.2 3234.96   555.8 3239.61   567.9 3243.04   608.7 3260.15
#Mann= 5 ,-1,0
       0      .1       0      30     .06       0     130      .1       0
  214.16    .045       0  238.62      .1       0
Bank Sta=214.16,238.62
XS Rating Curve= 0 ,0
Exp/Cntr=0.3,0.1

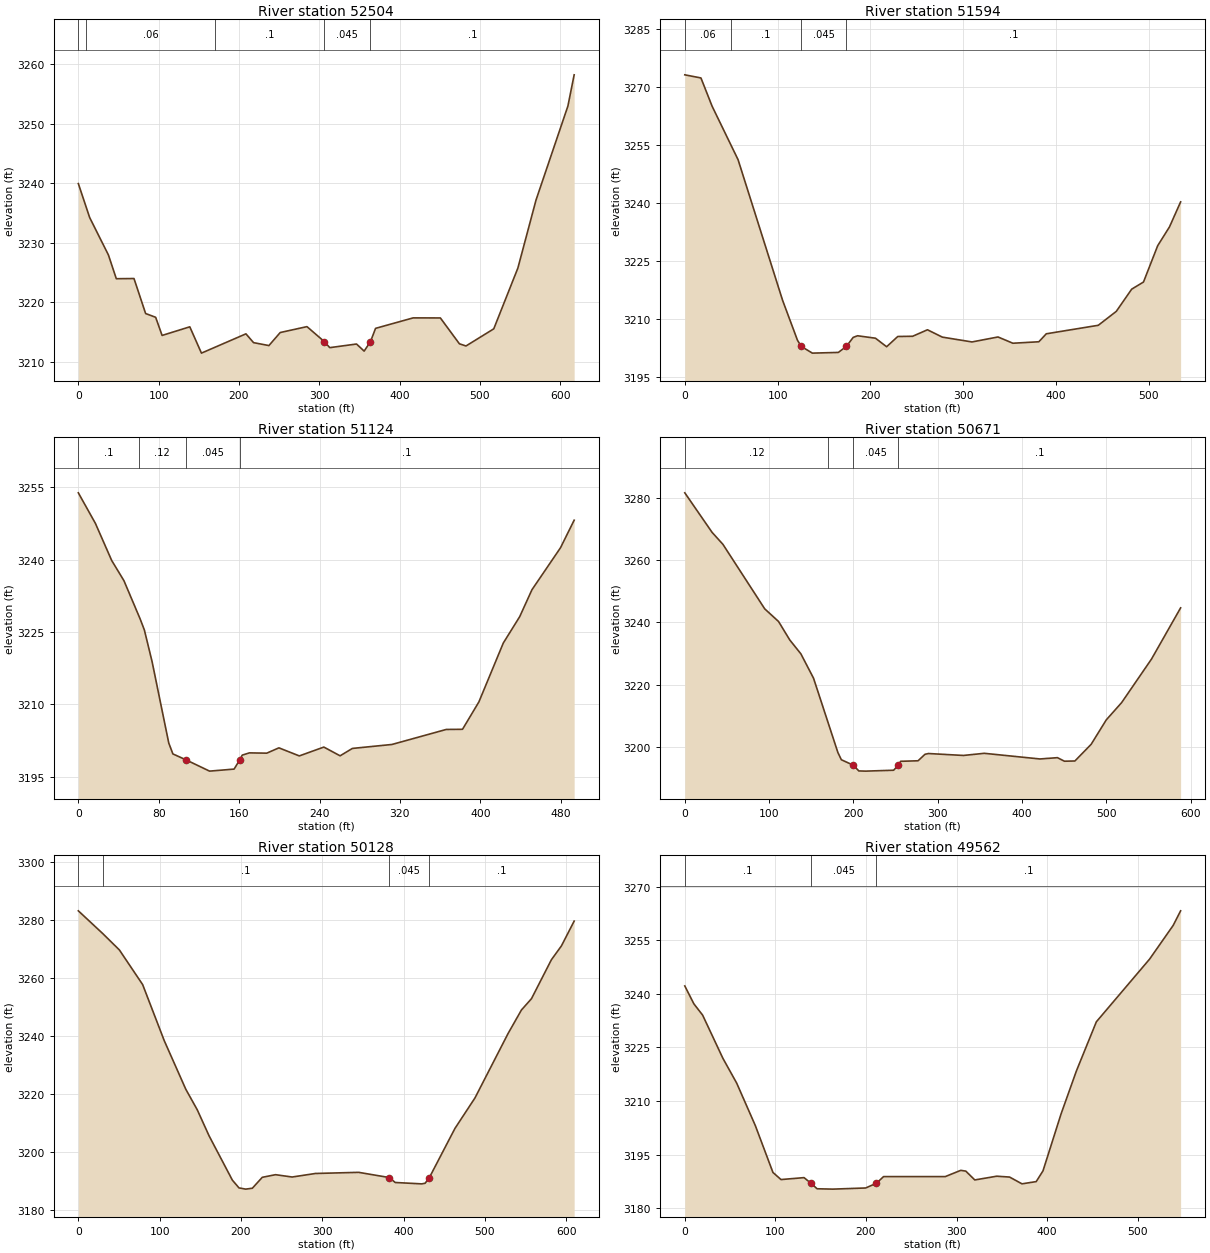
Type RM Length L Ch R = 1 ,52504   ,909.5,909.5,909.5
XS GIS Cut Line= 3
2369136.28713599 640849.043528182369589.45468518640559.514153247
2369645.68715492640503.184353086
#Sta/Elev= 30
       0 3239.93    14.1 3234.23    37.5 3227.93    47.3 3223.95    69.3 3223.98
    83.8  3218.1    96.3 3217.47   104.3 3214.42   138.8 3215.87   153.3 3211.45
   208.7 3214.69   218.2 3213.21   237.3 3212.72   251.4 3214.91   284.7  3215.9
  306.243213.395   313.1 3212.37   346.4 3212.98   355.9 3211.79   363.8 3213.38
   370.1 3215.61   416.9 3217.37   450.8 3217.36   474.5 3213.02   482.7 3212.65
   517.3 3215.53   547.3 3225.73   569.9 3237.16   609.6 3252.95   617.4  3258.2
#Mann= 5 ,-1,0
       0      .1       0      10     .06       0     170      .1       0
  306.24    .045       0   363.8      .1       0
Bank Sta=306.24,363.8
XS Rating Curve= 0 ,0
Exp/Cntr=0.3,0.1

Type RM Length L Ch R = 1 ,51594   ,470.1,470.1,470.1
XS GIS Cut Line= 2
2370132.86581909641294.5961604162370132.82937324640760.545808445
#Sta/Elev= 30
       0 3273.07    17.4 3272.26    29.4 3264.96    57.4 3251.11   105.4  3214.7
   121.4  3204.4   125.4 3202.83   137.4 3201.08   165.4 3201.26   174.1 3202.83
   181.4 3205.15   186.1 3205.57   205.4 3204.94   217.4 3202.73   229.4 3205.38
   245.4 3205.44   261.4 3207.12   277.4 3205.22   309.4 3203.97   337.4 3205.26
   353.4 3203.64   381.4 3204.02   389.4 3206.08   445.4 3208.28   464.8 3211.88
   481.4 3217.63   494.1 3219.47   509.4 3228.87   522.1 3233.73   534.1  3240.2
#Mann= 4 ,-1,0
       0     .06       0      50      .1       0   125.4    .045       0
   174.1      .1       0
Bank Sta=125.4,174.1
XS Rating Curve= 0 ,0
Exp/Cntr=0.3,0.1

Type RM Length L Ch R = 1 ,51124   ,452.8,452.8,452.8
XS GIS Cut Line= 2
2370620.28586966641209.8891255192370535.93559431640723.752111061
#Sta/Elev= 30
       0 3253.82      17 3247.49    33.2 3239.81    45.4 3235.62    61.6 3227.66
    65.7 3225.43    73.4 3218.86      90    3202    94.1 3199.75  107.163198.524
   130.6 3196.19     155 3196.61  160.643198.526   163.1  3199.5   170.2 3199.97
   187.5 3199.91   199.6 3201.01   219.9 3199.34   244.3 3201.17   260.5 3199.36
   272.7 3200.89   312.1 3201.71   366.1 3204.82   382.3 3204.85   398.6 3210.52
   422.9 3222.72   439.2 3228.17   451.4 3233.75   479.8 3242.44   493.4 3248.15
#Mann= 4 ,-1,0
       0      .1       0      60     .12       0  107.16    .045       0
  160.64      .1       0
Bank Sta=107.16,160.64
XS Rating Curve= 0 ,0
Exp/Cntr=0.3,0.1

Type RM Length L Ch R = 1 ,50671   ,543.5,543.5,543.5
XS GIS Cut Line= 2
2371096.35213345641216.916658913 2370948.1547128 640647.80348728
#Sta/Elev= 30
       0 3281.69    32.4 3268.96    45.2 3265.13    94.8 3244.37   111.2  3240.3
   124.5 3234.37   137.7 3229.89   152.7 3222.06   181.6 3198.14   185.7 3195.83
     200 3194.06   206.4 3192.23   214.7 3192.17   247.7 3192.46  253.13 3194.06
     256 3195.33   276.7  3195.5   284.9 3197.59   289.1 3197.83   330.4 3197.21
   355.2  3197.9   421.3 3196.08     442  3196.5   450.3 3195.36   462.7 3195.43
     482  3200.8   499.9 3208.65   518.1  3214.2   553.6 3228.23   588.1 3244.69
#Mann= 4 ,-1,0
       0     .12       0     170      .1       0     200    .045       0
  253.13      .1       0
Bank Sta=200,253.13
XS Rating Curve= 0 ,0
Exp/Cntr(USF)=0,0
Exp/Cntr=0.3,0.1

Type RM Length L Ch R = 1 ,50128   ,566.1,566.1,566.1
XS GIS Cut Line= 2
2371432.30067558641178.5766998112371557.99616516640581.750889849
#Sta/Elev= 30
       0 3283.25      30 3275.41    50.5 3269.75    79.1 3257.81   105.7 3238.44
   132.2 3221.68   146.3 3214.59   160.9 3205.57   189.5 3190.31   197.6 3187.65
   205.8 3187.22     214 3187.52   226.3  3191.3   242.6  3192.2     263  3191.4
   291.7 3192.62   344.8 3193.01   382.6 3191.21   389.8 3189.51   422.5 3189.03
   426.6 3189.25   431.8 3191.21   463.3 3208.18   487.9 3218.69   528.7 3240.96
   545.1 3249.05   557.4 3252.93   581.9 3266.37   594.2 3271.13   609.9  3279.7
#Mann= 4 ,-1,0
       0     .12       0      30      .1       0   382.6    .045       0
   431.8      .1       0
Bank Sta=382.6,431.8
XS Rating Curve= 0 ,0
Exp/Cntr=0.3,0.1

Type RM Length L Ch R = 1 ,49562   ,444.6,444.6,444.6
XS GIS Cut Line= 4
2371660.17151265641187.2982380092371756.67316519641088.498164308
2371785.28301118641019.3905528982371999.80942761640762.933972851
#Sta/Elev= 30
       0 3242.22      10 3237.22    19.7 3234.04    42.1 3221.93    57.3 3214.99
    77.9 3203.08    97.3 3189.98   106.2 3187.99   131.6 3188.53  139.33 3186.95
     146 3185.41   163.3 3185.31   199.6 3185.63   211.6 3186.96   219.4 3188.82
   287.5 3188.82   304.6 3190.57   310.2 3190.35   320.1 3187.88   344.3 3188.93
   358.5 3188.69   372.2 3186.79   387.9 3187.42   395.4 3190.44   415.3 3206.35
   432.3 3218.44   454.3 3232.18     513 3249.72   539.1 3259.18   547.3 3263.26
#Mann= 3 ,0,0
       0      .1       0  139.33    .045       0   211.6      .1       0
Bank Sta=139.33,211.6
XS Rating Curve= 0 ,0
Exp/Cntr=0.3,0.1

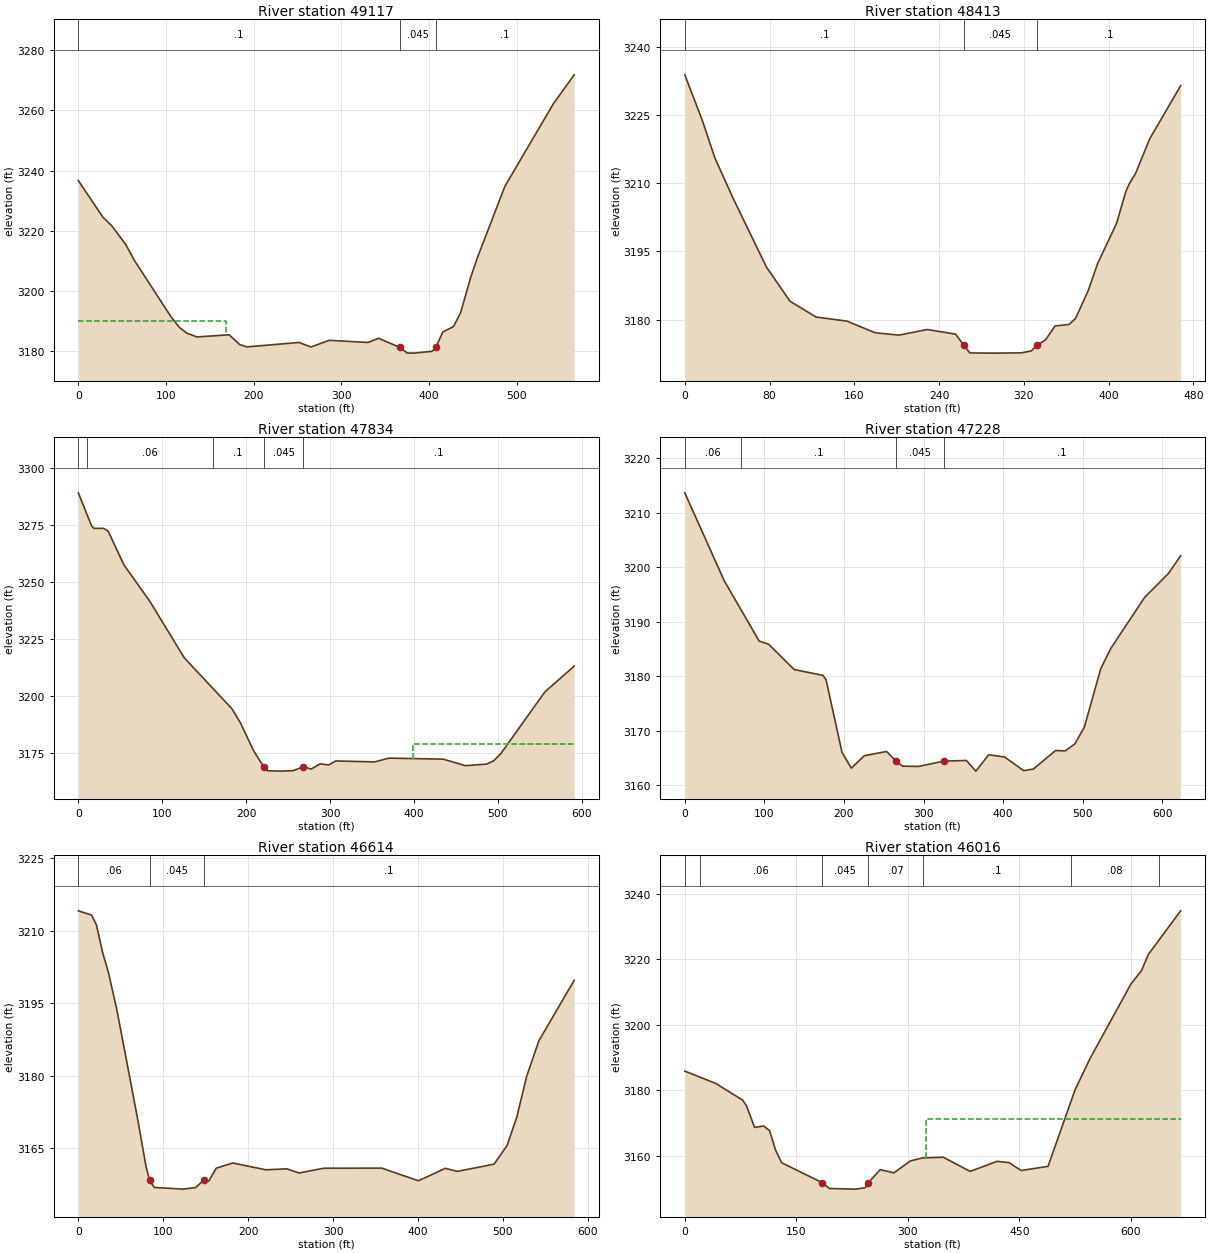
Type RM Length L Ch R = 1 ,49117   ,703.9,703.9,703.9
XS GIS Cut Line= 3
2371658.39094643641259.6025838622371745.19669517641330.464419568
2372191.68970514641409.271787515
#Sta/Elev= 30
       0 3236.71      28 3224.57    38.4 3221.62    53.9 3215.56    64.3 3210.05
   105.6 3191.55   115.1 3188.02   123.9 3186.03   135.4  3184.8   171.9 3185.53
   184.1 3182.27   192.3  3181.5   251.6 3182.97   265.4 3181.47   286.1 3183.68
   330.4 3182.97   342.5 3184.36   366.9  3181.3     375 3179.46   382.8 3179.43
   403.5 3180.03  407.733181.318   415.7 3186.45   427.8 3188.22     436 3192.86
   447.8 3204.86   455.3 3211.21   486.4 3234.75   541.6 3262.11   565.5 3271.81
#Mann= 3 ,-1,0
       0      .1       0   366.9    .045       0  407.73      .1       0
#XS Ineff= 2 , 0
           167.9    3190
Permanent Ineff=
       F       F
Bank Sta=366.9,407.73
XS Rating Curve= 0 ,0
Exp/Cntr=0.3,0.1

Type RM Length L Ch R = 1 ,48413   ,579.9,579.9,579.9
XS GIS Cut Line= 2
2371339.04005323641532.2181161042371546.99960394641951.374589487
#Sta/Elev= 30
       0 3233.87    16.5 3223.86    28.4 3215.57    45.7 3206.64      77 3191.58
    99.3 3184.04   123.9 3180.56   152.9 3179.67   179.7  3177.1     202 3176.58
   228.8 3177.81   255.6  3176.8  263.383174.323     269 3172.66   291.3 3172.62
   317.6 3172.68     327 3173.11  332.183174.322   340.4 3175.53   349.4  3178.6
   362.6 3178.93   368.7 3180.24   380.6 3186.32   389.5 3192.28   407.5 3201.22
   416.3 3208.25   419.4 3209.88   425.3  3212.1   438.7 3219.78   467.9 3231.47
#Mann= 3 ,-1,0
       0      .1       0  263.38    .045       0  332.18      .1       0
Bank Sta=263.38,332.18
XS Rating Curve= 0 ,0
Exp/Cntr=0.3,0.1

Type RM Length L Ch R = 1 ,47834   ,605.6,605.6,605.6
XS GIS Cut Line= 2
 2370793.4045023641937.8118405252371242.70104819642321.796618178
#Sta/Elev= 30
       0 3289.24      10 3280.05    15.7 3274.81    18.5 3273.67      30 3273.68
    35.6 3272.43    54.4 3257.62    85.2 3241.68   126.3 3216.89   183.1 3194.54
   193.1 3188.44   208.9 3176.15  220.853169.164   225.6 3167.35   242.7  3167.2
   256.2 3167.42   268.2 3169.15   277.3 3168.09   288.4  3170.4   298.3 3169.89
   306.9 3171.66   353.3 3171.25   370.3 3172.91   435.1 3172.44   461.4 3169.58
   486.7 3170.29   495.2 3171.77   503.7 3174.91   556.1 3201.96     591 3213.22
#Mann= 5 ,-1,0
       0      .1       0      10     .06       0     160      .1       0
  220.85    .045       0   268.2      .1       0
#XS Ineff= 2 , 0
                           398.7            3179
Permanent Ineff=
       F       F
Bank Sta=220.85,268.2
XS Rating Curve= 0 ,0
Exp/Cntr=0.3,0.1

Type RM Length L Ch R = 1 ,47228   ,613.7,613.7,613.7
XS GIS Cut Line= 3
2370558.94522212642648.8927824732371070.47723658642678.340961224
2371174.55469573642640.470396055
#Sta/Elev= 30
       0 3213.63    49.3 3197.58    93.4 3186.45   105.4 3185.86   137.5 3181.22
   173.5 3180.17   177.5 3179.37   197.6 3166.03   209.3 3163.15   225.6 3165.43
   253.6  3166.2   265.7 3164.43   273.7 3163.51   293.7 3163.46  325.173164.422
   353.8 3164.56   365.8  3162.6   381.9  3165.6   401.9 3165.19   425.9 3162.69
     438 3162.98     466 3166.38     478 3166.31   490.2 3167.59   502.1 3170.66
   522.7 3181.36   535.5 3185.13     578 3194.48   607.8 3198.84   623.1 3202.09
#Mann= 4 ,-1,0
       0     .06       0      70      .1       0   265.7    .045       0
  325.17      .1       0
Bank Sta=265.7,325.17
XS Rating Curve= 0 ,0
Exp/Cntr=0.3,0.1

Type RM Length L Ch R = 1 ,46614   ,598.3,598.3,598.3
XS GIS Cut Line= 2
2370939.83342037643290.5953480882371273.37742519642811.081536254
#Sta/Elev= 30
       0 3214.16    15.6 3213.29    21.4 3211.22    28.6 3205.54    35.6 3201.31
    45.6 3193.49    70.2 3170.73    79.7 3161.26   83.913158.361    89.4 3156.88
   123.5 3156.53   138.2 3156.86   147.7  3158.4   153.6 3158.18   162.5 3160.87
     182 3161.94     221 3160.53   245.4 3160.74     260 3159.87   289.2 3160.86
   357.4 3160.88   400.7 3158.26   432.3 3160.83   446.7 3160.21   489.8 3161.71
     505 3165.55   516.5 3171.41     528  3179.8   542.6 3187.27   584.1 3199.76
#Mann= 3 ,-1,0
       0     .06       0   83.91    .045       0   147.7      .1       0
Bank Sta=83.91,147.7
XS Rating Curve= 0 ,0
Exp/Cntr=0.3,0.1

Type RM Length L Ch R = 1 ,46016   ,620.3,620.3,620.3
XS GIS Cut Line= 3
2371553.53053144643534.4230291382371614.54362322643010.780193432
2371732.89001446 642936.66656035
#Sta/Elev= 30
       0 3185.85    41.5  3182.1    77.8 3176.99    82.9 3175.27    93.9 3168.64
     106 3169.07     114 3167.67   122.1 3161.71   130.1 3157.86  185.113151.715
   194.6 3149.97   230.7 3149.78   242.9 3150.25  246.723151.715   262.8 3155.73
   281.2 3154.76   303.3 3158.39   319.4 3159.31   347.6 3159.53   383.8  3155.2
   420.1 3158.28   436.2 3157.88   452.3 3155.47   488.5 3156.74   524.8 3180.12
   545.3 3189.84   599.9 3212.44   614.1 3216.56   623.5 3221.56   666.8 3234.85
#Mann= 7 ,-1,0
       0      .1       0      20     .06       0  185.11    .045       0
  246.72     .07       0     320      .1       0     520     .08       0
  637.19     .07       0
#XS Ineff= 2 , 0
                          323.86         3171.13
Permanent Ineff=
       F       F
Bank Sta=185.11,246.72
XS Rating Curve= 0 ,0
Exp/Cntr=0.3,0.1

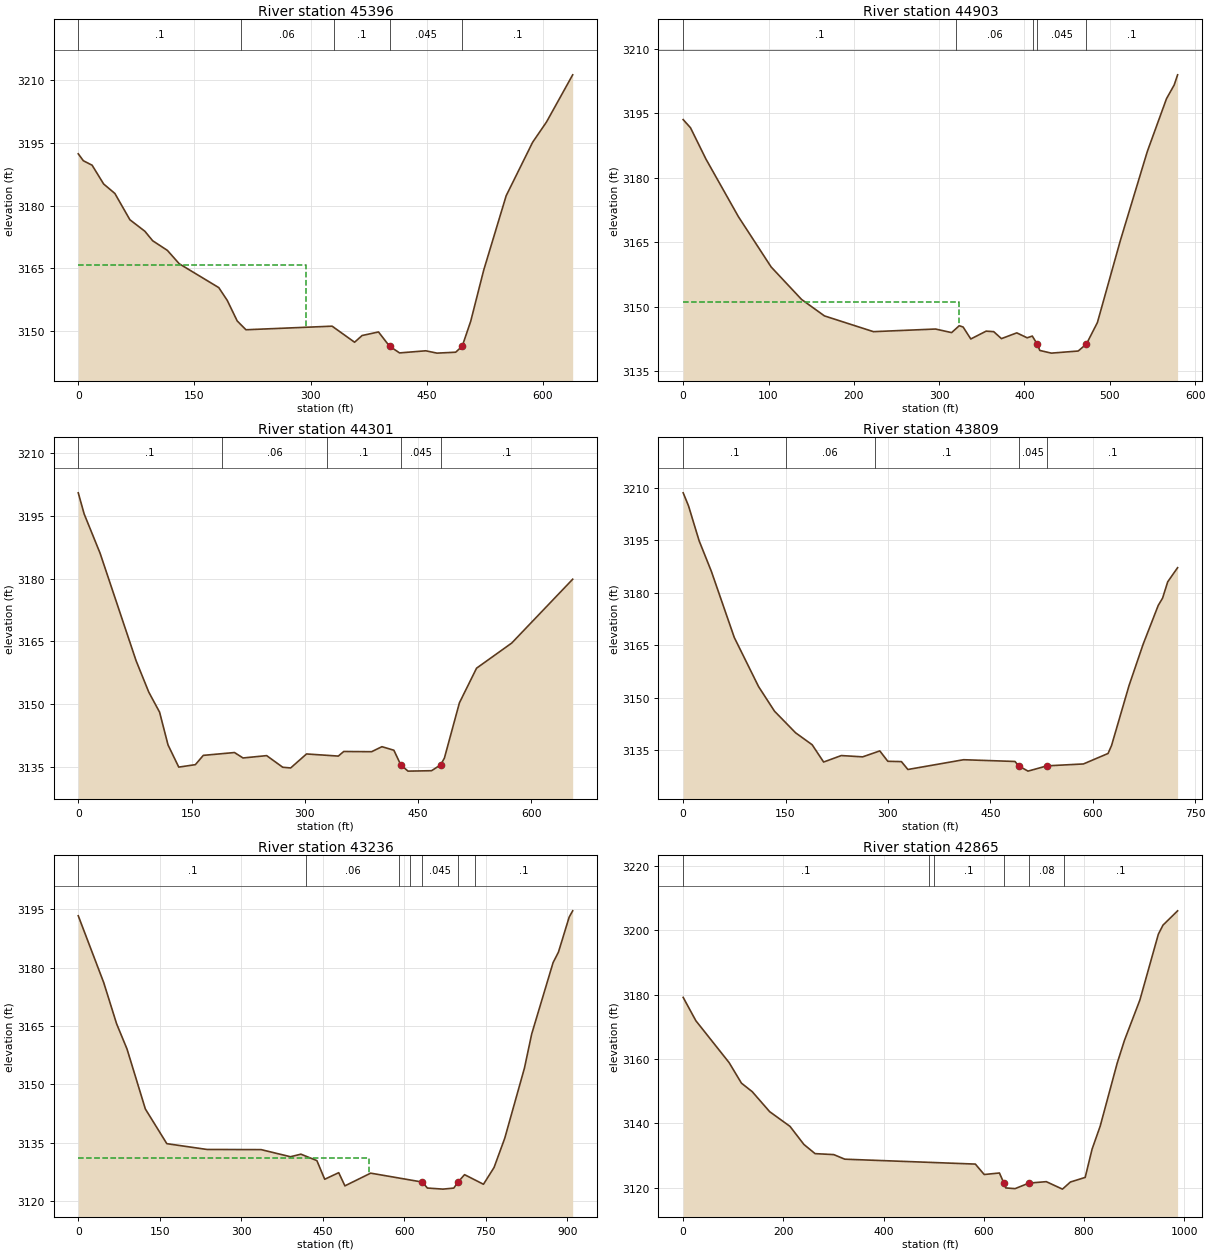
Type RM Length L Ch R = 1 ,45396   ,492.6,492.6,492.6
XS GIS Cut Line= 3
2371729.03336232643803.2434444692372156.18110624643512.738816429
2372277.80204359643503.390511936
#Sta/Elev= 30
       0 3192.42     6.6 3190.76    17.9 3189.69    32.8 3185.19    47.3 3182.92
    66.7 3176.62      86 3173.87    96.1 3171.59   115.1 3169.28   130.4 3166.08
   181.5 3160.36   192.5 3157.28   205.3 3152.37   216.6 3150.26   327.9 3151.12
   356.9 3147.27   366.6 3148.88   387.8 3149.73     402 3146.33     415 3144.71
   448.8 3145.22   463.4 3144.66   487.5 3144.88  495.943146.327   506.9  3152.3
   523.6 3164.49   552.7 3182.38   586.9  3195.2   604.8 3200.05   638.6 3211.35
#Mann= 5 ,-1,0
       0      .1       0     210     .06       0     330      .1       0
     402    .045       0  495.94      .1       0
#XS Ineff= 2 , 0
          294.54 3165.75
Permanent Ineff=
       F       F
Bank Sta=402,495.94
XS Rating Curve= 0 ,0
Exp/Cntr=0.3,0.1

Type RM Length L Ch R = 1 ,44903   ,601.8,601.8,601.8
XS GIS Cut Line= 2
2371912.55946375644196.6889178532372427.65274896643931.276579626
#Sta/Elev= 30
       0 3193.51     8.6 3191.61    26.6 3184.37    64.7 3170.96   103.1 3159.26
   138.7 3151.72   165.6 3147.88     223 3144.22   295.8 3144.83   314.6    3144
   323.6  3145.6   328.1  3145.3   337.1 3142.52   355.1 3144.34     364 3144.22
     373  3142.6     391 3143.94   403.2 3142.79   409.2  3143.2   414.93141.345
     418 3139.85   431.5 3139.23     463 3139.72  472.633141.344   485.5 3146.34
   512.5 3165.47     544  3186.1   566.5 3198.38   575.5 3201.56   579.5 3203.92
#Mann= 5 ,-1,0
       0      .1       0     320     .06       0     410      .1       0
   414.9    .045       0  472.63      .1       0
#XS Ineff= 2 , 0
           323.6    3151
Permanent Ineff=
       F       F
Bank Sta=414.9,472.63
XS Rating Curve= 0 ,0
Exp/Cntr=0.3,0.1

Type RM Length L Ch R = 1 ,44301   ,492.3,492.3,492.3
XS GIS Cut Line= 3
2372342.20762079 644718.892835692372752.71167533644368.629735262
2372799.92660119644263.563834552
#Sta/Elev= 30
       0 3200.56     7.8 3195.51    28.9 3186.11    76.6 3160.37    93.4 3152.86
   107.7 3148.07   118.9 3140.22   133.1 3134.91   155.1  3135.5   165.6 3137.72
   206.9  3138.4   218.2  3137.1   249.5 3137.66   270.8 3134.88   281.3 3134.71
   302.3 3138.06   344.4 3137.55   351.6 3138.65   388.5  3138.6   402.2  3139.8
     418 3138.95  427.19 3135.43   436.7 3133.95   467.9 3134.05   479.93135.447
   484.9 3137.06   504.8  3150.3   527.5 3158.59   574.1 3164.61   654.8 3179.88
#Mann= 5 ,-1,0
       0      .1       0     190     .06       0     330      .1       0
  427.19    .045       0   479.9      .1       0
Bank Sta=427.19,479.9
XS Rating Curve= 0 ,0
Exp/Cntr=0.3,0.1

Type RM Length L Ch R = 1 ,43809   ,572.3,572.3,572.3
XS GIS Cut Line= 3
2372552.77255071645091.0061303382372658.09156539645057.468907991
2373135.44613056644671.316410513
#Sta/Elev= 30
       0 3208.52     7.8 3204.81    23.3 3194.85    41.4 3186.02    74.9 3167.16
   110.5 3153.12   133.8  3146.1   164.7 3139.92     189  3136.5   205.8 3131.56
   231.7 3133.41     263 3133.04   288.1 3134.74   299.9 3131.77   319.8 3131.68
   329.3 3129.43   410.9 3132.22   486.2 3131.72  491.45 3130.48   505.3 3128.96
   533.2 3130.47   586.5 3131.01   622.6 3134.01   627.7 3136.28   653.4 3153.46
     674 3165.24   696.1 3176.32   702.5 3178.42     710 3183.08   724.5 3187.12
#Mann= 5 ,-1,0
       0      .1       0  150.53     .06       0  280.53      .1       0
  491.45    .045       0   533.2      .1       0
Bank Sta=491.45,533.2
XS Rating Curve= 0 ,0
Exp/Cntr=0.3,0.1

Type RM Length L Ch R = 1 ,43236   ,371.1,371.1,371.1
XS GIS Cut Line= 2
2372784.13552662645630.4854346082373521.42852662645097.101434608
#Sta/Elev= 30
       0 3193.37    46.8 3176.21    70.5 3165.62    89.8 3159.08   123.5 3143.68
     163 3134.76     237 3133.27   336.6 3133.23   390.6  3131.4   409.8 3132.06
   439.2  3130.4   453.6 3125.61   479.4  3127.3   490.8 3123.91   538.2 3127.18
  633.333124.885   642.6 3123.35   671.3 3123.07   691.2 3123.34  698.64 3124.85
     711 3126.79   745.8 3124.32   765.3 3128.64     785 3136.17   821.2 3154.19
   834.6 3162.99   873.9 3181.31   883.8 3184.02   903.5 3193.01     910 3194.64
#Mann= 7 ,-1,0
       0      .1       0     420     .06       0     590      .1       0
     610     .08       0  633.33    .045       0  698.64     .08       0
     730      .1       0
#XS Ineff= 2 , 0
          535.74 3131.12
Permanent Ineff=
       F       F
Bank Sta=633.33,698.64
XS Rating Curve= 0 ,0
Exp/Cntr=0.3,0.1

Type RM Length L Ch R = 1 ,42865   ,508.6,508.6,508.6
XS GIS Cut Line= 2
2373009.71012534646006.5087842132373742.97254252645345.635853784
#Sta/Elev= 30
       0 3179.15    25.3 3171.91    91.6 3158.91   116.4  3152.5   137.9 3149.86
   172.6 3143.66   213.3 3139.08     241 3133.47   263.3 3130.62   300.7 3130.31
   322.7 3128.89   583.3 3127.37     601 3124.13   631.4  3124.6  640.38 3121.42
   644.1 3119.96   662.6 3119.74   690.13121.461   724.9 3121.91   757.2 3119.59
   773.1  3121.8   802.6 3123.23   816.4 3132.03   832.5 3139.13   866.5 3158.73
   881.1 3165.85   911.8 3178.34   948.7 3198.79   957.9 3201.59   987.1 3206.04
#Mann= 6 ,-1,0
       0      .1       0     490     .06       0     500      .1       0
  640.38    .045       0   690.1     .08       0     760      .1       0
Bank Sta=640.38,690.1
XS Rating Curve= 0 ,0
Exp/Cntr=0.3,0.1

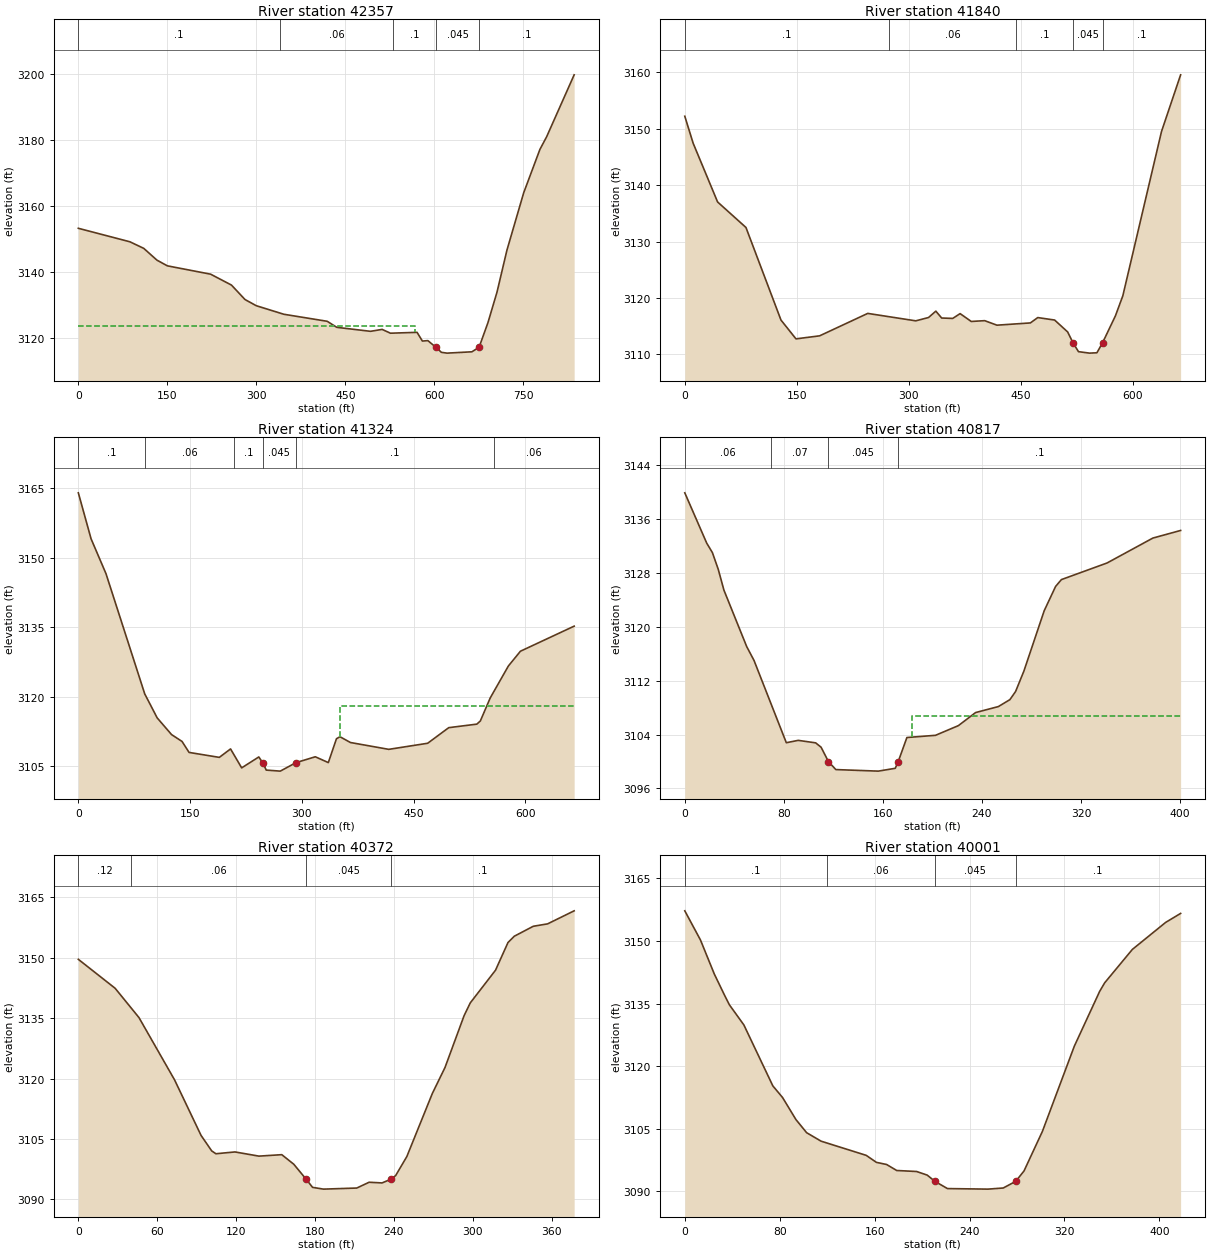
Type RM Length L Ch R = 1 ,42357   ,517.3,517.3,517.3
XS GIS Cut Line= 2
2373429.23494688646342.097620092 2374024.9054372645756.327470331
#Sta/Elev= 30
       0 3153.17    86.9 3149.08   110.2 3147.09   132.5 3143.51     150 3141.79
   222.9 3139.26     258 3135.96   280.8 3131.58   299.7 3129.71   346.3 3127.11
   419.3 3124.98   435.5 3123.15   492.2 3121.94   511.9 3122.52   525.9 3121.37
   570.7 3121.63   579.7 3118.99   588.9 3119.12   602.4 3117.12   611.7 3115.57
   621.2 3115.33   663.1 3115.73  675.24 3117.11   690.1 3124.54   705.4 3133.81
   722.2 3146.58   750.3 3163.89   777.7 3177.08   789.1 3180.94   835.4 3199.69
#Mann= 5 ,-1,0
       0      .1       0     340     .06       0     530      .1       0
   602.4    .045       0  675.24      .1       0
#XS Ineff= 2 , 0
          567.62 3123.64
Permanent Ineff=
       F       F
Bank Sta=602.4,675.24
XS Rating Curve= 0 ,0
Exp/Cntr(USF)=0,0
Exp/Cntr=0.3,0.1

Type RM Length L Ch R = 1 ,41840   ,515.6,515.6,515.6
XS GIS Cut Line= 3
2373811.21942171646671.7748781492373850.22780453646554.343478068
2374286.71893928646236.018773763
#Sta/Elev= 30
       0 3152.23    11.2 3147.44    43.9 3137.02    81.9 3132.49   128.8 3116.06
   148.9 3112.72   180.6 3113.26     245 3117.24   309.3 3115.92   326.4 3116.51
   336.2 3117.64     344 3116.42   358.8 3116.35   368.7  3117.2   383.6 3115.81
   401.6 3115.95     418 3115.15   462.8 3115.55   472.7  3116.5   495.3 3116.06
   512.7 3113.95  519.753112.062   527.2 3110.45     542 3110.19   551.9 3110.25
  559.593112.062   576.7 3116.81   586.6 3120.36   638.4 3149.52     664 3159.58
#Mann= 5 ,-1,0
       0      .1       0  273.74     .06       0  443.74      .1       0
  519.75    .045       0  559.59      .1       0
Bank Sta=519.75,559.59
XS Rating Curve= 0 ,0
Exp/Cntr=0.3,0.1

Type RM Length L Ch R = 1 ,41324   ,506.7,506.7,506.7
XS GIS Cut Line= 4
2374410.22958984646950.2940065492374408.53788987646851.394250776
2374645.36242421646470.1795692412374664.89919869646354.118258582
#Sta/Elev= 30
       0 3163.93    17.1 3154.03    37.1 3146.53    89.1 3120.64   105.8 3115.47
   125.1 3111.87   139.2 3110.39   148.6 3108.03   189.2 3106.96   204.3 3108.78
   219.2  3104.7   242.2 3107.05   247.5 3105.79   252.2 3104.22     271    3104
     292 3105.82     318 3107.09   335.5 3105.84   346.4 3110.97   351.1 3111.41
   365.2 3110.16   416.6 3108.69   468.8    3110   497.1 3113.36   534.8 3114.12
   539.5  3114.8   552.8 3119.77   577.1 3126.63   593.3 3129.82   665.4 3135.22
#Mann= 6 ,-1,0
       0      .1       0      90     .06       0  208.91      .1       0
   247.5    .045       0     292      .1       0   557.7     .06       0
#XS Ineff= 1 ,-1
   351.1 665.396    3118
Permanent Ineff=
       F
Bank Sta=247.5,292
XS Rating Curve= 0 ,0
Exp/Cntr=0.3,0.1

Type RM Length L Ch R = 1 ,40817   ,445.5,445.5,445.5
XS GIS Cut Line= 2
2375021.22729164646720.5149338752374820.80125172646373.785629449
#Sta/Elev= 30
       0 3139.91    17.7 3132.44    22.3 3131.03      27 3128.56    31.6 3125.46
      50 3117.07    55.9 3115.02      82 3102.79    91.6 3103.14   105.7 3102.77
   110.1 3102.12     1163099.995     122  3098.8   156.3 3098.57     170 3098.99
  172.413099.995   179.4 3103.56   202.5 3103.89     221 3105.33   234.9 3107.27
   253.3 3108.16   262.6 3109.19   267.2  3110.4   273.9 3113.43   290.3 3122.39
   299.5    3126   304.2 3127.02   341.1 3129.49   378.1 3133.19   400.5 3134.32
#Mann= 4 ,-1,0
       0     .06       0      70     .07       0     116    .045       0
  172.41      .1       0
#XS Ineff= 2 , 0
                          183.39         3106.79
Permanent Ineff=
       F       F
Bank Sta=116,172.41
XS Rating Curve= 0 ,0
Exp/Cntr=0.3,0.1

Type RM Length L Ch R = 1 ,40372   ,370.6,370.6,370.6
XS GIS Cut Line= 3
2375173.75939639646693.8929337762375217.38787479646611.411933441
2375454.13827167 646455.06285217
#Sta/Elev= 30
       0 3149.63      28 3142.43    46.1 3135.16    73.2 3119.66    93.3 3105.89
   101.4 3102.03   104.6 3101.32   119.1 3101.77   137.3 3100.73   154.7 3101.09
   163.8 3098.72  173.193095.008   178.1 3092.97   186.4 3092.53   211.7  3092.8
   221.1 3094.24   230.9 3094.07  237.833095.007   241.3 3095.91   249.8 3100.64
   269.2 3116.32   278.8 3122.75   293.3 3135.62     298  3138.8   317.2 3146.92
   326.7 3153.81   331.5 3155.37   345.9 3157.84   356.8 3158.44     377 3161.68
#Mann= 4 ,-1,0
       0     .12       0      40     .06       0  173.19    .045       0
  237.83      .1       0
Bank Sta=173.19,237.83
XS Rating Curve= 0 ,0
Exp/Cntr=0.3,0.1

Type RM Length L Ch R = 1 ,40001   ,487,487,487
XS GIS Cut Line= 3
2375227.15804339646953.1871306062375348.40534791646931.024956539
2375624.00539146646826.764391236
#Sta/Elev= 30
       0 3157.21    13.2 3150.23    24.9 3142.06    33.6 3136.94    37.6  3134.7
    49.8 3129.88    74.2 3115.29    82.4  3112.5    93.7 3107.21   102.7 3104.07
   114.9 3102.04   152.9 3098.65   161.5 3096.97   170.1 3096.46   178.6 3095.02
   195.4 3094.78   204.3 3093.92  210.813092.422   221.4 3090.69   255.6 3090.56
   268.4 3090.83  278.923092.424   285.9 3094.91   301.4 3104.38   328.3 3124.79
   349.7 3137.94   353.9 3139.97   377.2 3147.96   405.3 3154.44   417.9 3156.59
#Mann= 4 ,-1,0
       0      .1       0     120     .06       0  210.81    .045       0
  278.92      .1       0
Bank Sta=210.81,278.92
XS Rating Curve= 0 ,0
Exp/Cntr=0.3,0.1

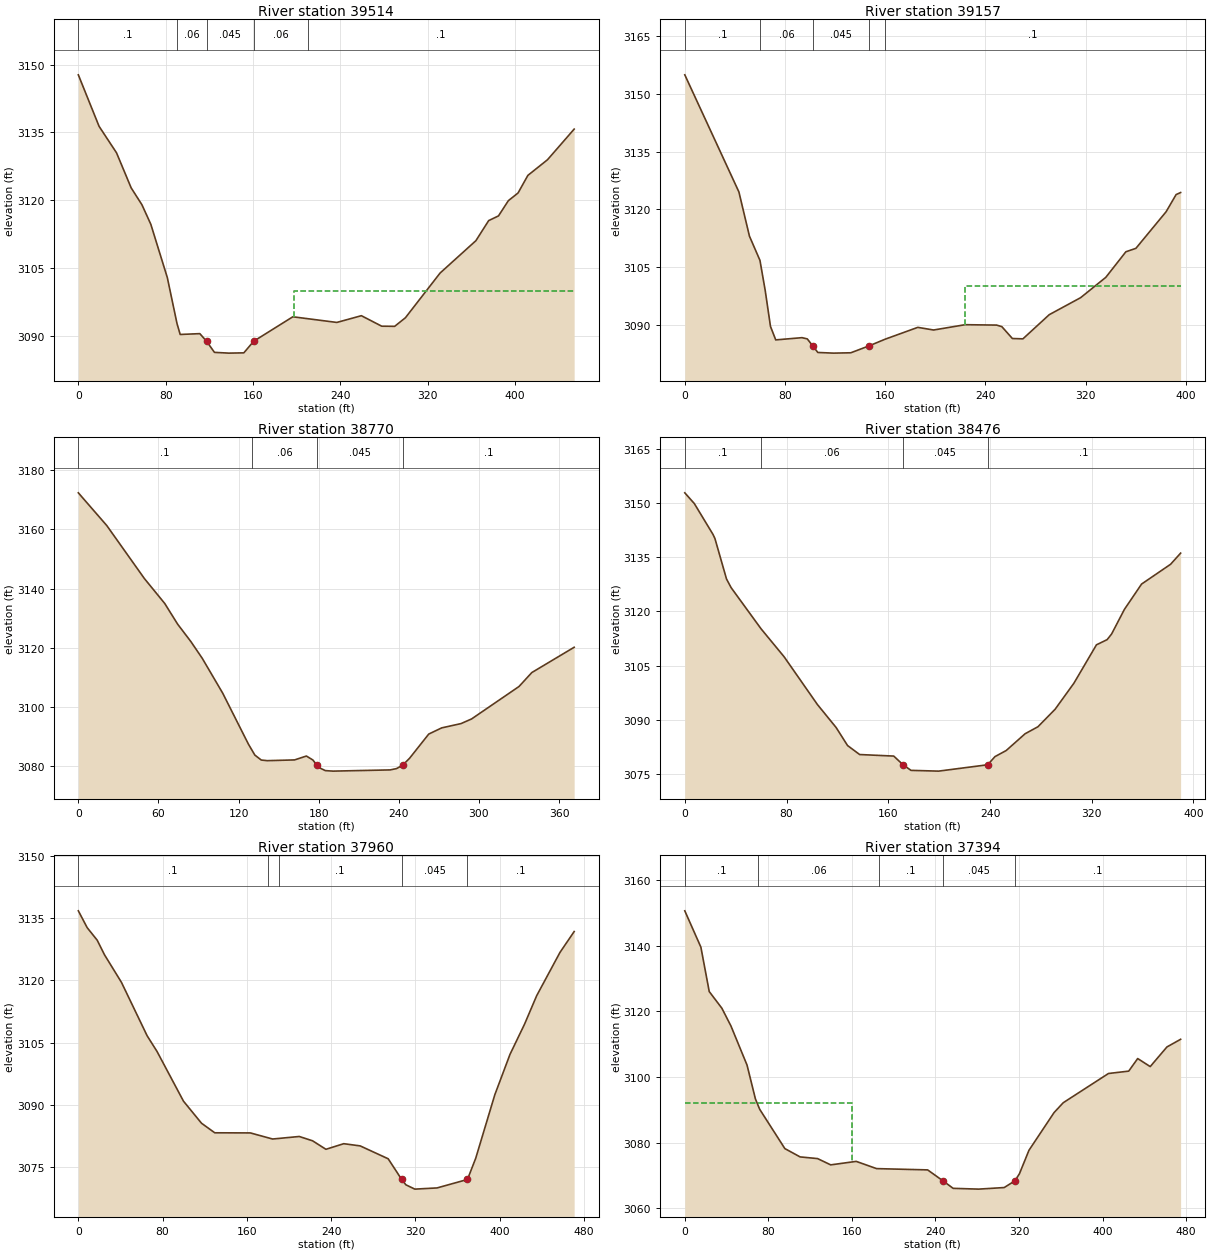
Type RM Length L Ch R = 1 ,39514   ,357.6,357.6,357.6
XS GIS Cut Line= 2
2375601.75961423647440.3461354522375807.43609237647035.370744394
#Sta/Elev= 30
       0 3147.73      19 3136.34      35 3130.47    48.4 3122.72    58.3 3118.97
    66.4 3114.67    81.5 3102.89    90.4  3092.7    93.3 3090.29   111.3 3090.47
  117.443088.793   124.7 3086.33   137.8 3086.16   151.6 3086.22  160.653088.792
   196.5  3094.2   236.8 3092.95   259.3 3094.44   277.9 3092.12   289.8 3092.09
   299.6 3093.98   331.4 3103.88   364.2 3111.04   375.9 3115.48   384.9 3116.52
   393.9 3119.88   402.8 3121.59   411.8 3125.48   429.8 3128.95   454.2 3135.72
#Mann= 5 ,-1,0
       0      .1       0      90     .06       0  117.44    .045       0
  160.65     .06       0     210      .1       0
#XS Ineff= 2 , 0
                           197.5            3100
Permanent Ineff=
       F       F
Bank Sta=117.44,160.65
XS Rating Curve= 0 ,0
Exp/Cntr(USF)=0,0
Exp/Cntr=0.3,0.1

Type RM Length L Ch R = 1 ,39157   ,386.4,386.4,386.4
XS GIS Cut Line= 3
2376041.59195634647506.3192173042375946.14813576647207.565005159
2375940.35534784647125.619086765
#Sta/Elev= 30
       0    3155    43.2 3124.55    51.6 3113.07      60 3106.76    64.2 3098.92
    68.4 3089.59    72.6 3086.09    93.6 3086.67    97.8 3086.34  102.213084.506
   106.2 3082.82   118.8 3082.65   132.5 3082.74  146.893084.507     160 3086.28
     186 3089.35   198.6 3088.66   223.8 3090.04   248.9 3089.94   253.1 3089.53
   261.5 3086.45   269.9 3086.36   290.9 3092.64     316 3097.07   336.1 3102.36
   352.1    3109   360.1 3109.89   384.2  3119.4   392.2 3123.87   395.8  3124.4
#Mann= 5 ,-1,0
       0      .1       0      60     .06       0  102.21    .045       0
  146.89     .06       0     160      .1       0
#XS Ineff= 2 , 0
                           223.8            3100
Permanent Ineff=
       F       F
Bank Sta=102.21,146.89
XS Rating Curve= 0 ,0
Exp/Cntr=0.3,0.1

Type RM Length L Ch R = 1 ,38770   ,293.9,293.9,293.9
XS GIS Cut Line= 2
2376447.25165218647358.8452175722376239.79782607 647050.85126101
#Sta/Elev= 30
       0 3172.31    21.3 3161.27    49.5 3143.37    64.7 3134.98    74.4 3127.98
    84.3 3122.11    92.8 3116.47   108.1 3104.73   127.4 3087.49   132.2 3083.82
     137 3082.15   141.5 3081.94   161.9 3082.19   170.8  3083.5   175.6 3082.18
  178.73  3080.4   180.5 3079.55     185 3078.58   190.7 3078.41   233.5 3078.82
   238.3 3079.27  242.833080.399     248 3082.72   262.4 3090.91   272.1    3093
   286.6 3094.45   294.5 3096.02     330 3106.96   339.6 3111.67   371.3  3120.2
#Mann= 4 ,-1,0
       0      .1       0     130     .06       0  178.73    .045       0
  242.83      .1       0
Bank Sta=178.73,242.83
XS Rating Curve= 0 ,0
Exp/Cntr=0.3,0.1

Type RM Length L Ch R = 1 ,38476   ,516.1,516.1,516.1
XS GIS Cut Line= 2
2376677.35413041647210.0999129222376493.56704342646866.206869417
#Sta/Elev= 30
       0 3152.87     7.5 3149.89    22.2 3141.33    23.7  3140.2    32.8 3128.99
    36.4  3126.6      60 3115.16    78.1 3107.42   104.3 3094.18     119 3087.81
     128 3082.81   137.5 3080.32   164.3 3079.89  171.633077.485   177.9 3075.93
   199.6 3075.72  238.193077.483   243.9 3079.74   252.7 3081.42   267.6 3086.08
   277.7 3088.02   291.2 3092.87     306  3100.1   323.7 3110.73   332.1 3112.17
   335.6 3113.72   345.7 3120.56   359.2 3127.58     382 3133.06   389.9 3136.15
#Mann= 4 ,-1,0
       0      .1       0      60     .06       0  171.63    .045       0
  238.19      .1       0
Bank Sta=171.63,238.19
XS Rating Curve= 0 ,0
Exp/Cntr=0.3,0.1

Type RM Length L Ch R = 1 ,37960   ,565.9,565.9,565.9
XS GIS Cut Line= 2
2376960.28834791647231.9849563382377109.86621748646785.774478091
#Sta/Elev= 30
       0 3136.77     8.4 3132.71    17.9 3129.69    24.8 3126.18    40.9 3119.53
    65.3 3106.63    74.7 3102.84    99.8 3090.85   116.9 3085.53   129.5 3083.22
   163.3 3083.19   184.4 3081.72   209.7 3082.33   222.3 3081.29     235 3079.24
   251.9 3080.59   267.5 3080.06   294.1 3076.95   306.93071.962   310.9 3070.67
   319.4 3069.63   340.5 3069.92  369.363071.963   377.2  3077.1   395.3  3092.4
   409.7 3102.14   423.5 3109.42     435 3116.28   457.1 3126.72   470.6 3131.77
#Mann= 5 ,-1,0
       0      .1       0     180     .06       0     190      .1       0
   306.9    .045       0  369.36      .1       0
Bank Sta=306.9,369.36
XS Rating Curve= 0 ,0
Exp/Cntr=0.3,0.1

Type RM Length L Ch R = 1 ,37394   ,339.1,339.1,339.1
XS GIS Cut Line= 4
2377450.93982598647424.4701739772377460.81987397647328.738744215
2377592.88530432647140.346913056 2377586.6008262646992.123391169
#Sta/Elev= 30
       0 3150.55    15.4  3139.5    23.4 3125.99    35.5 3120.92    44.2 3115.51
    59.6 3103.61    67.6 3093.35    71.7 3090.18    95.8 3078.22   110.4 3075.69
   127.1 3075.18   139.7 3073.27   164.1 3074.33   183.6 3072.13   232.5 3071.74
   247.1 3068.43   256.9 3066.13   281.3 3065.89   305.8 3066.37   316.13068.422
   320.4 3070.58   329.5  3077.7   353.5 3089.16   362.3 3092.17   405.6 3101.06
     425 3101.79   433.6 3105.61   445.6 3103.17   461.6 3109.14   474.7 3111.47
#Mann= 5 ,-1,0
       0      .1       0      70     .06       0  186.24      .1       0
   247.1    .045       0   316.1      .1       0
#XS Ineff= 2 , 0
          160.29 3092.19
Permanent Ineff=
       F       F
Bank Sta=247.1,316.1
XS Rating Curve= 0 ,0
Exp/Cntr=0.3,0.1