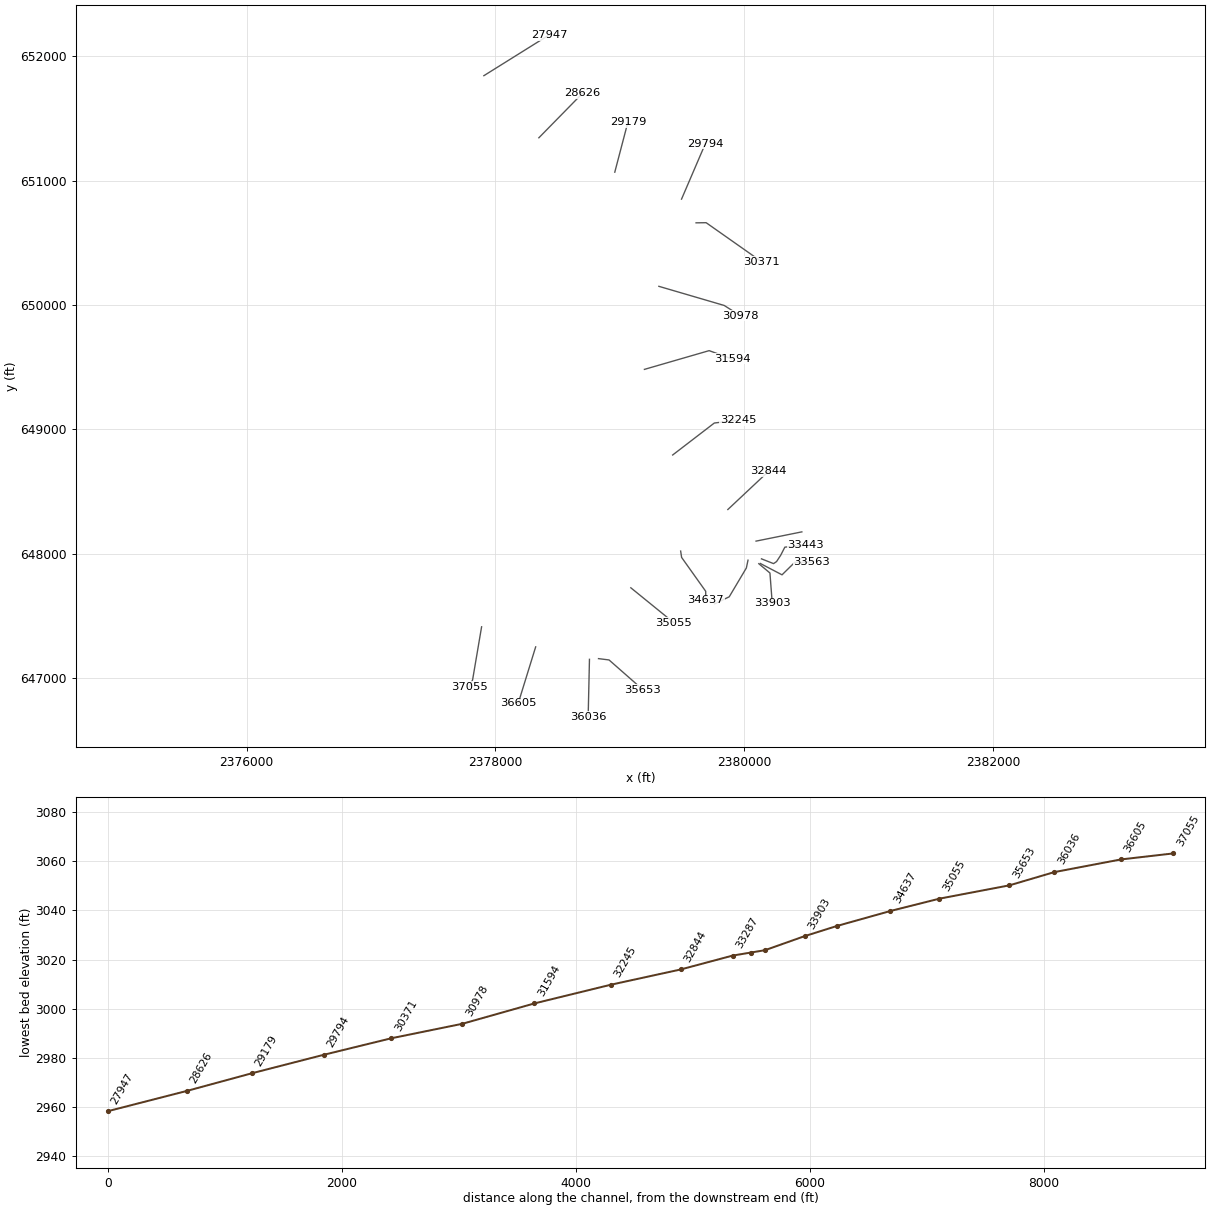
HEC-RAS study GNDYCK_1.prj: GNDYCK_1

--- GNDYCK_1.g01 (geometry) --- (continued)

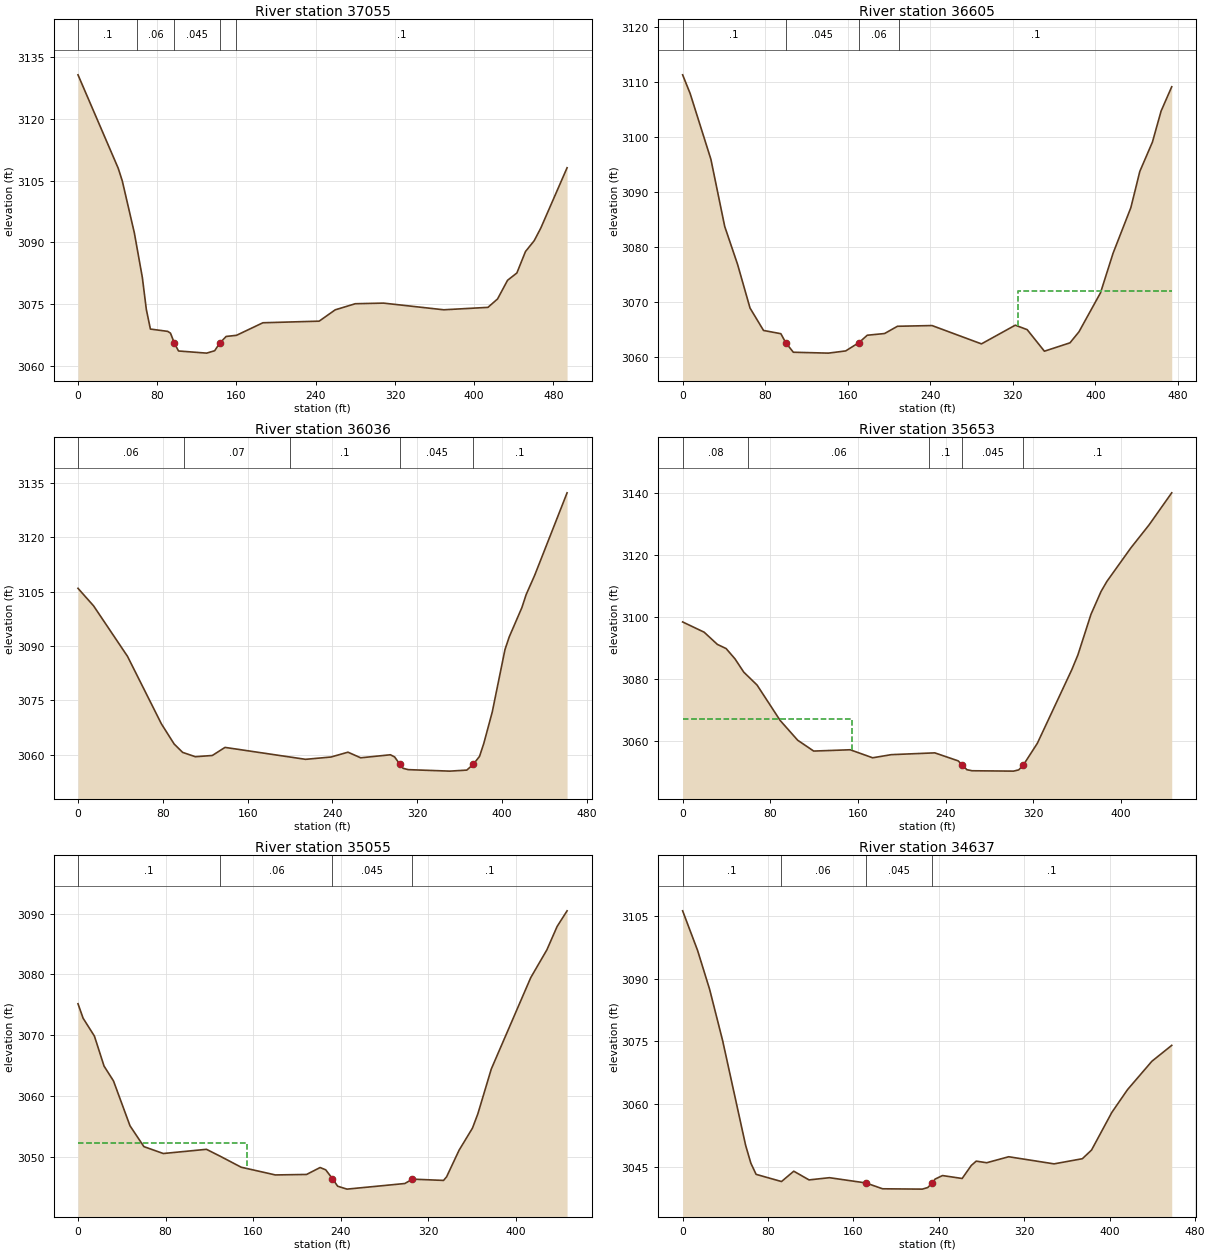
Type RM Length L Ch R = 1 ,37055   ,449.7,449.7,449.7
XS GIS Cut Line= 3
2377888.60734789647413.2545216412377816.36913462646987.539005293
2377791.52704355646930.748869483
#Sta/Elev= 30
       0 3130.69    40.6 3108.02    44.7 3104.96    56.9 3092.32      65 3081.46
      69 3073.74    73.1 3068.98    90.6 3068.42    93.4 3067.98   97.293065.566
   101.5 3063.66   129.9 3063.14     138 3063.72  143.113065.568   149.6 3067.19
     160 3067.46   186.7 3070.51   243.5  3070.9   259.7 3073.65     280 3075.13
   308.4 3075.28   369.3 3073.66   413.9 3074.25   423.6 3076.29   433.7 3080.82
   443.1 3082.59   451.8  3087.8   460.6 3090.43   467.2 3093.46   493.8 3108.13
#Mann= 5 ,-1,0
       0      .1       0      60     .06       0   97.29    .045       0
  143.11     .06       0     160      .1       0
Bank Sta=97.29,143.11
XS Rating Curve= 0 ,0
Exp/Cntr=0.3,0.1

Type RM Length L Ch R = 1 ,36605   ,568.9,568.9,568.9
XS GIS Cut Line= 2
2378323.48839146 647252.120913192378183.35739146 646799.26691319
#Sta/Elev= 30
       0 3111.25     7.3 3107.85    27.4  3095.9    40.8 3083.69    53.3 3076.78
    65.3 3068.88    78.4  3064.8    95.2 3064.21   99.923062.582   107.3 3060.84
   141.3 3060.68     158 3061.08  171.043062.609   178.9 3063.93   195.7 3064.24
   208.2 3065.56   241.7 3065.69   289.6 3062.36   322.4 3065.76   333.9 3064.95
   350.6 3061.03   375.4 3062.55   384.1 3064.55     405 3071.65   417.1  3078.8
   434.4 3087.12   443.1 3093.71   455.3 3099.03   463.7 3104.66     474 3109.08
#Mann= 4 ,-1,0
       0      .1       0   99.92    .045       0  171.04     .06       0
     210      .1       0
#XS Ineff= 2 , 0
                          325.27         3071.89
Permanent Ineff=
       F       F
Bank Sta=99.92,171.04
XS Rating Curve= 0 ,0
Exp/Cntr=0.3,0.1

Type RM Length L Ch R = 1 ,36036   ,383.1,383.1,383.1
XS GIS Cut Line= 2
2378756.00580805647151.8382001592378745.50398659646690.602140147
#Sta/Elev= 30
       0 3105.91    14.7 3101.08    46.7 3087.17    78.7 3068.55    90.7 3063.01
    98.7  3060.7   110.7  3059.5   126.7 3059.84   138.7 3062.07   214.7 3058.78
   238.7 3059.42   254.7 3060.75   266.7  3059.2   294.7 3060.04   298.7 3059.44
   303.7 3057.39   306.7 3056.31   311.5 3055.94   350.8 3055.53   366.8 3055.81
  372.913057.407   378.8 3059.59   382.8 3063.14   390.8 3071.81   402.8 3089.02
   406.8 3092.51   418.8 3100.63   422.8  3104.2   430.8 3109.48   461.4 3132.23
#Mann= 5 ,-1,0
       0     .06       0     100     .07       0     200      .1       0
   303.7    .045       0  372.91      .1       0
Bank Sta=303.7,372.91
XS Rating Curve= 0 ,0
Exp/Cntr=0.3,0.1

Type RM Length L Ch R = 1 ,35653   ,598.6,598.6,598.6
XS GIS Cut Line= 3
 2378828.7690451647157.4201099642378913.33331058647146.829538361
2379184.61276295646908.571440561
#Sta/Elev= 30
       0 3098.35    19.6 3095.05    31.7  3091.1    39.7 3089.75    47.8 3086.42
    55.8 3082.13    67.9 3077.98      89 3066.53     105 3060.14   119.6 3056.64
   152.9 3057.06   173.4 3054.47   190.4 3055.48   230.1 3056.06   251.4 3053.48
  255.38 3052.09   259.4 3050.62   264.1 3050.28     302 3050.16   306.7 3050.57
  310.833052.091   323.7 3059.16   355.2 3082.99   360.7 3087.71   372.6 3100.79
   381.8 3108.18   387.1 3111.42     409 3122.26   425.7 3129.73   446.3 3140.06
#Mann= 5 ,-1,0
       0     .08       0      60     .06       0  225.22      .1       0
  255.38    .045       0  310.83      .1       0
#XS Ineff= 2 , 0
          154.15 3067.16
Permanent Ineff=
       F       F
Bank Sta=255.38,310.83
XS Rating Curve= 0 ,0
Exp/Cntr=0.3,0.1

Type RM Length L Ch R = 1 ,35055   ,418.2,418.2,418.2
XS GIS Cut Line= 2
 2379088.5543306647727.106370488 2379435.2423306647445.549370488
#Sta/Elev= 30
       0 3075.19     4.7 3072.81      15 3069.88    23.8 3064.95    32.4 3062.52
    47.5 3055.14    60.2 3051.72    77.9 3050.59   117.3 3051.28     130 3050.13
     149 3048.34   180.2 3047.07   208.7 3047.15   221.1 3048.29   226.2 3047.91
  232.323046.464   237.1 3045.22   245.6 3044.74   298.4 3045.66   305.4 3046.38
   333.8 3046.17   336.6 3046.77     348 3051.14   360.2 3054.76   365.1  3057.1
   377.4 3064.48   413.4 3079.48   428.2 3084.07   437.5 3087.89   446.6 3090.46
#Mann= 4 ,-1,0
       0      .1       0     130     .06       0  232.32    .045       0
   305.4      .1       0
#XS Ineff= 2 , 0
          154.53 3052.37
Permanent Ineff=
       F       F
Bank Sta=232.32,305.4
XS Rating Curve= 0 ,0
Exp/Cntr=0.3,0.1

Type RM Length L Ch R = 1 ,34637   ,457.2,457.2,457.2
XS GIS Cut Line= 4
2379489.25870762648022.2190634482379497.04602543647971.140684067
2379690.57085025647699.1598491892379691.30020244647626.531608876
#Sta/Elev= 30
       0 3106.17      14 3096.72    25.3 3087.41    37.5 3075.15      59 3050.19
    63.9 3045.93    68.8 3043.26    92.6 3041.54   104.1 3044.01   118.4 3041.93
   137.5 3042.46   171.73041.202   187.3 3039.81   224.5 3039.73   229.6 3040.11
  233.763041.202   236.5 3042.13   243.4 3042.97   261.8 3042.27   270.4 3045.39
     275 3046.41   284.8 3046.03   305.4 3047.46   347.9 3045.76   374.4 3046.99
     383 3049.06     402 3058.04   416.7 3063.48   439.5 3070.25   458.1 3074.05
#Mann= 4 ,-1,0
       0      .1       0   91.67     .06       0   171.7    .045       0
  233.76      .1       0
Bank Sta=171.7,233.76
XS Rating Curve= 0 ,0
Exp/Cntr=0.3,0.1

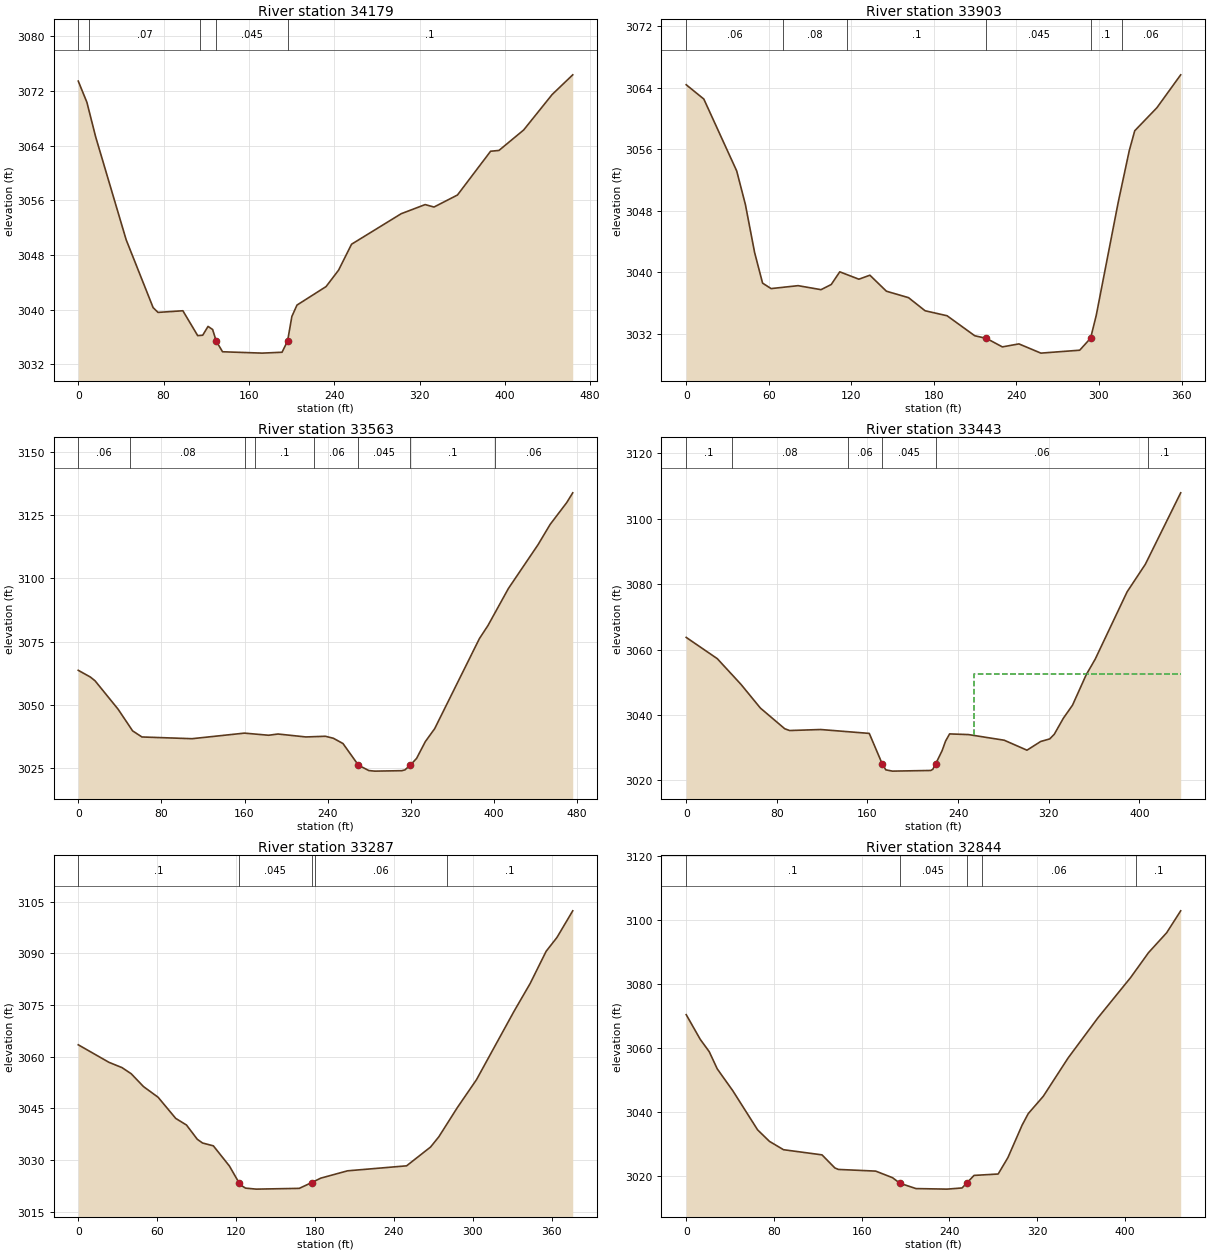
Type RM Length L Ch R = 1 ,34179   ,276.6,276.6,276.6
XS GIS Cut Line= 4
2380030.90827244647949.1116809652380017.57749572647886.328661194
2379879.95336378647654.7230750082379762.74708719647598.122879076
#Sta/Elev= 30
       0 3073.45     8.1 3070.35    16.3  3065.3    44.9 3050.24    70.2  3040.3
    74.8  3039.6    98.1 3039.84     112  3036.2   116.7 3036.26   121.7 3037.55
     126  3037.1  129.373035.403   135.3 3033.84   172.5 3033.64   191.1 3033.77
  196.283035.402   200.3    3039   205.1 3040.67   232.4 3043.38   244.1 3045.78
   256.3 3049.58   302.8 3054.04   325.3 3055.38   333.6 3055.02   355.6 3056.78
   386.7 3063.19   394.5  3063.3   417.7  3066.3   444.4 3071.49   463.7 3074.37
#Mann= 5 ,-1,0
       0      .1       0      10     .07       0  114.18      .1       0
  129.37    .045       0  196.28      .1       0
Bank Sta=129.37,196.28
XS Rating Curve= 0 ,0
Exp/Cntr=0.3,0.1

Type RM Length L Ch R = 1 ,33903   ,339.4,339.4,339.4
XS GIS Cut Line= 3
2380117.75445434647920.7263682832380207.28845302 647845.97105336
 2380225.7036477647603.930414379
#Sta/Elev= 30
       0 3064.39    12.8 3062.53    36.7 3053.18      43 3048.83    49.7 3042.59
    55.5  3038.6    61.7 3037.89    81.3 3038.27      98 3037.75   105.4 3038.42
   111.6 3040.07   125.5 3039.11   133.5 3039.63   145.5 3037.55   161.6 3036.71
   173.6 3035.01   189.6 3034.36   209.7 3031.76  218.243031.414   229.8 3030.31
   241.8  3030.7   257.8  3029.5     286 3029.88   293.9 3031.44     298 3034.39
     314 3049.12     322 3055.81     326 3058.41   342.1  3061.4   359.4 3065.68
#Mann= 6 ,-1,0
       0     .06       0      70     .08       0  116.64      .1       0
  218.24    .045       0   293.9      .1       0  316.64     .06       0
Bank Sta=218.24,293.9
XS Rating Curve= 0 ,0
Exp/Cntr(USF)=0,0
Exp/Cntr=0.3,0.1

Type RM Length L Ch R = 1 ,33563   ,120.9,120.9,120.9
XS GIS Cut Line= 4
2380129.80997496647922.6440156452380304.55325819647831.314245359
2380407.30291996647932.292361239 2380541.9404078647934.063907132
#Sta/Elev= 30
       0 3063.63    11.7 3060.96    16.2 3059.47    38.4 3048.23    52.3 3039.69
    61.3 3037.28   109.5  3036.6   159.9  3038.8   183.2 3037.96   192.2 3038.45
   219.1 3037.29   237.8 3037.56   245.5 3036.78   254.8 3034.68  269.69 3026.11
   279.7    3024   285.4 3023.78   311.4 3023.95   314.4 3024.27  319.48 3026.11
   325.6  3028.8     334 3035.43     343 3040.55   386.1 3076.18   394.3 3081.32
     414 3095.98   442.6 3113.35   454.1 3121.27   470.1 3129.92   475.9 3133.79
#Mann= 8 ,-1,0
       0     .06       0      50     .08       0     160     .06       0
     170      .1       0  227.17     .06       0  269.69    .045       0
  319.48      .1       0  401.23     .06       0
Bank Sta=269.69,319.48
XS Rating Curve= 0 ,0
Exp/Cntr(USF)=0,0
Exp/Cntr=0.3,0.1

Type RM Length L Ch R = 1 ,33443   ,155.6,155.6,155.6
XS GIS Cut Line= 6
2380139.19450109647959.705172536 2380236.2887276647921.486563399
2380260.26461087647937.6069989172380293.92398283647988.981829803
2380327.15146724 648053.917658822380495.23860394648069.519420375
#Sta/Elev= 30
       0 3063.71    27.4 3057.22    48.3 3049.37    65.5  3042.1      87 3035.78
    91.3 3035.24   118.7 3035.55   161.6 3034.36  172.933025.129   176.2 3023.22
     182 3022.83   215.9 3023.03   217.7  3023.4  220.313025.126   225.9 3029.09
   228.9 3031.98   232.5 3034.21   249.2    3034   280.7 3032.28   300.8 3029.23
   312.9 3031.89   320.9 3032.68   324.9  3034.1   332.9 3038.99     341 3042.99
     353 3052.22   361.1 3057.11   389.2 3077.64   405.3 3086.07   436.5 3107.91
#Mann= 6 ,-1,0
       0      .1       0      40     .08       0  143.24     .06       0
  172.93    .045       0  220.31     .06       0  407.64      .1       0
#XS Ineff= 2 , 0
                           254.1         3052.45
Permanent Ineff=
       F       F
Bank Sta=172.93,220.31
XS Rating Curve= 0 ,0
Exp/Cntr=0.3,0.1

Type RM Length L Ch R = 1 ,33287   ,442.9,442.9,442.9
XS GIS Cut Line= 2
2380095.51084286648102.3607669322380463.99238853648176.765694423
#Sta/Elev= 30
       0 3063.47    23.3 3058.39    33.3 3056.84    40.3 3055.05    49.6 3051.34
    60.7 3048.25    74.1 3042.11    82.3 3040.18    90.5 3036.05    94.5 3034.97
   102.7 3034.15   114.9  3028.3  122.133023.492   123.1 3022.85   127.2 3021.88
   135.3 3021.59     168 3021.81  177.473023.492   184.3 3024.77   204.7  3026.9
   249.6 3028.35   267.8  3033.8   274.1 3036.77   288.1  3045.2   302.7 3053.33
   331.2 3073.14   343.5 3081.23   355.7 3090.61   363.9 3094.61   375.9 3102.34
#Mann= 5 ,-1,0
       0      .1       0  122.13    .045       0  177.47      .1       0
     180     .06       0     280      .1       0
Bank Sta=122.13,177.47
XS Rating Curve= 0 ,0
Exp/Cntr(USF)=0,0
Exp/Cntr=0.3,0.1

Type RM Length L Ch R = 1 ,32844   ,598.7,598.7,598.7
XS GIS Cut Line= 2
2379868.84017075648356.4485904992380197.53171918648665.005348028
#Sta/Elev= 30
       0 3070.44    12.8 3062.73      21 3058.87    28.3 3053.51    42.5 3046.67
    65.1 3034.46    75.9 3030.87    88.7 3028.27   123.8 3026.66   135.5 3022.58
   138.7 3022.11   172.7 3021.59   188.1 3019.53  194.813017.798   209.5 3016.13
   237.8 3015.96   251.5 3016.33  255.563017.799   262.4 3020.24   284.4 3020.68
   293.3 3025.82   306.3    3036   311.8 3039.53   325.5 3044.94   348.1 3056.89
   375.1 3069.35   405.1 3082.01   421.5 3089.82     438 3096.02   450.8 3102.87
#Mann= 5 ,-1,0
       0      .1       0  194.81    .045       0  255.56      .1       0
     270     .06       0     410      .1       0
Bank Sta=194.81,255.56
XS Rating Curve= 0 ,0
Exp/Cntr=0.3,0.1

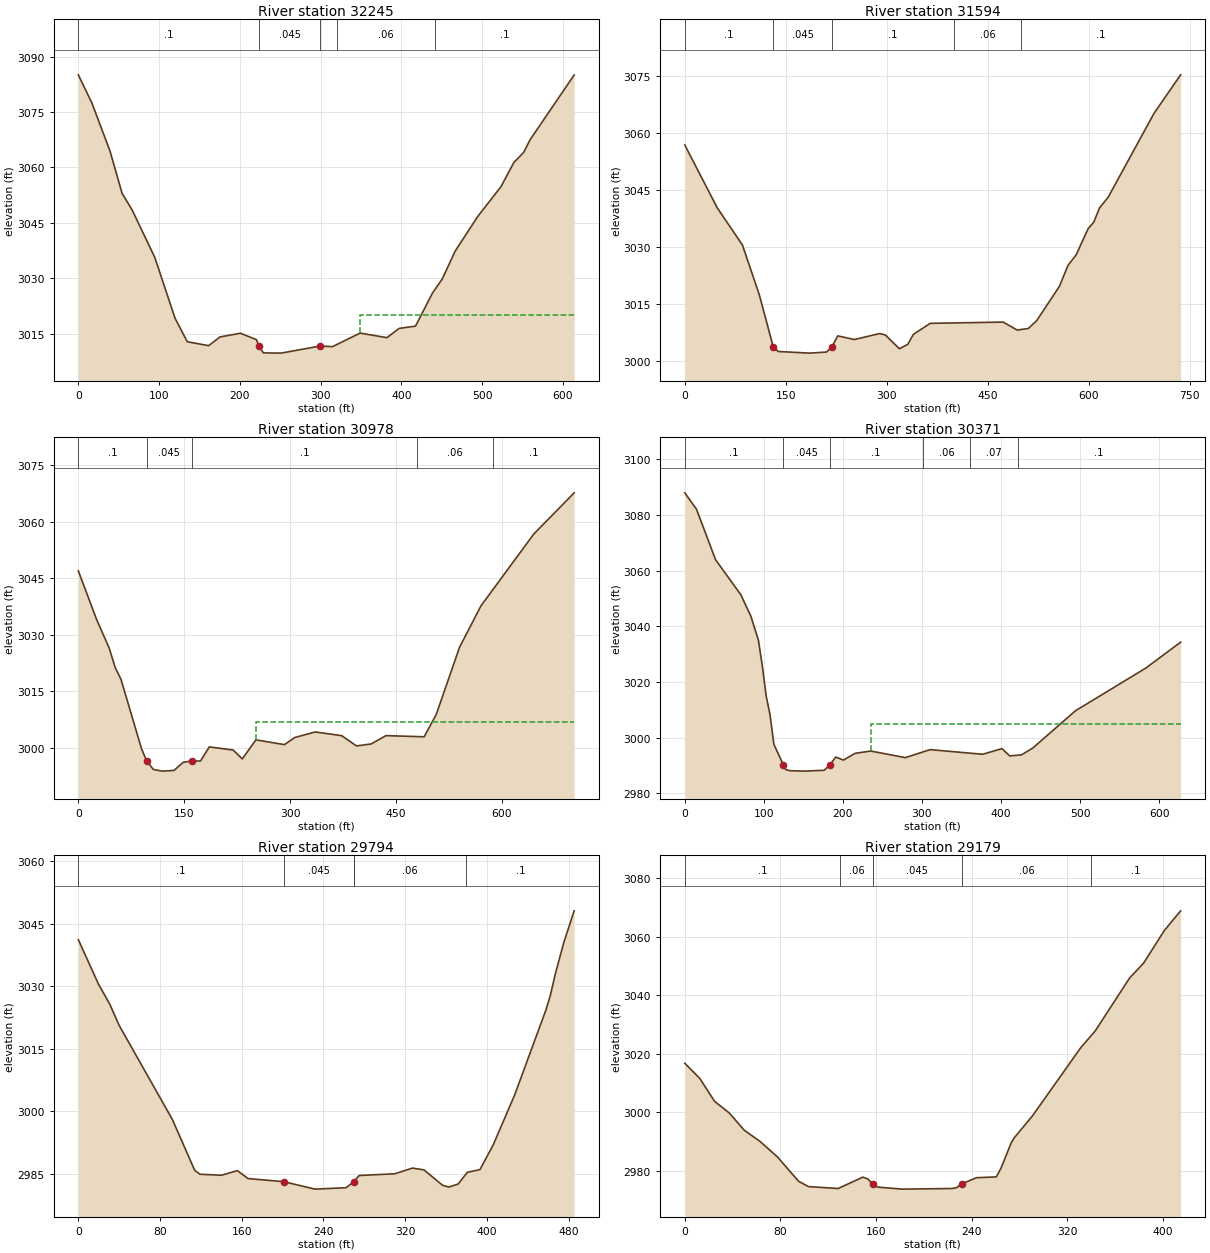
Type RM Length L Ch R = 1 ,32245   ,651.3,651.3,651.3
XS GIS Cut Line= 3
2379425.14892242648794.9502516322379759.97503809649051.949938185
2379950.24702313649075.570561242
#Sta/Elev= 30
       0 3085.09    16.8 3077.45    39.1 3064.53    54.2 3052.98    66.5 3048.55
    94.6 3035.68   119.8 3019.16   134.9 3012.82   161.3 3011.76   175.3 3014.11
   200.6 3015.13   220.5 3013.39  223.593011.593   229.1 3009.81   250.9 3009.74
   299.3 3011.65   314.7  3011.5   348.9 3015.17     382 3013.92   397.1 3016.43
   417.4 3017.05   438.4 3025.99   450.5 3029.81   466.6  3037.4   494.5 3046.76
   523.1 3054.77   539.2 3061.36   551.3 3064.09   559.3 3067.53   613.8 3085.05
#Mann= 5 ,-1,0
       0      .1       0  223.59    .045       0   299.3      .1       0
     320     .06       0  442.09      .1       0
#XS Ineff= 2 , 0
                        348.8811            3020
Permanent Ineff=
       F       F
Bank Sta=223.59,299.3
XS Rating Curve= 0 ,0
Exp/Cntr=0.3,0.1

Type RM Length L Ch R = 1 ,31594   ,616,616,616
XS GIS Cut Line= 3
 2379197.9792277  649483.41877232379718.36946653649634.093373106
2379901.39185824649567.646596969
#Sta/Elev= 30
       0 3056.79    48.1 3040.33    85.6 3030.54   110.6 3017.53   131.4 3003.79
   138.8 3002.59   185.5 3002.16   210.5 3002.44  218.263003.739   227.2 3006.69
   252.1 3005.73   289.6 3007.31     298 3006.91   318.8 3003.31   331.3 3004.47
   339.6  3007.1   364.6 3009.98   472.9 3010.31   493.7 3008.22   510.3 3008.63
   522.8 3010.71   556.4 3019.67   569.2 3025.19   581.4 3027.98     599 3034.79
   607.5 3036.53     616 3040.28   628.8 3043.06   696.9 3065.07   736.5 3075.21
#Mann= 5 ,-1,0
       0      .1       0   131.4    .045       0  218.26      .1       0
     400     .06       0     500      .1       0
Bank Sta=131.4,218.26
XS Rating Curve= 0 ,0
Exp/Cntr=0.3,0.1

Type RM Length L Ch R = 1 ,30978   ,607.1,607.1,607.1
XS GIS Cut Line= 3
2379314.17168291650151.2440186072379839.45438442649997.436861884
2379970.25877614649914.475216382
#Sta/Elev= 30
       0 3046.96    25.8  3034.1    43.8 3026.45    52.1 3021.39    60.4 3018.21
    89.6 2999.76    96.8 2996.55   106.4 2994.31   118.8 2993.88   135.5 2994.06
   148.4 2996.21   160.5 2996.57     173 2996.56   185.5  3000.3   219.3 2999.47
   232.2 2997.12   251.5 3002.17     292  3000.9   306.3 3002.78   335.5 3004.26
     373 3003.28   393.9 3000.56   414.7 3001.08   435.6 3003.29   489.7 3002.98
   506.8 3008.85   539.8 3026.67   570.2 3037.68   644.9 3056.69   702.2 3067.64
#Mann= 5 ,-1,0
       0      .1       0    96.8    .045       0   160.5      .1       0
     480     .06       0  587.34      .1       0
#XS Ineff= 2 , 0
                           251.5            3007
Permanent Ineff=
       F       F
Bank Sta=96.8,160.5
XS Rating Curve= 0 ,0
Exp/Cntr=0.3,0.1

Type RM Length L Ch R = 1 ,30371   ,576.7,576.7,576.7
XS GIS Cut Line= 3
2379613.24224266650661.8686604642379694.26480222650662.887619413
2380141.00085076650348.731611932
#Sta/Elev= 30
       0 3087.93    14.9 3081.99    38.9 3063.92    70.9 3051.32    83.4 3043.75
    93.1 3035.06      98 3025.88   102.9 3015.03   107.8 3008.24   112.7 2997.61
  124.792990.177   127.4 2988.64   132.4 2988.15   151.8 2987.99   176.3  2988.3
  183.312990.114   190.9 2993.03   200.7 2991.96   215.4 2994.37     235 2995.21
     279 2992.84   310.4 2995.71   376.8 2994.04   401.2 2996.08     411 2993.46
   425.7 2993.81   440.3  2996.3   494.1 3009.65   583.2    3025   627.2  3034.3
#Mann= 6 ,-1,0
       0      .1       0  124.79    .045       0  183.31      .1       0
  301.03     .06       0  361.03     .07       0  421.03      .1       0
#XS Ineff= 2 , 0
                           235.8            3005
Permanent Ineff=
       F       F
Bank Sta=124.79,183.31
XS Rating Curve= 0 ,0
Exp/Cntr=0.3,0.1

Type RM Length L Ch R = 1 ,29794   ,615.4,615.4,615.4
XS GIS Cut Line= 2
2379496.39894399650852.4950186072379688.00263054651298.580414157
#Sta/Elev= 30
       0 3041.14    19.7 3030.49    30.8 3025.66    39.9  3020.6    92.2 2997.94
   113.9 2985.81   119.1 2984.85   140.1 2984.61   155.7 2985.72   166.2 2983.82
   201.3 2983.06   231.8 2981.28   262.2 2981.62  269.682983.052     275 2984.55
   309.8 2984.96   327.2 2986.33   338.4  2985.9   356.7  2982.2   362.7 2981.78
   371.9  2982.5     381 2985.33   393.2 2985.95   406.2 2991.87   427.4 3003.98
   457.8 3024.23   462.2 3027.76   467.2 3033.07   475.4 3040.48   485.5 3048.06
#Mann= 5 ,-1,0
       0      .1       0   201.3    .045       0  269.68      .1       0
     270     .06       0     380      .1       0
Bank Sta=201.3,269.68
XS Rating Curve= 0 ,0
Exp/Cntr=0.3,0.1

Type RM Length L Ch R = 1 ,29179   ,553.3,553.3,553.3
XS GIS Cut Line= 2
2378959.56113447 651069.13246269 2379064.7632277651470.325585843
#Sta/Elev= 30
       0 3016.79    12.5 3011.63    24.9 3003.79    37.3 2999.75    49.7 2993.91
    62.8 2990.12    77.7 2984.69    95.2 2976.45   103.4 2974.63   128.3 2973.97
   148.9 2977.86   153.1 2977.25   157.2  2975.5   161.3 2974.45     182 2973.76
   223.4 2973.97   227.5 2974.28   231.6 2975.55     244 2977.66   260.6 2977.94
   264.7 2981.07     273 2989.52   275.7 2991.35   290.7 2998.72   331.4  3022.2
   343.3 3027.81   372.2 3045.99   383.9 3051.04   401.2 3062.19   414.8  3068.9
#Mann= 5 ,-1,0
       0      .1       0     130     .06       0   157.2    .045       0
   231.6     .06       0     340      .1       0
Bank Sta=157.2,231.6
XS Rating Curve= 0 ,0
Exp/Cntr=0.3,0.1

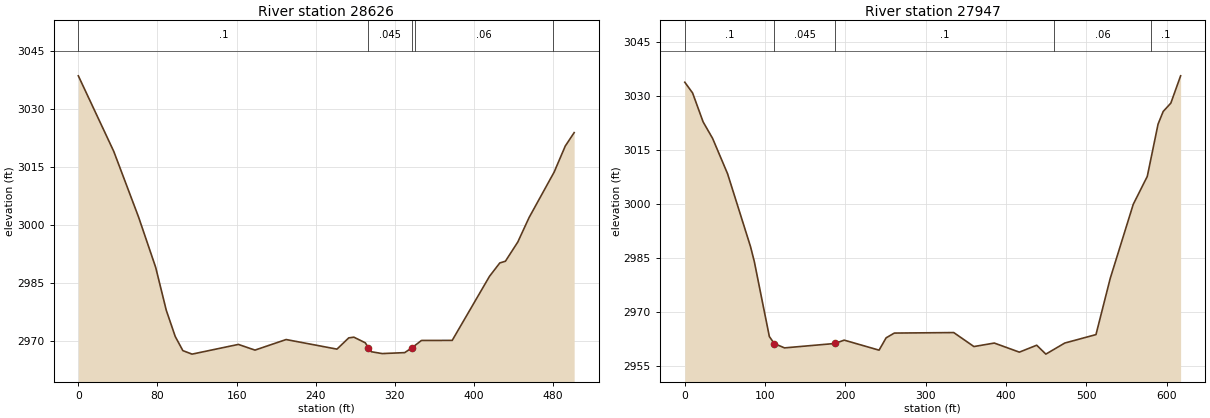
Type RM Length L Ch R = 1 ,28626   ,679,679,679
XS GIS Cut Line= 2
2378349.07613064651345.680817188 2378700.0512277651703.550421638
#Sta/Elev= 30
       0 3038.53    35.8 3019.02    60.9 3002.04    78.2 2989.04    88.9 2977.96
      98 2971.15   105.7 2967.51     115 2966.61   161.8 2969.12   178.6 2967.65
   210.1 2970.38   261.5  2967.9   273.4 2970.81   278.6 2970.99   290.1 2969.54
   293.2 2968.31   296.2 2967.23   307.2 2966.75     330    2967  337.632968.309
   346.9 2970.14     378 2970.16   415.7 2986.71   426.1 2990.17   431.8 2990.62
   444.3 2995.57   455.7 3001.89   481.1 3013.67   492.3 3020.38   501.3 3023.85
#Mann= 5 ,-1,0
       0      .1       0   293.2    .045       0  337.63      .1       0
     340     .06       0     480      .1       0
Bank Sta=293.2,337.63
XS Rating Curve= 0 ,0
Exp/Cntr=0.3,0.1

Type RM Length L Ch R = 1 ,27947   ,589.8,589.8,589.8
XS GIS Cut Line= 2
2377906.81744213651845.1065748062378430.51848553652172.030313885
#Sta/Elev= 30
       0 3033.75     9.7 3030.78    22.8 3022.76    34.6 3018.18    53.3 3008.35
    81.8 2988.18    86.5 2984.07   105.3  2963.2   111.4 2961.26   124.2 2960.06
   186.8 2961.28   198.5 2962.21   241.9 2959.43   250.7 2962.85   260.9 2964.17
   334.9 2964.31     360 2960.43   385.4  2961.4   416.6 2958.88   438.2  2960.8
   449.6 2958.33   473.1  2961.4     512 2963.75   529.7  2979.3   558.4 2999.88
   575.9 3007.64   589.3 3022.12   595.7 3025.65   605.2 3027.95   617.4 3035.53
#Mann= 5 ,-1,0
       0      .1       0   111.4    .045       0   186.8      .1       0
     460     .06       0     580      .1       0
Bank Sta=111.4,186.8
XS Rating Curve= 0 ,0
Exp/Cntr=0.3,0.1