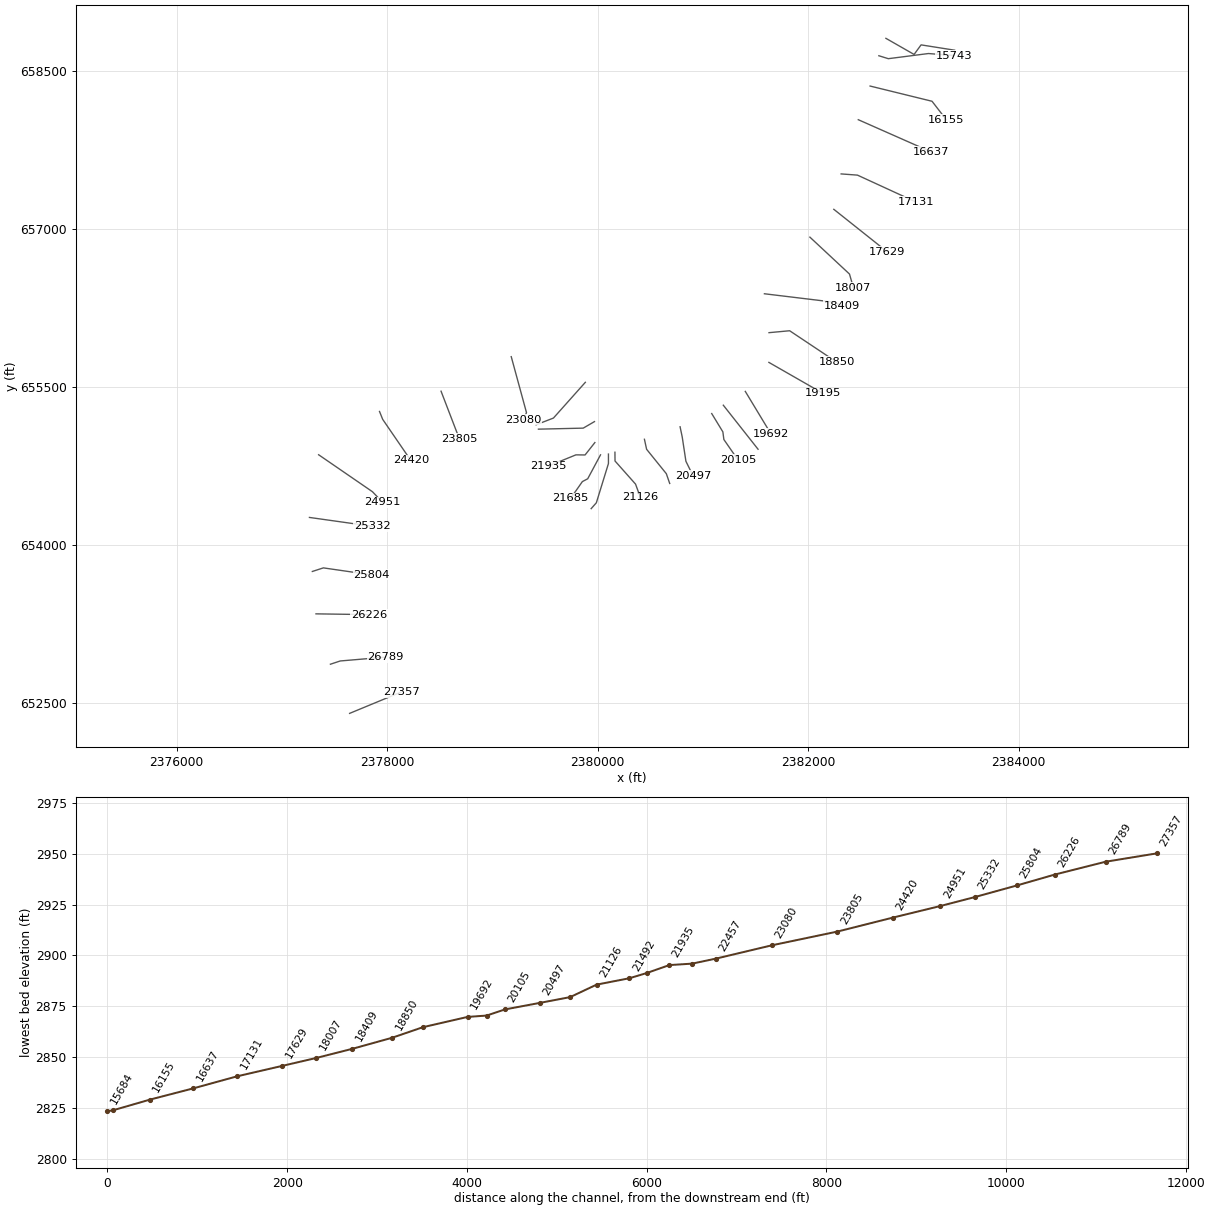
HEC-RAS study GNDYCK_1.prj: GNDYCK_1

--- GNDYCK_1.g01 (geometry) --- (continued)

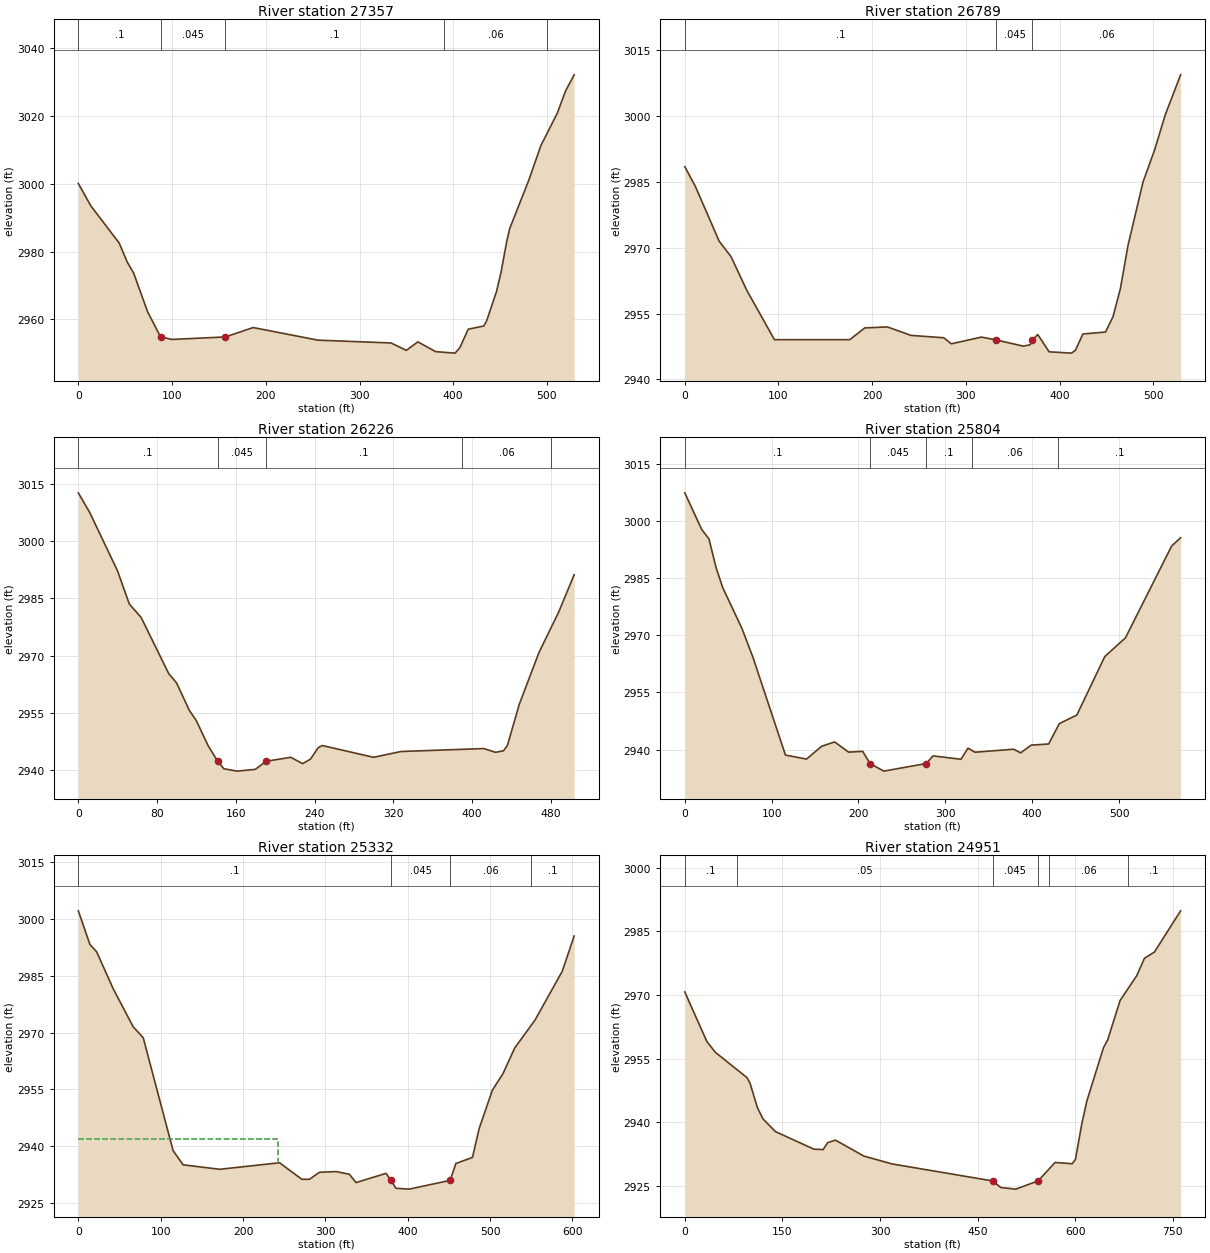
Type RM Length L Ch R = 1 ,27357   ,568.1,568.1,568.1
XS GIS Cut Line= 2
 2377643.8650433652400.3402173032378132.68126065652602.525478157
#Sta/Elev= 30
       0 3000.05    13.3 2993.47    43.6  2982.5    52.3 2976.85    59.1  2973.6
    73.9 2962.28   87.722954.875    99.9 2954.12     157 2954.86   186.5 2957.62
   255.7 2953.91   333.6 2953.08     350 2950.91   362.2 2953.41   381.3 2950.52
     402 2950.09   407.2 2951.76   415.9 2957.13   432.6 2958.08   435.7 2959.64
   446.2 2968.27     451 2973.89   457.1 2983.04   460.2 2986.72   480.8 3001.17
   493.6 3011.28     500 3014.73   511.1 3020.81   519.8 3027.27     529 3032.04
#Mann= 5 ,-1,0
       0      .1       0   87.72    .045       0     157      .1       0
     390     .06       0     500      .1       0
Bank Sta=87.72,157
XS Rating Curve= 0 ,0
Exp/Cntr=0.3,0.1

Type RM Length L Ch R = 1 ,26789   ,562.7,562.7,562.7
XS GIS Cut Line= 3
 2377461.3609129652867.3331738882377554.72082381652898.294225042
2377984.16234769652934.724869528
#Sta/Elev= 30
       0 2988.46    11.4 2983.93    36.7 2971.49    49.3    2968    66.2  2960.3
    95.7 2949.06   176.1 2949.06   192.1 2951.74   216.2 2951.97   241.5 2950.04
   276.5  2949.5   284.5 2948.12   316.6 2949.65   332.7 2948.99   361.4 2947.59
   368.8 2947.91  371.172949.052   376.8 2950.23   388.9  2946.3   412.9    2946
     417 2946.66     425 2950.36   449.1  2950.8   457.1 2954.28     465 2960.68
   473.2 2970.59   489.2 2985.01   501.3 2992.13   513.1 3000.41   529.3 3009.39
#Mann= 3 ,-1,0
       0      .1       0   332.7    .045       0  371.17     .06       0
Bank Sta=332.7,371.17
XS Rating Curve= 0 ,0
Exp/Cntr=0.3,0.1

Type RM Length L Ch R = 1 ,26226   ,422.5,422.5,422.5
XS GIS Cut Line= 2
 2377324.3979129653345.8905650562377827.97826067653338.561826022
#Sta/Elev= 30
       0  3012.6    11.8 3007.34    39.8 2992.17    51.8 2983.48    63.8 2979.97
    91.8 2965.27    99.8 2962.82   112.7 2955.66   119.8 2952.97   131.8 2946.42
  141.532942.336   147.8 2940.35   161.4 2939.73   179.8  2940.2  190.792942.316
   215.8 2943.35   227.8 2941.68   235.8 2942.88   243.8  2945.9   247.8 2946.43
   299.8 2943.35   327.8 2944.87   411.8 2945.64   423.8 2944.66   431.8 2945.05
   435.8 2946.45   447.8 2957.18   467.8 2970.75   487.8 2981.33   503.6 2991.16
#Mann= 5 ,-1,0
       0      .1       0  141.53    .045       0  190.79      .1       0
     390     .06       0     480      .1       0
Bank Sta=141.53,190.79
XS Rating Curve= 0 ,0
Exp/Cntr=0.3,0.1

Type RM Length L Ch R = 1 ,25804   ,471.8,471.8,471.8
XS GIS Cut Line= 3
 2377289.7462559653748.5944647272377394.47021116653782.678507965
2377850.43392811653716.624154909
#Sta/Elev= 30
       0 3007.37    19.4 2997.79    27.8 2995.28    36.2 2987.62    43.6 2982.54
    65.7 2971.84    78.3 2964.34   115.9 2938.58   140.1 2937.53   157.6 2940.89
   172.5 2942.03   188.6 2939.35   204.8 2939.56  213.292936.366   229.1 2934.37
  277.972936.365   285.9 2938.37     318 2937.48   326.1  2940.4   334.1 2939.33
   378.6 2940.12   386.7 2939.16   398.8 2941.19     419 2941.49   431.2 2946.83
   451.4 2949.08   483.6 2964.43   507.4 2969.34   560.5 2993.39   570.9  2995.6
#Mann= 5 ,-1,0
       0      .1       0  213.29    .045       0  277.97      .1       0
  330.13     .06       0  430.13      .1       0
Bank Sta=213.29,277.97
XS Rating Curve= 0 ,0
Exp/Cntr=0.3,0.1

Type RM Length L Ch R = 1 ,25332   ,380.6,380.6,380.6
XS GIS Cut Line= 2
2377262.18236224      654261.9262377858.49259186654177.845243428
#Sta/Elev= 30
       0 3002.16    14.1 2993.25    22.2 2991.35    42.4 2981.54    66.6 2971.53
    78.8 2968.63   115.1  2938.8   127.2 2935.05   171.7 2933.86   244.4 2935.59
   271.5 2931.21   280.7 2931.22   292.9 2933.07   313.1 2933.26   329.2 2932.55
   337.3 2930.35   373.7 2932.79  379.522930.986   385.8 2928.84   401.9 2928.62
   451.62930.937   458.5 2935.39   478.7    2937   486.8 2944.61   502.9 2954.78
   515.8 2959.14   529.9 2965.88   554.7 2973.31   587.7 2986.17   602.2  2995.5
#Mann= 4 ,-1,0
       0      .1       0  379.52    .045       0   451.6     .06       0
     550      .1       0
#XS Ineff= 2 , 0
           243.1 2941.83
Permanent Ineff=
       F       F
Bank Sta=379.52,451.6
XS Rating Curve= 0 ,0
Exp/Cntr=0.3,0.1

Type RM Length L Ch R = 1 ,24951   ,531.3,531.3,531.3
XS GIS Cut Line= 3
2377349.33914726 654857.519028352377861.10964191654506.061671768
2377958.60402778      654404.118
#Sta/Elev= 30
       0 2970.74    33.9 2959.05    47.1  2956.5    95.6 2950.54   100.1  2949.3
   111.6 2943.47   120.2 2940.81   139.3 2937.82   198.4 2933.68   212.6 2933.58
   219.6 2935.23   231.5 2935.81   275.2 2932.05   318.8 2930.19  473.11 2926.19
   485.6 2924.63   508.6 2924.26  542.792926.192     569 2930.54   595.4 2930.25
   600.3 2931.28     610 2939.61   617.9 2945.08   643.4 2957.62   649.7 2959.38
   668.9 2968.74   694.4 2974.56   706.3 2978.68   721.7 2980.16   761.9 2989.87
#Mann= 6 ,-1,0
       0      .1       0      80     .05       0  473.11    .045       0
  542.79     .05       0     560     .06       0  680.83      .1       0
Bank Sta=473.11,542.79
XS Rating Curve= 0 ,0
Exp/Cntr=0.3,0.1

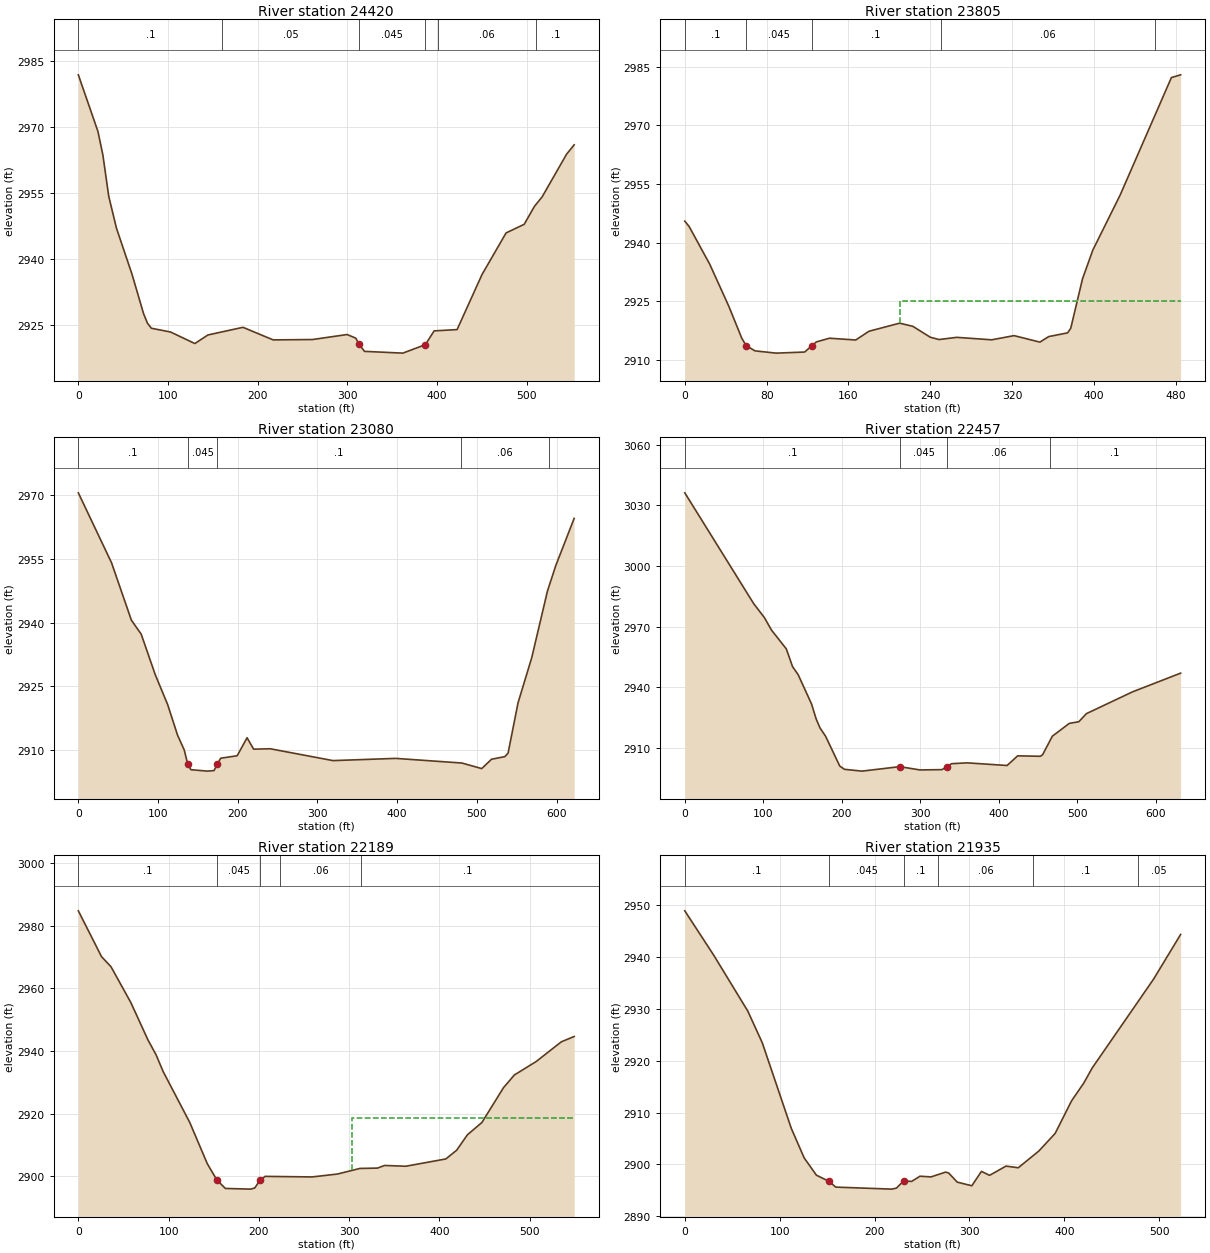
Type RM Length L Ch R = 1 ,24420   ,614.5,614.5,614.5
XS GIS Cut Line= 3
2377928.03904649 655268.673078422377958.03145811655193.858445395
2378224.90012283654804.436828609
#Sta/Elev= 30
       0 2981.82    21.9 2968.93    27.4 2963.54    33.9  2954.2    42.5 2946.96
    59.8  2936.5    72.7 2927.53      77 2925.37    81.4  2924.2   102.8 2923.34
   129.9 2920.72   144.5 2922.67   183.5 2924.41   217.2 2921.55     261 2921.63
   299.6 2922.77   309.3 2921.94   313.12920.521     319 2918.94   361.7 2918.54
   386.9 2920.47   396.6  2923.6   422.2 2923.89     450 2936.41   476.8 2945.87
     497 2947.83   508.5 2951.93   517.1  2954.1   544.3 2963.79   552.7  2965.9
#Mann= 6 ,-1,0
       0      .1       0   160.6     .05       0   313.1    .045       0
   386.9     .05       0   400.6     .06       0   510.6      .1       0
Bank Sta=313.1,386.9
XS Rating Curve= 0 ,0
Exp/Cntr=0.3,0.1

Type RM Length L Ch R = 1 ,23805   ,725.7,725.7,725.7
XS GIS Cut Line= 2
2378512.72664815655461.2089431212378686.54740873655008.754381708
#Sta/Elev= 30
       0  2945.5     4.3 2944.11    24.4 2934.47    43.1 2923.67    55.7 2915.53
      60 2913.64    68.6 2912.29    89.4 2911.71   117.2 2911.99   124.3 2913.64
   128.6 2914.58   141.4 2915.53   167.1 2915.07     180 2917.31     210 2919.38
   222.9 2918.58     240 2915.78   248.6 2915.19   265.8 2915.75     300 2915.12
   321.9 2916.19   347.1 2914.53   355.7 2915.94   374.2  2916.9   377.3 2918.08
   388.8 2930.74   398.9 2938.11   425.5 2952.14   475.7 2982.27   484.7 2982.97
#Mann= 5 ,-1,0
       0      .1       0      60    .045       0   124.3      .1       0
     250     .06       0     460      .1       0
#XS Ineff= 2 , 0
                          210.83         2925.03
Permanent Ineff=
       F       F
Bank Sta=60,124.3
XS Rating Curve= 0 ,0
Exp/Cntr=0.3,0.1

Type RM Length L Ch R = 1 ,23080   ,622.9,622.9,622.9
XS GIS Cut Line= 3
2379179.58888779655789.443698334 2379324.3919013655258.251997064
2379298.30366709655191.691333781
#Sta/Elev= 30
       0 2970.57    41.7 2954.08    66.6 2940.55    78.9 2937.27    96.4 2927.78
   112.2 2920.62   124.5 2913.47   132.9 2909.98   137.1 2906.76   141.2 2905.34
     162    2905   170.3 2905.13   174.4 2906.66   178.6 2908.04   199.3 2908.62
   211.7 2912.86     220 2910.17   240.7 2910.27   319.5 2907.48   398.3    2908
   481.2 2906.91   506.1  2905.6   518.5 2907.81   535.1 2908.41   539.2 2909.24
   551.7  2921.1   568.9 2931.74   588.6 2947.43     599 2953.41   622.1 2964.55
#Mann= 5 ,-1,0
       0      .1       0   137.1    .045       0   174.4      .1       0
     480     .06       0  590.57      .1       0
Bank Sta=137.1,174.4
XS Rating Curve= 0 ,0
Exp/Cntr=0.3,0.1

Type RM Length L Ch R = 1 ,22457   ,267.9,267.9,267.9
XS GIS Cut Line= 3
2379883.65907367655545.7222915772379580.61660304655206.142209454
 2379415.6332437  655142.3475748
#Sta/Elev= 30
       0 3036.25    87.8 2981.39   101.4 2974.52   110.5  2968.3   129.4 2958.99
   137.4 2950.17   144.5 2946.22   161.6 2931.67   167.4 2924.33   172.3 2919.87
   179.5 2915.72   197.5 2900.98   203.5 2899.36   225.9 2898.46   274.1 2900.68
   299.6 2899.05   327.8  2899.2   334.3 2900.73     340 2902.14   359.7 2902.56
   410.8 2901.25   424.3 2906.03   453.3 2905.81   456.2 2906.67   468.5 2915.76
   490.2 2922.12   502.2  2922.9   511.9 2926.92   570.7 2937.71     632 2946.97
#Mann= 4 ,-1,0
       0      .1       0   274.1    .045       0   334.3     .06       0
  465.14      .1       0
Bank Sta=274.1,334.3
XS Rating Curve= 0 ,0
Exp/Cntr=0.3,0.1

Type RM Length L Ch R = 1 ,22189   ,253.8,253.8,253.8
XS GIS Cut Line= 3
2379970.40045166655172.3713375982379863.58742447655110.397018122
2379437.95614097655100.641296395
#Sta/Elev= 30
       0 2984.76    25.7 2970.14    36.2 2966.92    58.1 2955.53    77.1 2943.59
    86.1 2938.83      94 2933.46   123.5  2917.2   142.9 2904.05  153.662898.804
   162.9 2896.19   190.9 2895.97   195.4 2896.34  201.222898.776   206.9 2900.04
   258.9 2899.86   286.9 2900.78   311.9 2902.57   331.4 2902.68   339.2 2903.52
   362.7 2903.27     407 2905.59     419 2908.36     431 2913.32     447 2917.22
     471 2928.36     483 2932.39     507 2936.65     535 2942.97   549.2 2944.67
#Mann= 5 ,-1,0
       0      .1       0  153.66    .045       0  201.22      .1       0
  223.49     .06       0  313.49      .1       0
#XS Ineff= 2 , 0
                          302.73         2918.63
Permanent Ineff=
       F       F
Bank Sta=153.66,201.22
XS Rating Curve= 0 ,0
Exp/Cntr=0.3,0.1

Type RM Length L Ch R = 1 ,21935   ,250.5,250.5,250.5
XS GIS Cut Line= 4
2379974.14251823654973.2630939252379881.22947933654855.589067158
2379794.00007546654856.4553806072379529.75314689654748.788750529
#Sta/Elev= 30
       0 2948.92    30.7  2940.3    66.4 2929.58    81.7 2923.45   112.2 2906.98
   125.8 2901.27   138.7 2897.94   152.32896.723     159 2895.64   218.1 2895.25
     223 2895.45   230.62896.825   239.1 2896.74   247.8 2897.74   259.5 2897.61
   274.8 2898.53     278 2898.37   287.1  2896.6   302.5  2895.9   312.6 2898.67
   321.2 2897.91   338.5 2899.69   351.4 2899.37   373.1  2902.6   390.3    2906
   407.6 2912.28   420.5 2915.72   429.2 2918.58     494 2935.75   522.5 2944.36
#Mann= 6 ,-1,0
       0      .1       0   152.3    .045       0   230.6      .1       0
  267.17     .06       0  367.17      .1       0  477.17     .05       0
Bank Sta=152.3,230.6
XS Rating Curve= 0 ,0
Exp/Cntr=0.3,0.1

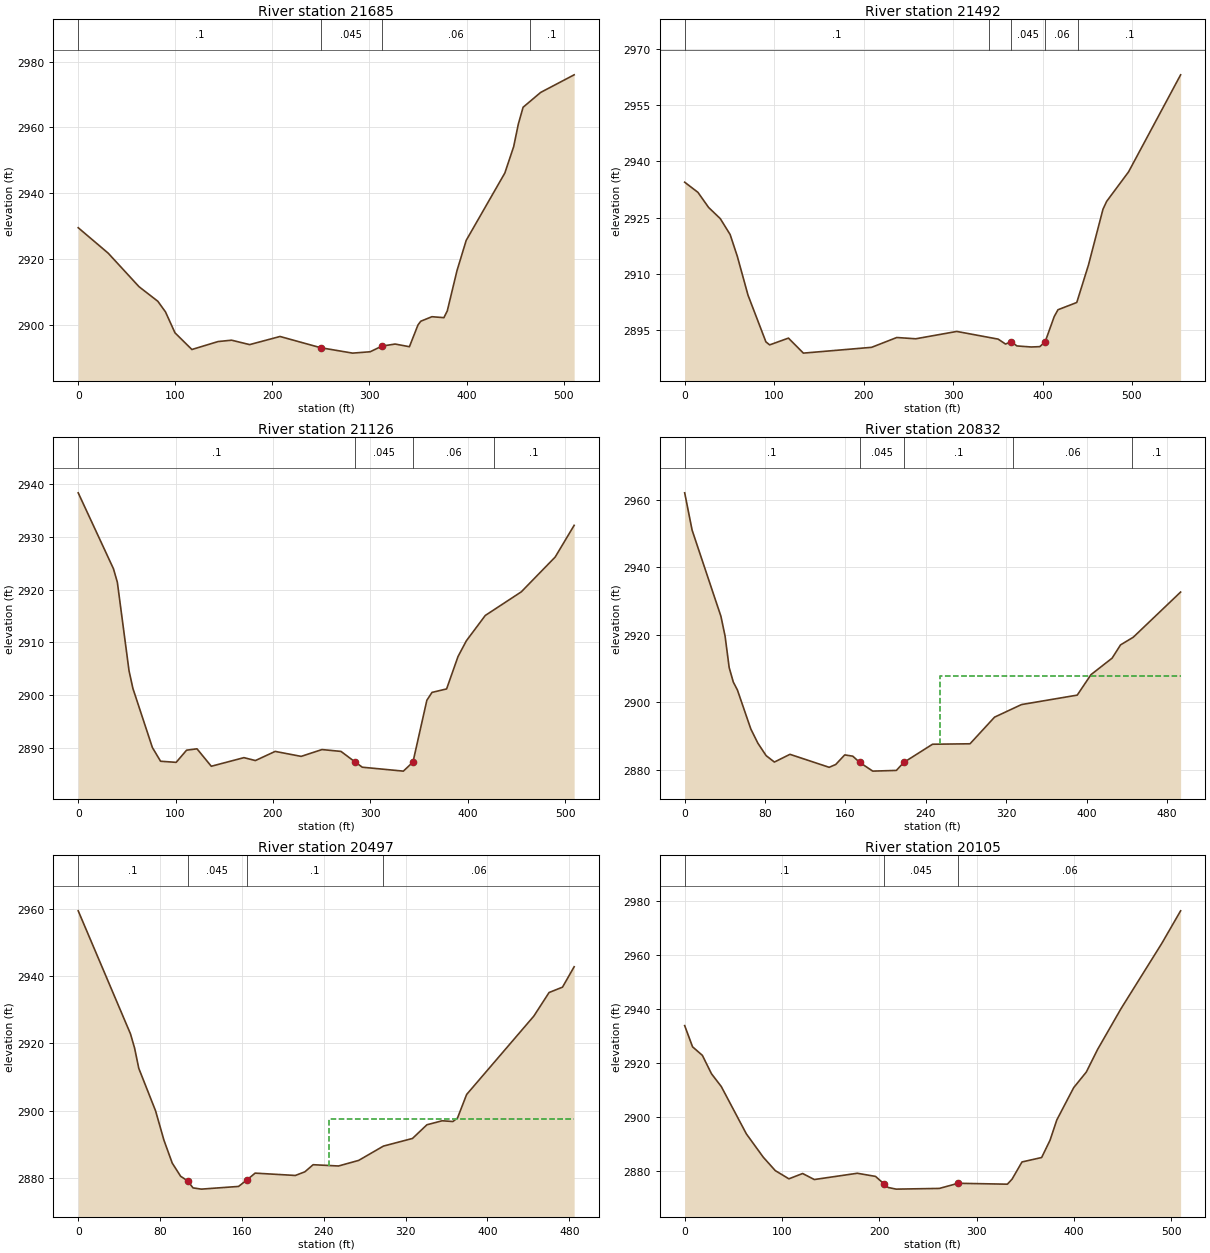
Type RM Length L Ch R = 1 ,21685   ,192.6,192.6,192.6
XS GIS Cut Line= 4
2380027.89562117654856.455380607 2379906.2699374 654629.24256477
2379855.48119033 654602.511645262379743.21132839654442.126128198
#Sta/Elev= 30
       0 2929.48    30.9 2921.74    62.7 2911.54      82 2907.13    89.9  2903.9
    99.7 2897.53   117.1 2892.46   144.1 2894.88     158 2895.29   176.6 2893.95
   207.9 2896.42   249.72893.009   282.7 2891.36   300.8 2891.78   312.92893.496
   326.5 2894.12   341.2 2893.31     350 2899.91   352.9 2901.06   364.4 2902.43
   376.7 2902.14   380.2 2904.19   390.2 2916.43   399.7 2925.64   439.5 2946.11
   448.6 2954.14   453.4 2960.99   458.3  2966.1   476.4 2970.61   510.9 2975.96
#Mann= 4 ,-1,0
       0      .1       0   249.7    .045       0   312.9     .06       0
  465.11      .1       0
Bank Sta=249.7,312.9
XS Rating Curve= 0 ,0
Exp/Cntr(USF)=0,0
Exp/Cntr=0.3,0.1

Type RM Length L Ch R = 1 ,21492   ,365.7,365.7,365.7
XS GIS Cut Line= 4
2380103.17412174654863.9881644942380103.17412174654773.750759921
2379988.32651592654401.3163810472379939.10611343 654345.53325822
#Sta/Elev= 30
       0 2934.43    14.8 2931.73    26.8 2927.68    39.8 2924.71    50.8 2920.47
    58.8 2914.68    70.8 2904.28    90.8 2891.81      95    2891     116 2892.81
   132.7  2888.8     209 2890.35   237.1 2892.97   258.3 2892.63   304.2 2894.59
   350.4 2892.54   358.7 2891.22     365 2891.85   371.4 2890.72   387.4 2890.44
     397 2890.53  402.972891.826   413.1 2898.56   417.3 2900.38   438.3 2902.32
   451.4 2912.34   467.6 2927.21   471.7 2929.31   496.2 2937.19   554.4  2963.1
#Mann= 5 ,-1,0
       0      .1       0  340.24     .06       0     365    .045       0
  402.97     .06       0  440.24      .1       0
Bank Sta=365,402.97
XS Rating Curve= 0 ,0
Exp/Cntr(USF)=0,0
Exp/Cntr=0.3,0.1

Type RM Length L Ch R = 1 ,21126   ,294.4,294.4,294.4
XS GIS Cut Line= 4
2380164.92951684654881.4240516712380165.73512474654798.116527673
 2380360.7608948654578.5098300262380406.22340648654454.195447174
#Sta/Elev= 30
       0  2938.3    36.2 2923.94    40.2 2921.39    52.2 2904.64    56.2 2901.29
    76.2 2890.12    84.6 2887.53   100.6 2887.32   111.3 2889.62     122 2889.88
   136.7 2886.58   170.2 2888.21     182 2887.66   202.3 2889.39     229 2888.45
   250.4 2889.74   269.9 2889.39  284.262887.413   291.8  2886.4     334 2885.66
  343.842887.374   358.1 2899.06   363.4 2900.55   378.4 2901.21   390.1 2907.33
   398.6 2910.29   418.1  2915.1   455.1 2919.57   489.9 2926.15   509.4 2932.15
#Mann= 4 ,-1,0
       0      .1       0  284.26    .045       0  343.84     .06       0
  427.02      .1       0
Bank Sta=284.26,343.84
XS Rating Curve= 0 ,0
Exp/Cntr=0.3,0.1

Type RM Length L Ch R = 1 ,20832   ,335,335,335
XS GIS Cut Line= 4
2380445.17092158655004.4513435372380465.85919709654909.429643991
2380653.22754201654677.480574682 2380685.3484726654584.750283825
#Sta/Elev= 30
       0 2961.99     7.4 2950.93    36.1 2925.38    40.2 2919.56    44.3  2910.2
    48.4 2905.92    52.5 2903.56    65.8 2892.04    72.9 2887.78    81.1 2884.11
    89.3 2882.22   104.8 2884.51   143.8 2880.66   150.3 2881.49   159.3 2884.34
   167.3 2883.96  174.252882.106   187.2 2879.53   210.7 2879.74  218.012882.094
   246.7  2887.5     284 2887.63   308.4 2895.52   335.2 2899.25   390.7 2902.05
   404.4 2908.12   425.4    2913   433.8 2916.93   446.5 2919.21   493.6 2932.59
#Mann= 5 ,-1,0
       0      .1       0  174.25    .045       0  218.01      .1       0
  327.25     .06       0  445.42      .1       0
#XS Ineff= 2 , 0
                           254.1         2907.81
Permanent Ineff=
       F       F
Bank Sta=174.25,218.01
XS Rating Curve= 0 ,0
Exp/Cntr=0.3,0.1

Type RM Length L Ch R = 1 ,20497   ,391.5,391.5,391.5
XS GIS Cut Line= 4
2380783.92957497655123.1372890822380804.17010966655026.945432392
2380839.40856369654795.2330710532380906.73234163654658.880720079
#Sta/Elev= 30
       0 2959.36    51.1 2922.81    55.1  2918.6    59.2 2912.59    75.6 2899.97
    83.8 2891.23    91.9 2884.44   100.1 2880.53   106.9 2879.17   112.2 2877.08
   120.3 2876.71   156.7 2877.51   164.92879.445   172.9 2881.46   212.2 2880.77
   221.5 2881.85   229.6 2883.96   254.4 2883.58   274.1 2885.24   298.3 2889.49
   326.7 2891.76   340.8 2895.82   355.7 2897.01   366.2 2896.79   370.7 2897.83
   379.6 2904.81   445.3  2928.1   460.2  2935.1   473.3 2936.69   484.7 2942.75
#Mann= 4 ,-1,0
       0      .1       0   106.9    .045       0   164.9      .1       0
   298.3     .06       0
#XS Ineff= 2 , 0
                          244.81         2897.68
Permanent Ineff=
       F       F
Bank Sta=106.9,164.9
XS Rating Curve= 0 ,0
Exp/Cntr(USF)=0,0
Exp/Cntr=0.3,0.1

Type RM Length L Ch R = 1 ,20105   ,201.3,201.3,201.3
XS GIS Cut Line= 4
2381084.63038358655248.7096542532381190.38587145655074.909844909
 2381200.0464417655002.1388919372381332.58424015654810.855253683
#Sta/Elev= 30
       0 2933.96     8.1 2926.12    18.2 2922.95    27.5 2916.18    37.6 2911.43
    63.4  2893.9    80.8 2885.26    93.1 2880.32   107.1 2877.28   121.2 2879.25
   133.2 2877.02   177.4 2879.34   196.1 2878.18   204.82875.419   209.2 2874.07
   217.3 2873.47   261.7 2873.73     2812875.631   331.6  2875.3   336.4 2877.16
   346.6 2883.52   366.8 2885.17   375.4 2891.54   382.4 2899.08   399.7    2911
   412.7 2916.79   424.2 2925.09   448.3  2940.2   490.4 2964.47   509.6 2976.43
#Mann= 3 ,-1,0
       0      .1       0   204.8    .045       0     281     .06       0
Bank Sta=204.8,281
XS Rating Curve= 0 ,0
Exp/Cntr=0.3,0.1

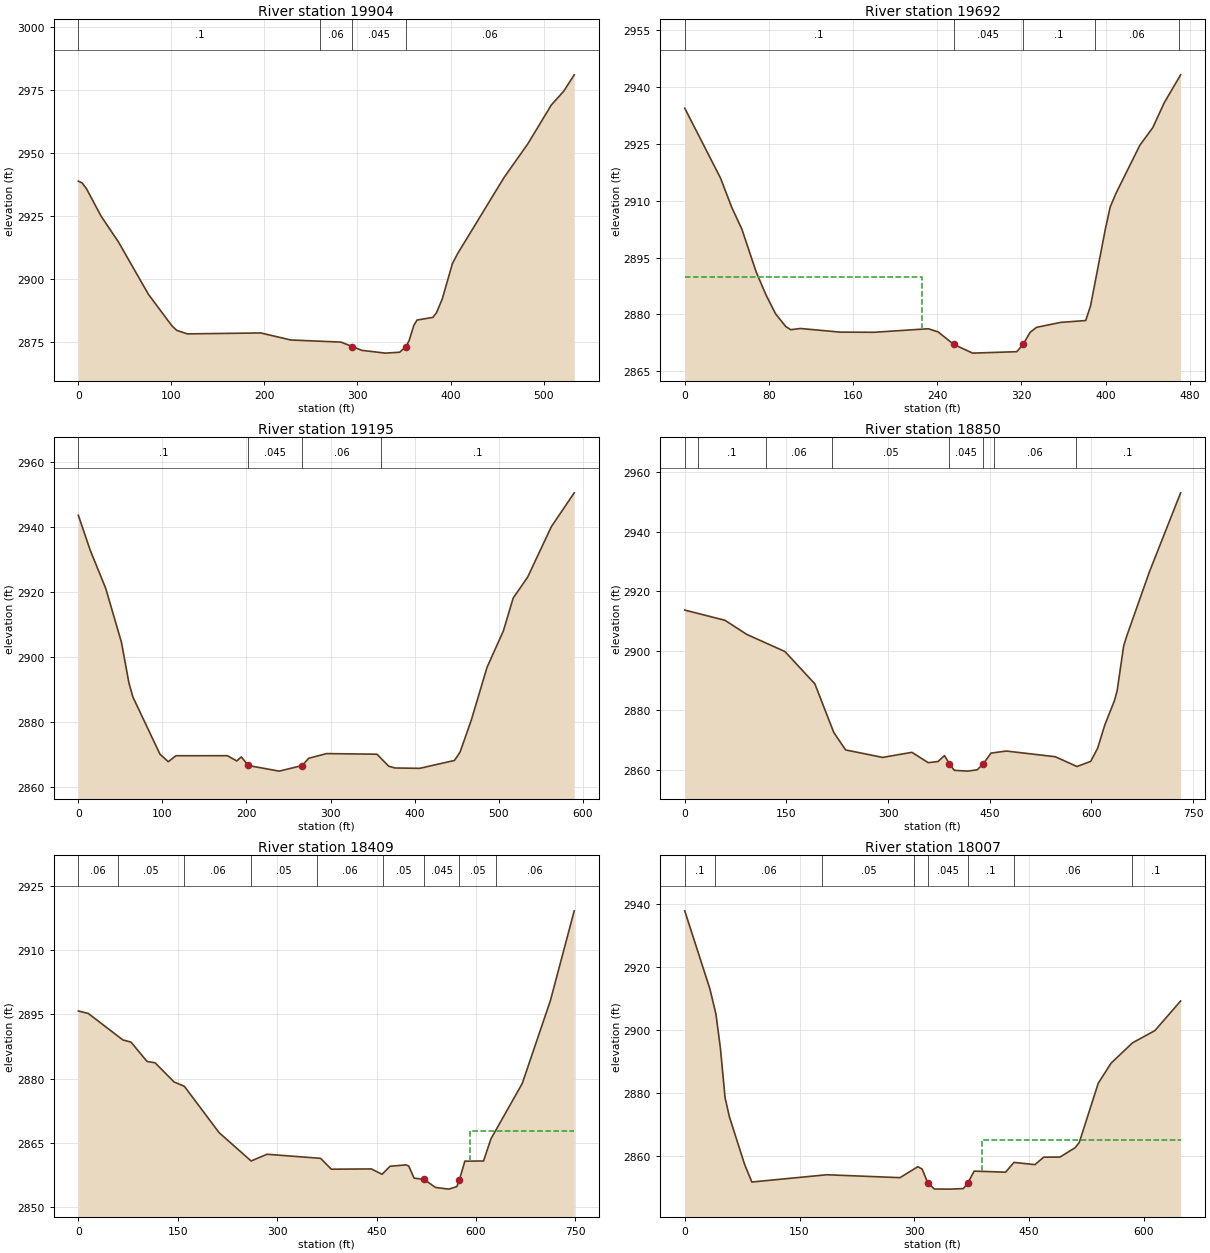
Type RM Length L Ch R = 1 ,19904   ,212.5,212.5,212.5
XS GIS Cut Line= 2
2381194.70025779655328.2561099622381524.82711375654909.917219627
#Sta/Elev= 30
       0 2938.83     3.9 2938.21     8.9 2935.76    24.3 2925.02    43.1 2914.68
    75.3 2893.87   100.7 2881.28   105.8 2879.52   117.2 2878.13   196.1  2878.5
   228.2 2875.71   282.3 2874.86   294.4 2873.09   304.6 2871.59     330 2870.48
   345.3 2870.84  352.23 2873.09   355.5 2875.51   360.6 2881.55     364 2883.63
     381 2884.69   384.9 2886.54   391.2 2892.12     402 2906.08   407.7  2910.1
   457.4 2940.24   482.9 2953.59   508.4 2969.17   521.6 2974.59   532.9 2981.11
#Mann= 4 ,-1,0
       0      .1       0     260     .06       0   294.4    .045       0
  352.23     .06       0
Bank Sta=294.4,352.23
XS Rating Curve= 0 ,0
Exp/Cntr(USF)=0,0
Exp/Cntr=0.3,0.1

Type RM Length L Ch R = 1 ,19692   ,496.9,496.9,496.9
XS GIS Cut Line= 2
2381403.63324981655459.3278771732381647.39324981655055.919877173
#Sta/Elev= 30
       0 2934.42      34 2915.98    44.6 2908.31    54.4 2902.44    67.9 2891.22
    77.3 2885.13    86.4 2880.15      96 2876.83   100.7 2875.99     110 2876.31
   147.6 2875.35   180.1 2875.31   231.5 2876.24   240.9  2875.4  255.542872.131
   273.6 2869.81   315.6 2870.19  321.642872.132   328.2 2875.27   334.3 2876.61
   357.4 2877.92   381.1 2878.41   385.7 2882.28   399.8 2902.57   404.4 2908.38
   409.8 2911.92   432.5 2924.61   444.8 2929.27   455.8 2935.87   471.3 2943.21
#Mann= 5 ,-1,0
       0      .1       0  255.54    .045       0  321.64      .1       0
     390     .06       0     470      .1       0
#XS Ineff= 2 , 0
          225.87 2889.92
Permanent Ineff=
       F       F
Bank Sta=255.54,321.64
XS Rating Curve= 0 ,0
Exp/Cntr=0.3,0.1

Type RM Length L Ch R = 1 ,19195   ,344.4,344.4,344.4
XS GIS Cut Line= 2
2381627.89741289655734.8931207482382139.76695767655441.639766818
#Sta/Elev= 30
       0 2943.72    14.1 2932.95    32.6 2921.14    51.3 2904.51    60.2 2891.97
    64.9 2887.64    97.1 2870.01     107 2867.68   116.1 2869.52   177.3 2869.53
   188.5  2867.9   193.9 2869.17  202.08 2866.51   238.9 2864.77   266.32866.495
     274 2868.73   295.4 2870.18   355.3 2869.99   369.1 2866.31   376.6 2865.74
     406 2865.63   447.5 2868.07   454.1 2870.64   467.5 2880.54   486.2 2896.81
   505.6 2908.02   517.3 2918.17   534.5 2924.62   562.7 2940.19   589.9 2950.63
#Mann= 4 ,-1,0
       0      .1       0  202.08    .045       0   266.3     .06       0
     360      .1       0
Bank Sta=202.08,266.3
XS Rating Curve= 0 ,0
Exp/Cntr=0.3,0.1

Type RM Length L Ch R = 1 ,18850   ,441,441,441
XS GIS Cut Line= 3
2381628.98854161656017.3968782712381825.09980922656035.622333254
2382270.13087909655739.075565766
#Sta/Elev= 30
       0 2913.69    59.4 2910.25    91.6  2905.5   147.8 2899.76     192 2888.89
   219.9 2872.57   237.4 2866.68     292 2864.17   335.2 2865.88   359.3  2862.4
   373.7 2862.79   383.3 2864.76   390.62861.978   397.7 2859.84   417.3 2859.56
   431.7 2860.01   440.6 2862.06   451.9 2865.62   474.6 2866.31   546.7  2864.4
   578.8 2861.11     599 2862.84   609.2 2867.23   619.7 2874.99   634.2 2883.35
   638.1 2886.64   647.7  2901.7   652.5 2905.15   685.5 2926.43   731.7 2953.09
#Mann= 8 ,-1,0
       0     .06       0      20      .1       0     120     .06       0
  216.96     .05       0   390.6    .045       0   440.6     .05       0
  456.96     .06       0  576.96      .1       0
Bank Sta=390.6,440.6
XS Rating Curve= 0 ,0
Exp/Cntr=0.3,0.1

Type RM Length L Ch R = 1 ,18409   ,402.6,402.6,402.6
XS GIS Cut Line= 3
2381585.31611451656387.0344767572382250.15552532 656306.56127551
2382320.45574603 656271.88615684
#Sta/Elev= 30
       0 2895.79      15 2895.22    67.3 2889.02    79.4 2888.53   103.6 2884.01
   115.8 2883.68   144.4 2879.21     160 2878.18   212.4 2867.35   260.7 2860.73
   284.6  2862.3   365.5 2861.35   381.6 2858.81   442.1 2858.87   458.2 2857.62
   470.3  2859.5   494.4 2859.81   498.5 2859.54   506.5 2856.72   521.8 2856.41
   538.8 2854.54   558.9 2854.15     571 2854.74     575 2856.39   583.1 2860.69
   611.3 2860.73   622.4 2865.88   669.7 2878.85   712.1 2898.19   748.1 2919.21
#Mann= 9 ,-1,0
       0     .06       0      60     .05       0     160     .06       0
     260     .05       0     360     .06       0     460     .05       0
   521.8    .045       0     575     .05       0     630     .06       0
#XS Ineff= 2 , 0
                          590.16         2867.73
Permanent Ineff=
       F       F
Bank Sta=521.8,575
XS Rating Curve= 0 ,0
Exp/Cntr=0.3,0.1

Type RM Length L Ch R = 1 ,18007   ,377.2,377.2,377.2
XS GIS Cut Line= 3
2382017.44987925656924.9703900232382393.60280083656574.377947279
2382430.40274603656445.767476757
#Sta/Elev= 30
       0 2937.73    32.9 2913.02    40.8 2905.01    46.6  2894.3    52.7 2878.58
    58.4 2872.51    78.2 2857.49    87.7 2851.89   185.7 2854.19   281.3 2853.27
   304.6 2856.74   310.3 2855.96  317.66 2851.55   326.3 2849.68   345.8 2849.64
     364 2849.81   370.1 2851.63   378.2 2855.34   419.3 2855.01   430.2  2858.1
   457.6 2857.39     469 2859.75   490.4 2859.79   510.1 2862.74   515.5 2864.38
   540.4 2883.18   557.1  2889.5   585.2 2895.96   614.3  2899.8     648 2909.19
#Mann= 8 ,-1,0
       0      .1       0      40     .06       0     180     .05       0
     300      .1       0  317.66    .045       0   370.1      .1       0
     430     .06       0   584.2      .1       0
#XS Ineff= 2 , 0
                          388.89         2865.33
Permanent Ineff=
       F       F
Bank Sta=317.66,370.1
XS Rating Curve= 0 ,0
Exp/Cntr=0.3,0.1

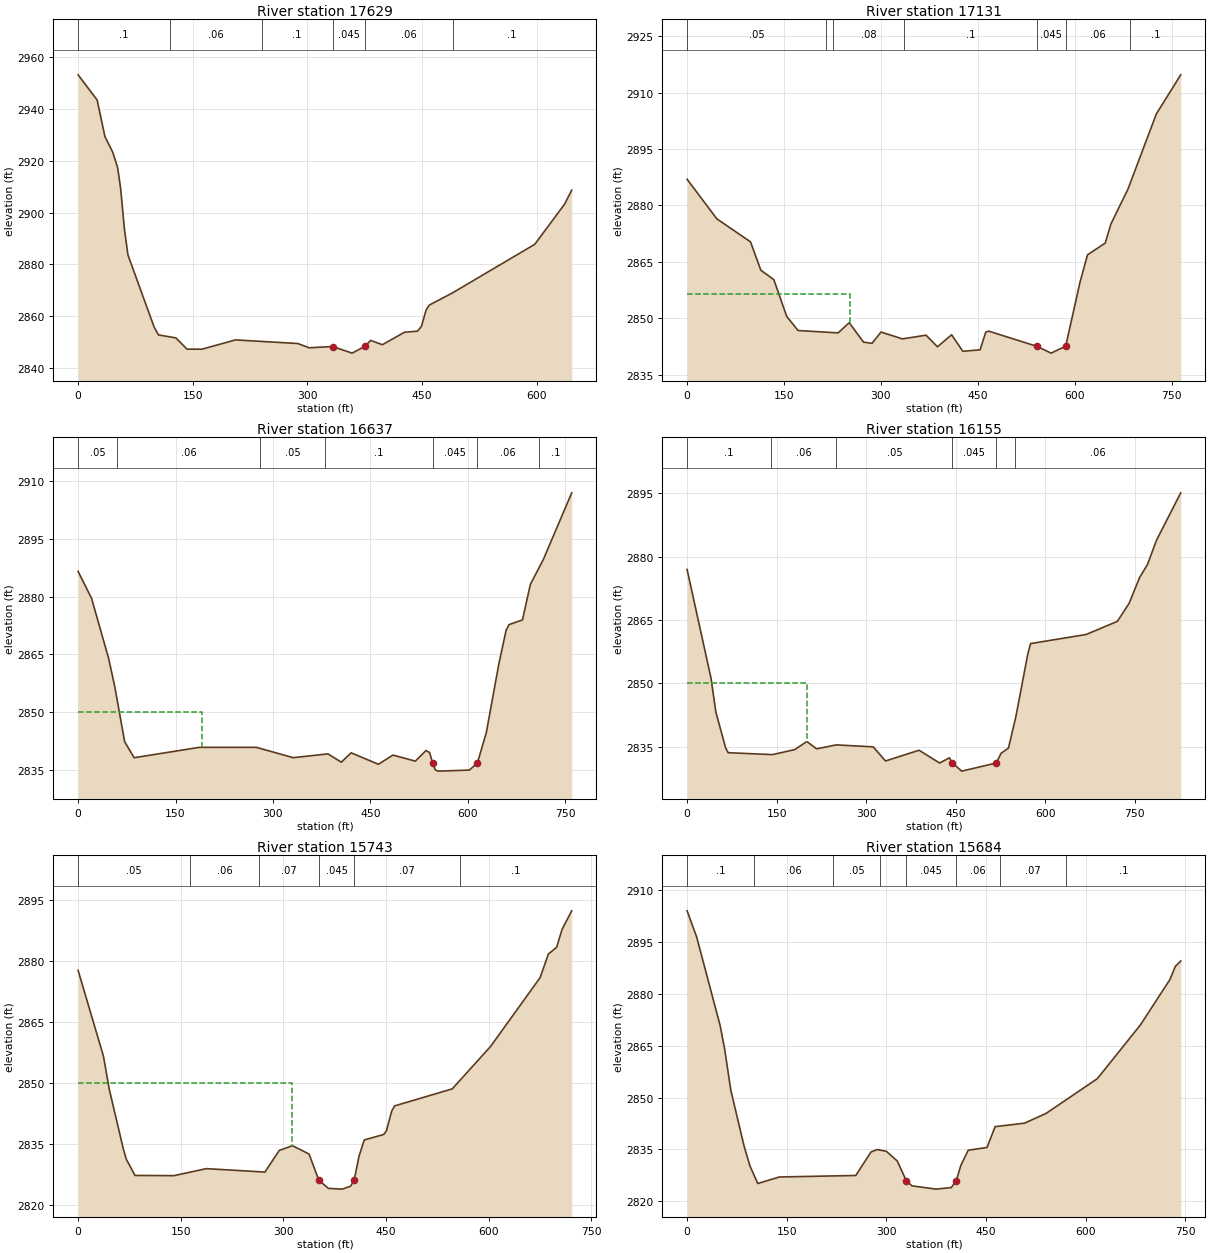
Type RM Length L Ch R = 1 ,17629   ,498.4,498.4,498.4
XS GIS Cut Line= 2
2382244.68722266657189.3617819772382750.01668827656787.395161607
#Sta/Elev= 30
       0 2953.13    24.9 2943.42    35.1 2929.31    45.3 2923.28    51.7 2917.35
    55.6 2909.45    60.7  2893.4    65.2 2883.65    99.4 2855.86   105.1  2852.8
   127.9 2851.64   142.5  2847.3     162 2847.29   205.9 2850.87   287.3 2849.48
   302.3 2847.84  332.91 2848.31   358.5 2845.77  374.942848.337   382.7 2850.68
     398 2849.01   426.8 2853.81     444 2854.24   449.1  2856.1   455.2 2862.39
   459.3 2864.29     490 2869.05   597.4 2887.76   636.4 2903.26   645.7 2908.63
#Mann= 6 ,-1,0
       0      .1       0     120     .06       0     240      .1       0
  332.91    .045       0  374.94     .06       0     490      .1       0
Bank Sta=332.91,374.94
XS Rating Curve= 0 ,0
Exp/Cntr(USF)=0,0
Exp/Cntr=0.3,0.1

Type RM Length L Ch R = 1 ,17131   ,493.9,493.9,493.9
XS GIS Cut Line= 3
2382314.27363776657525.6524406652382469.46039405 657514.21643844
2383022.39601663657259.991442744
#Sta/Elev= 30
       0 2886.98      46 2876.45    98.2 2870.31   114.2 2862.76   134.3 2860.25
   154.3 2850.44   171.8 2846.71   233.8 2846.08     251 2848.79   273.1 2843.62
   286.3  2843.3   300.2  2846.3   333.4 2844.48   369.9 2845.47   387.6 2842.38
   409.5 2845.58   426.9 2841.18   453.6 2841.57   462.4 2846.29   466.8 2846.55
   541.5  2842.5   563.6 2840.69  586.142842.549   608.1 2859.46   619.9 2866.86
   647.3 2869.99   656.1 2875.06   682.5 2884.35   726.5 2904.39   764.2 2914.78
#Mann= 7 ,-1,0
       0     .05       0  215.61     .06       0  225.61     .08       0
  335.61      .1       0   541.5    .045       0  586.14     .06       0
  685.61      .1       0
#XS Ineff= 2 , 0
          252.09 2856.46
Permanent Ineff=
       F       F
Bank Sta=541.5,586.14
XS Rating Curve= 0 ,0
Exp/Cntr=0.3,0.1

Type RM Length L Ch R = 1 ,16637   ,481.7,481.7,481.7
XS GIS Cut Line= 2
2382477.22811867658040.7467751322383172.42062944657733.397571806
#Sta/Elev= 30
       0 2886.55    20.7 2879.57      47 2863.97    56.5 2856.61    71.7 2842.33
    86.3 2838.18   186.9 2840.88   274.4 2840.88   331.2 2838.19   384.7 2839.18
   405.3 2837.02   420.4 2839.45   462.4 2836.48   484.8 2838.87   519.3 2837.29
   535.7 2840.05   541.2 2839.53  545.962836.795   549.9 2835.04   554.3  2834.7
   602.4 2834.97  614.872836.804   628.6 2844.72   647.9 2862.56   659.2 2871.36
   663.6 2872.74   684.3 2873.96   696.4 2883.19   716.1 2889.54   760.1 2906.95
#Mann= 7 ,-1,0
       0     .05       0      60     .06       0     280     .05       0
     380      .1       0  545.96    .045       0  614.87     .06       0
     710      .1       0
#XS Ineff= 2 , 0
           191.4    2850
Permanent Ineff=
       F       F
Bank Sta=545.96,614.87
XS Rating Curve= 0 ,0
Exp/Cntr=0.3,0.1

Type RM Length L Ch R = 1 ,16155   ,412.1,412.1,412.1
XS GIS Cut Line= 3
2382589.34495578658360.5217237542383177.93855431658215.928048391
2383313.03716884658041.158096793
#Sta/Elev= 30
       0 2876.97      40 2851.24    48.2 2843.16    64.6 2834.68    68.8 2833.55
     143 2833.09   180.4 2834.29   200.6 2836.19   217.1 2834.46     250  2835.4
   311.8 2834.93   332.4 2831.59   388.7 2834.13     423  2831.1   439.5 2832.33
  444.592831.101   460.1 2829.18  517.92  2831.1     526  2833.4   538.4 2834.65
   550.8 2842.08   570.5 2856.73   575.4  2859.4   668.6 2861.56   720.9 2864.68
   740.6 2868.96   757.9    2875   771.4 2878.18   786.3 2883.86     827 2895.13
#Mann= 6 ,-1,0
       0      .1       0     140     .06       0     250     .05       0
  444.59    .045       0  517.92      .1       0     550     .06       0
#XS Ineff= 2 , 0
           201.3    2850
Permanent Ineff=
       F       F
Bank Sta=444.59,517.92
XS Rating Curve= 0 ,0
Exp/Cntr=0.3,0.1

Type RM Length L Ch R = 1 ,15743   ,59.4,59.4,59.4
XS GIS Cut Line= 4
2382672.76755002658648.4304147712382762.57380221658620.472908957
2383143.93584091658669.4545354712383386.23973668658650.460164745
#Sta/Elev= 30
       0 2877.66    37.1 2856.56    45.5  2848.5    66.4  2833.6    70.6 2831.23
    83.2 2827.29     140 2827.24   187.6 2828.96   273.1 2828.12   294.1 2833.44
   313.4  2834.6   337.6 2832.55  351.882826.134   365.9 2824.11     386 2823.93
   398.1 2824.63   403.5 2826.09   410.6 2831.98   418.3    2836   446.8 2837.36
   450.6 2838.23   458.6 2843.16   462.7 2844.37     547 2848.56   603.2 2859.02
   675.4 2875.88   687.4 2881.65   699.5 2883.33   707.5 2887.73   721.6 2892.28
#Mann= 6 ,-1,0
       0     .05       0  164.06     .06       0  264.06     .07       0
  351.88    .045       0   403.5     .07       0  558.55      .1       0
#XS Ineff= 2 , 0
           312.6    2850
Permanent Ineff=
       F       F
Bank Sta=351.88,403.5
XS Rating Curve= 0 ,0
Exp/Cntr=0.3,0.1

Type RM Length L Ch R = 1 ,15684   ,56.1,56.1,56.1
XS GIS Cut Line= 4
2382739.69245291658813.8303215812383007.36506103658660.776506817
2383073.88553093658751.676755992 2383392.2256912658701.318194001
#Sta/Elev= 30
       0 2904.01    14.4 2896.44    49.7 2870.87    56.5 2864.07    65.8 2852.14
    85.8 2835.95    94.6 2830.23   106.4 2825.12   138.8 2827.01     254 2827.45
     277 2834.26   286.2 2834.94   300.1 2834.44   316.5 2831.63     330 2825.95
   338.6 2824.45     375  2823.5   397.8 2823.95  405.27 2825.92   412.2 2830.35
   423.3 2834.75   451.6 2835.55   463.8 2841.57   508.3 2842.59   540.6 2845.42
   617.7 2855.45   682.5 2870.98     727 2884.11   735.1 2887.93   743.3 2889.48
#Mann= 8 ,-1,0
       0      .1       0     100     .06       0     220     .05       0
     290     .07       0     330    .045       0  405.27     .06       0
  470.98     .07       0  570.98      .1       0
Bank Sta=330,405.27
XS Rating Curve= 0 ,0
Exp/Cntr(USF)=0,0
Exp/Cntr=0.3,0.1