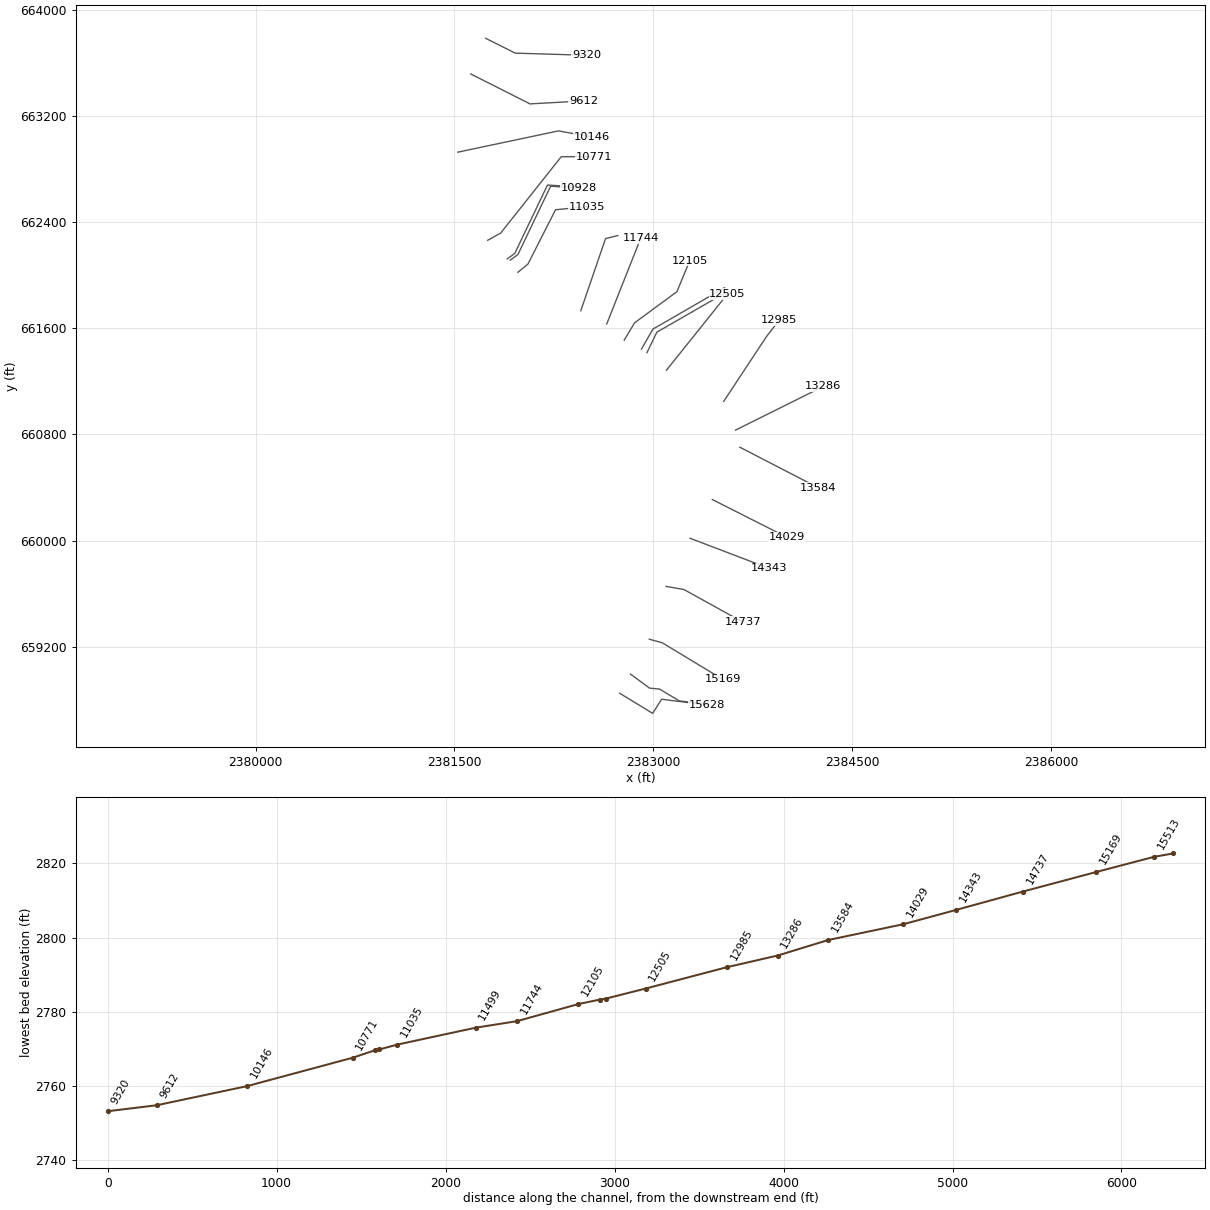
HEC-RAS study GNDYCK_1.prj: GNDYCK_1

--- GNDYCK_1.g01 (geometry) --- (continued)

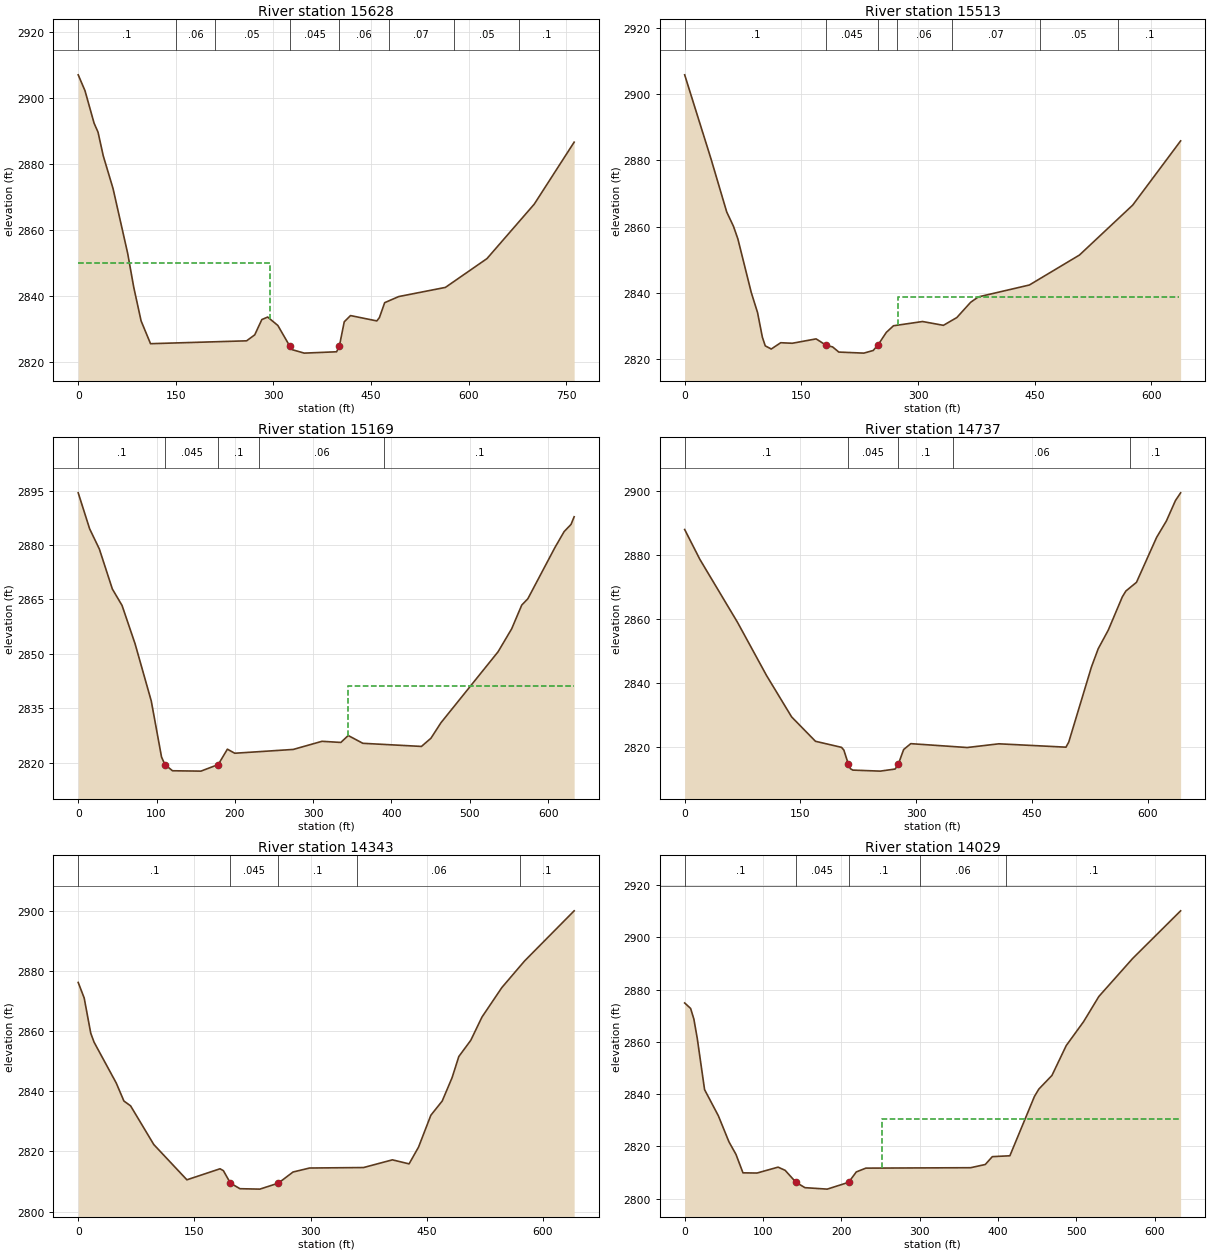
Type RM Length L Ch R = 1 ,15628   ,114.4,114.4,114.4
XS GIS Cut Line= 4
2382747.32180189658849.0363315692382995.83561408658697.535932691
2383062.83340244658804.1820087372383405.06576672658761.032234048
#Sta/Elev= 30
       0  2907.1    10.4  2902.3    24.4 2892.43    30.5 2889.68    38.5 2882.51
    53.5 2872.62      76 2852.95    85.3 2842.69    96.6 2832.48   111.1 2825.56
   258.7 2826.43   271.2 2828.25   282.1 2832.88   291.1 2833.64   306.7 2831.09
  324.73 2824.92   328.8 2823.74   347.3  2822.7     397 2823.11   401.3 2824.93
   408.7  2832.2   418.3 2834.09   458.7 2832.47   462.7 2833.46   470.8    2838
   492.5 2839.86   564.1 2842.63     628 2851.37   700.6 2867.88   761.9 2886.68
#Mann= 8 ,-1,0
       0      .1       0     150     .06       0     210     .05       0
  324.73    .045       0   401.3     .06       0     477     .07       0
     577     .05       0     677      .1       0
#XS Ineff= 2 , 0
           295.4    2850
Permanent Ineff=
       F       F
Bank Sta=324.73,401.3
XS Rating Curve= 0 ,0
Exp/Cntr(USF)=0,0
Exp/Cntr=0.3,0.1

Type RM Length L Ch R = 1 ,15513   ,344,344,344
XS GIS Cut Line= 5
2382828.70681798658993.3411242322382972.18197896658887.723977405
2383046.81661292658880.9943836732383196.33786024658791.774041207
2383405.37287849658767.269836262
#Sta/Elev= 30
       0 2905.78      34  2880.3    54.1 2864.35    62.7 2860.09    68.4 2856.26
    85.6  2840.1    93.7 2834.02    99.9 2826.59   103.6 2823.98   111.3 2823.02
   123.5 2824.92   138.4 2824.76     169 2826.08   182.2 2824.11   190.2 2823.66
   198.2  2822.1   230.4 2821.78   242.4 2822.58   248.42824.182   259.3 2828.05
   268.5 2830.04   305.9 2831.32   332.7 2830.17   349.9 2832.51   367.7 2837.12
   377.6 2838.75   443.2 2842.34   507.6 2851.38   576.1 2866.46   637.7 2885.84
#Mann= 7 ,-1,0
       0      .1       0   182.2    .045       0   248.4      .1       0
  273.09     .06       0  343.09     .07       0  457.21     .05       0
  557.21      .1       0
#XS Ineff= 1 ,-1
  274.13   635.3 2838.65
Permanent Ineff=
       F
Bank Sta=182.2,248.4
XS Rating Curve= 0 ,0
Exp/Cntr(USF)=0,0
Exp/Cntr=0.3,0.1

Type RM Length L Ch R = 1 ,15169   ,432.8,432.8,432.8
XS GIS Cut Line= 3
2382970.07777056659256.3412110322383067.67651371659229.949122524
 2383523.0735625 658954.55443644
#Sta/Elev= 30
       0  2894.4    14.6 2884.47      27 2878.91    43.6 2867.88      56 2863.34
    72.6 2852.79    93.3    2837   106.4 2821.56  110.712819.482   120.4 2817.77
   156.7 2817.67  178.782819.482   190.5 2823.72   199.9  2822.6   274.6 2823.65
   311.3 2825.89   335.4 2825.58   344.8 2827.49   363.5 2825.34   438.3 2824.48
   450.4 2826.73   463.2 2831.01   536.1 2850.56   553.5  2856.9   566.4 2863.46
   574.1 2865.17   608.8 2879.34   620.5 2883.71   629.3 2885.69   633.3  2887.8
#Mann= 5 ,-1,0
       0      .1       0  110.71    .045       0  178.78      .1       0
   231.1     .06       0   391.1      .1       0
#XS Ineff= 2 , 0
                          344.26         2841.16
Permanent Ineff=
       F       F
Bank Sta=110.71,178.78
XS Rating Curve= 0 ,0
Exp/Cntr=0.3,0.1

Type RM Length L Ch R = 1 ,14737   ,393.5,393.5,393.5
XS GIS Cut Line= 3
2383096.72440635659654.4327111422383231.92808014659630.702652398
2383674.21019337659386.169501842
#Sta/Elev= 30
       0 2887.95    19.7 2878.61    68.5 2858.92   106.1  2842.3   138.6 2829.36
   169.5 2821.74   203.3 2819.84   206.3 2818.98  212.272814.483   214.8 2813.16
     218 2812.73   253.4 2812.41   272.7 2813.06   276.72814.483   283.8 2819.17
     293    2821   366.1 2819.79   407.2 2820.95   494.1  2819.9   497.7 2821.47
   527.1 2844.95   535.9 2850.67   548.9 2856.47   567.2 2866.92   571.8 2868.73
   585.5 2871.44   611.6  2885.5   624.2 2890.59     636    2897   642.7 2899.42
#Mann= 5 ,-1,0
       0      .1       0  212.27    .045       0   276.7      .1       0
  347.27     .06       0  577.27      .1       0
Bank Sta=212.27,276.7
XS Rating Curve= 0 ,0
Exp/Cntr=0.3,0.1

Type RM Length L Ch R = 1 ,14343   ,314.4,314.4,314.4
XS GIS Cut Line= 2
2383276.99686657660017.3584014742383875.34229374659789.740292542
#Sta/Elev= 30
       0 2876.21     7.7 2871.06    16.2 2859.32    20.5 2856.33    49.1 2842.76
      59 2836.78    67.6 2835.18    97.6  2822.3   140.3 2810.58   183.1 2814.25
   187.4 2813.62   196.52809.467   208.8 2807.62   234.5 2807.48  258.312809.466
   277.3 2813.17   298.7  2814.5   368.4 2814.66   405.6 2817.22   427.1 2815.88
   439.3 2821.44   455.2 2832.04   469.9 2836.79   482.7  2844.6   491.3 2851.57
   506.8 2856.99   521.2  2864.7   546.9 2874.52   576.2 2883.36   640.2 2900.03
#Mann= 5 ,-1,0
       0      .1       0   196.5    .045       0  258.31      .1       0
     360     .06       0     570      .1       0
Bank Sta=196.5,258.31
XS Rating Curve= 0 ,0
Exp/Cntr=0.3,0.1

Type RM Length L Ch R = 1 ,14029   ,444.7,444.7,444.7
XS GIS Cut Line= 2
2383445.76537698660308.9412044212384010.74054466660023.600706263
#Sta/Elev= 30
       0 2874.89     7.6 2872.78    11.7 2868.76    16.1 2861.26    25.4  2841.7
      43 2831.68    56.5 2821.71    65.4 2816.95    74.4 2809.84    92.3 2809.76
   119.2 2812.02   128.2  2810.8  142.092806.205   153.5 2804.16   181.9  2803.6
   209.22806.207     219 2810.18   231.2 2811.64   364.9  2811.8   383.6 2813.03
   392.6 2816.04     415 2816.37   446.3 2839.06     452 2841.92   468.7 2847.14
   486.9 2858.56   509.1 2867.74   528.6 2877.39   571.8 2891.96   632.9 2910.17
#Mann= 5 ,-1,0
       0      .1       0  142.09    .045       0   209.2      .1       0
     300     .06       0     410      .1       0
#XS Ineff= 2 , 0
                          251.18          2830.4
Permanent Ineff=
       F       F
Bank Sta=142.09,209.2
XS Rating Curve= 0 ,0
Exp/Cntr=0.3,0.1

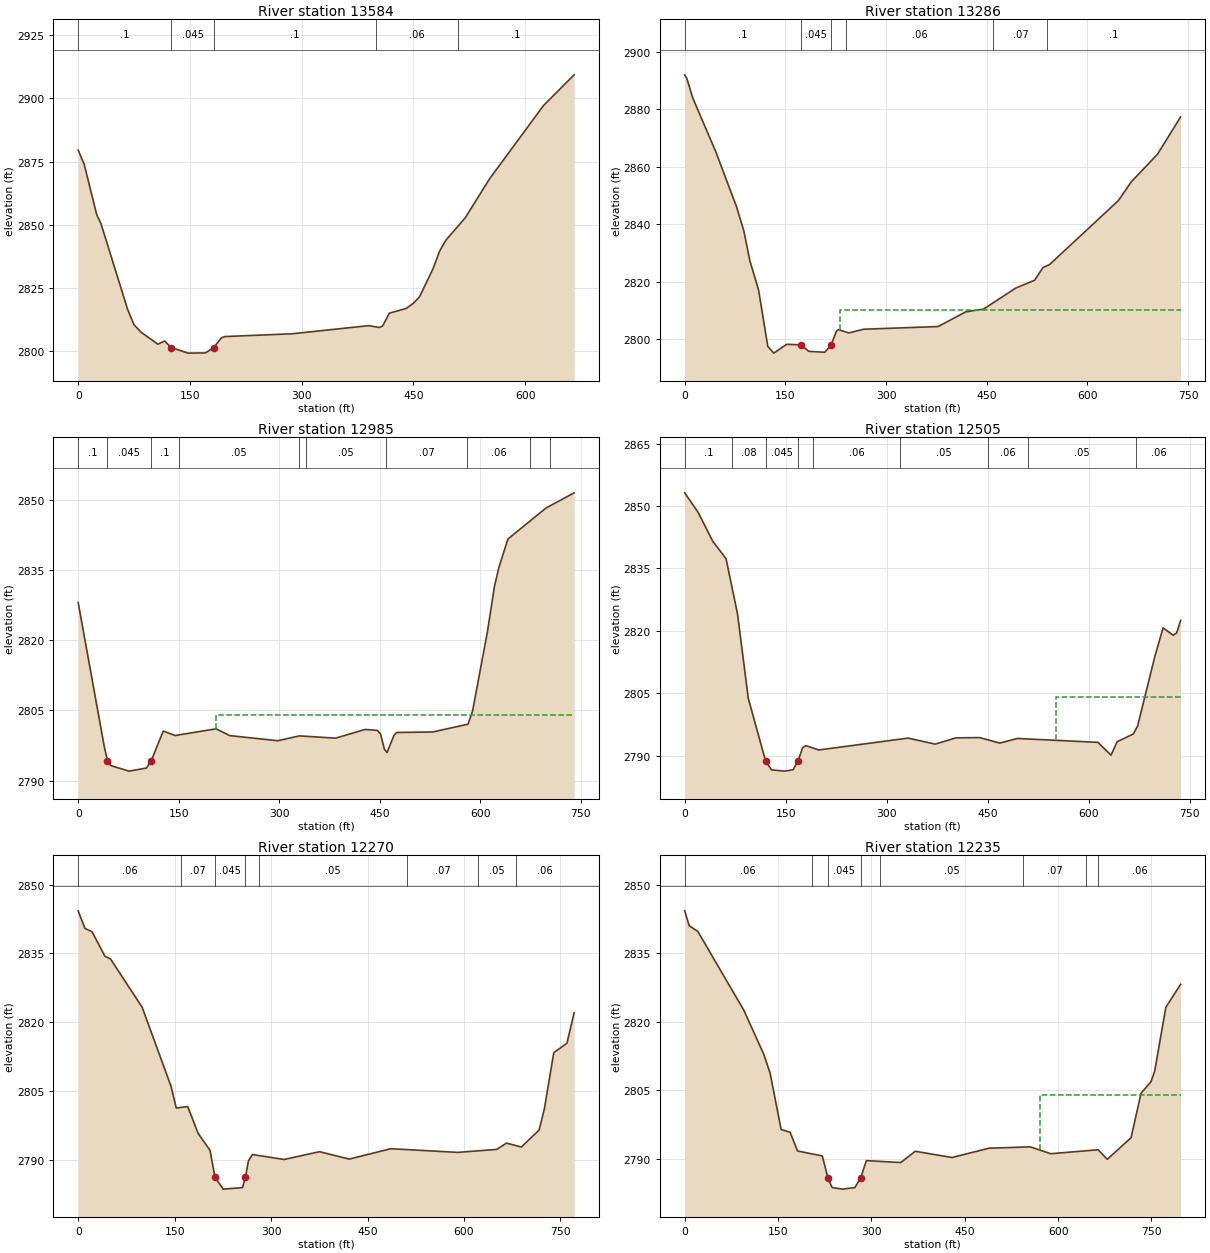
Type RM Length L Ch R = 1 ,13584   ,297.9,297.9,297.9
XS GIS Cut Line= 2
2383653.10675396660703.5020501842384244.69356356660398.153829836
#Sta/Elev= 30
       0 2879.48       8 2873.97    24.8 2854.06    30.5 2850.51    66.3 2816.64
    74.8 2810.57    84.5 2807.57     107 2802.86     116 2804.12   125.12801.507
   147.5 2799.34   170.8 2799.42   181.72801.508   192.5 2805.44     197 2805.88
     287 2806.98     390 2810.19   404.1 2809.47   408.6 2810.05   417.6 2815.11
   440.1 2816.97   449.8 2818.99   458.3 2821.68   476.1 2832.55   485.1 2839.63
   493.4 2843.88   519.6 2852.82   552.6 2868.36   624.6 2897.13   665.7 2909.25
#Mann= 5 ,-1,0
       0      .1       0   125.1    .045       0   181.7      .1       0
     400     .06       0     510      .1       0
Bank Sta=125.1,181.7
XS Rating Curve= 0 ,0
Exp/Cntr=0.3,0.1

Type RM Length L Ch R = 1 ,13286   ,301.2,301.2,301.2
XS GIS Cut Line= 2
2383621.28014376660832.5176927262384282.95359293661161.103827348
#Sta/Elev= 30
       0 2891.92     3.2 2890.65    12.2 2883.78    46.5 2865.09    77.3 2846.02
    88.1 2837.68      97 2827.38   110.1 2817.11   123.8 2797.55   132.7 2795.17
   151.9 2798.23   173.5 2798.05   184.7 2795.79   208.7 2795.47  218.262798.106
   226.3 2802.91   229.4 2803.33   244.4 2802.19   266.7 2803.48   377.6 2804.41
   418.6 2809.51   445.4 2810.49   492.9 2817.75   521.3 2820.51   533.8 2824.93
   543.6 2825.97   646.3 2848.24   665.1 2854.66   704.4 2864.32   738.8 2877.27
#Mann= 6 ,-1,0
       0      .1       0   173.5    .045       0  218.26      .1       0
     240     .06       0     460     .07       0     540      .1       0
#XS Ineff= 2 , 0
                             231            2810
Permanent Ineff=
       F       F
Bank Sta=173.5,218.26
XS Rating Curve= 0 ,0
Exp/Cntr(USF)=0,0
Exp/Cntr=0.3,0.1

Type RM Length L Ch R = 1 ,12985   ,479.8,479.8,479.8
XS GIS Cut Line= 3
 2383531.5256744661048.608356169 2383853.6593733661536.232264363
2383949.03643573661659.215828637
#Sta/Elev= 30
       0 2828.06      39 2797.17   43.642794.265    48.6  2793.2    75.9 2792.02
   101.9 2792.68  109.062794.263   126.9 2800.59   144.5 2799.64   205.8 2801.07
   226.1 2799.62   297.9 2798.52     330 2799.56   384.2 2799.08   428.1 2800.94
   446.5 2800.73   451.2 2799.97     457 2796.67   460.9    2796   471.4 2799.73
   475.3 2800.29   529.2  2800.4   581.7 2802.06   588.5 2804.86   610.9 2822.01
   621.1 2831.48   627.7 2835.56   641.3 2841.68   698.1 2848.31   740.1 2851.56
#Mann= 10 ,-1,0
       0      .1       0   43.64    .045       0  109.06      .1       0
     150     .05       0     330     .06       0     340     .05       0
     460     .07       0     580     .06       0  674.42      .1       0
  704.42     .07       0
#XS Ineff= 2 , 0
                           205.8            2804
Permanent Ineff=
       F       F
Bank Sta=43.64,109.06
XS Rating Curve= 0 ,0
Exp/Cntr=0.3,0.1

Type RM Length L Ch R = 1 ,12505   ,235.7,235.7,235.7
XS GIS Cut Line= 2
2383099.54116134661283.509512353 2383560.2001476661857.821416079
#Sta/Elev= 30
       0 2853.18    20.2 2848.42    41.5 2841.58    61.4 2837.35    78.5 2824.03
    94.4 2803.79   120.1 2788.71   128.9 2786.58     148 2786.27     161  2786.6
  168.19 2788.71   175.2 2791.94     180 2792.39   199.2 2791.36   331.7 2794.21
   371.8 2792.76   402.8 2794.27     438 2794.33   467.7 2793.01   493.9 2794.12
   613.4 2793.19   632.9  2790.1   641.9 2793.33   665.9 2795.19   672.3 2797.07
   697.8 2813.75   710.2 2820.72   725.2 2818.94   730.3  2819.5   736.2  2822.5
#Mann= 9 ,-1,0
       0      .1       0      70     .08       0   120.1    .045       0
  168.19     .08       0     190     .06       0     320     .05       0
     450     .06       0     510     .05       0     670     .06       0
#XS Ineff= 2 , 0
                           550.7            2804
Permanent Ineff=
       F       F
Bank Sta=120.1,168.19
XS Rating Curve= 0 ,0
Exp/Cntr=0.3,0.1

Type RM Length L Ch R = 1 ,12270   ,34.9,34.9,34.9
XS GIS Cut Line= 4
2382952.66113489 661415.852509312383027.42322523661570.508157905
 2383148.8578098661639.8993956762383547.26745444661869.257066358
#Sta/Elev= 30
       0  2844.3    10.4 2840.48    21.6 2839.73    41.5  2834.4    50.3 2833.78
    99.5 2823.24   144.4    2806   152.5 2801.27   170.3 2801.58   186.5 2795.74
   204.9 2792.05  212.75  2786.2   225.5 2783.56   255.6 2783.89   260.2 2786.23
   264.8 2789.73     271 2791.11   320.1 2790.03   375.5 2791.73   421.6 2790.11
   486.2 2792.38   590.4 2791.58   650.9 2792.23   666.2  2793.6   689.3 2792.75
     717 2796.47   725.1 2801.11   739.7 2813.32   760.2 2815.42   771.4 2822.06
#Mann= 8 ,-1,0
       0     .06       0     160     .07       0  212.75    .045       0
   260.2     .07       0  281.78     .05       0  511.64     .07       0
  621.64     .05       0  681.64     .06       0
Bank Sta=212.75,260.2
XS Rating Curve= 0 ,0
Exp/Cntr(USF)=0,0
Exp/Cntr=0.3,0.1

Type RM Length L Ch R = 1 ,12235   ,130,130,130
XS GIS Cut Line= 4
2382911.16211418661442.8825428982382998.20091393661594.030560235
 2383119.6354985661663.4217980072383537.33711505661905.056178091
#Sta/Elev= 30
       0 2844.32     7.3 2841.04    21.1 2839.81      95 2822.53   127.3  2812.8
   137.2 2808.75     155 2796.37   169.4 2795.76   181.3 2791.67   221.1 2790.57
  230.34 2785.68   236.8 2783.66   253.3  2783.3   273.4 2783.64   282.7  2785.7
   291.9 2789.55   347.3 2789.13   370.4  2791.6   429.6 2790.23   488.7 2792.27
   555.2 2792.57   588.2 2791.06   664.3 2791.93     679 2789.84   717.2 2794.57
   733.2 2804.32   749.2 2806.86   755.1 2809.14   773.1 2823.18   796.8 2828.21
#Mann= 8 ,-1,0
       0     .06       0  204.42     .07       0  230.34    .045       0
   282.7     .07       0  314.28     .05       0  544.28     .07       0
  644.28     .05       0  664.28     .06       0
#XS Ineff= 2 , 0
                           570.3            2804
Permanent Ineff=
       F       F
Bank Sta=230.34,282.7
XS Rating Curve= 0 ,0
Exp/Cntr(USF)=0,0
Exp/Cntr=0.3,0.1

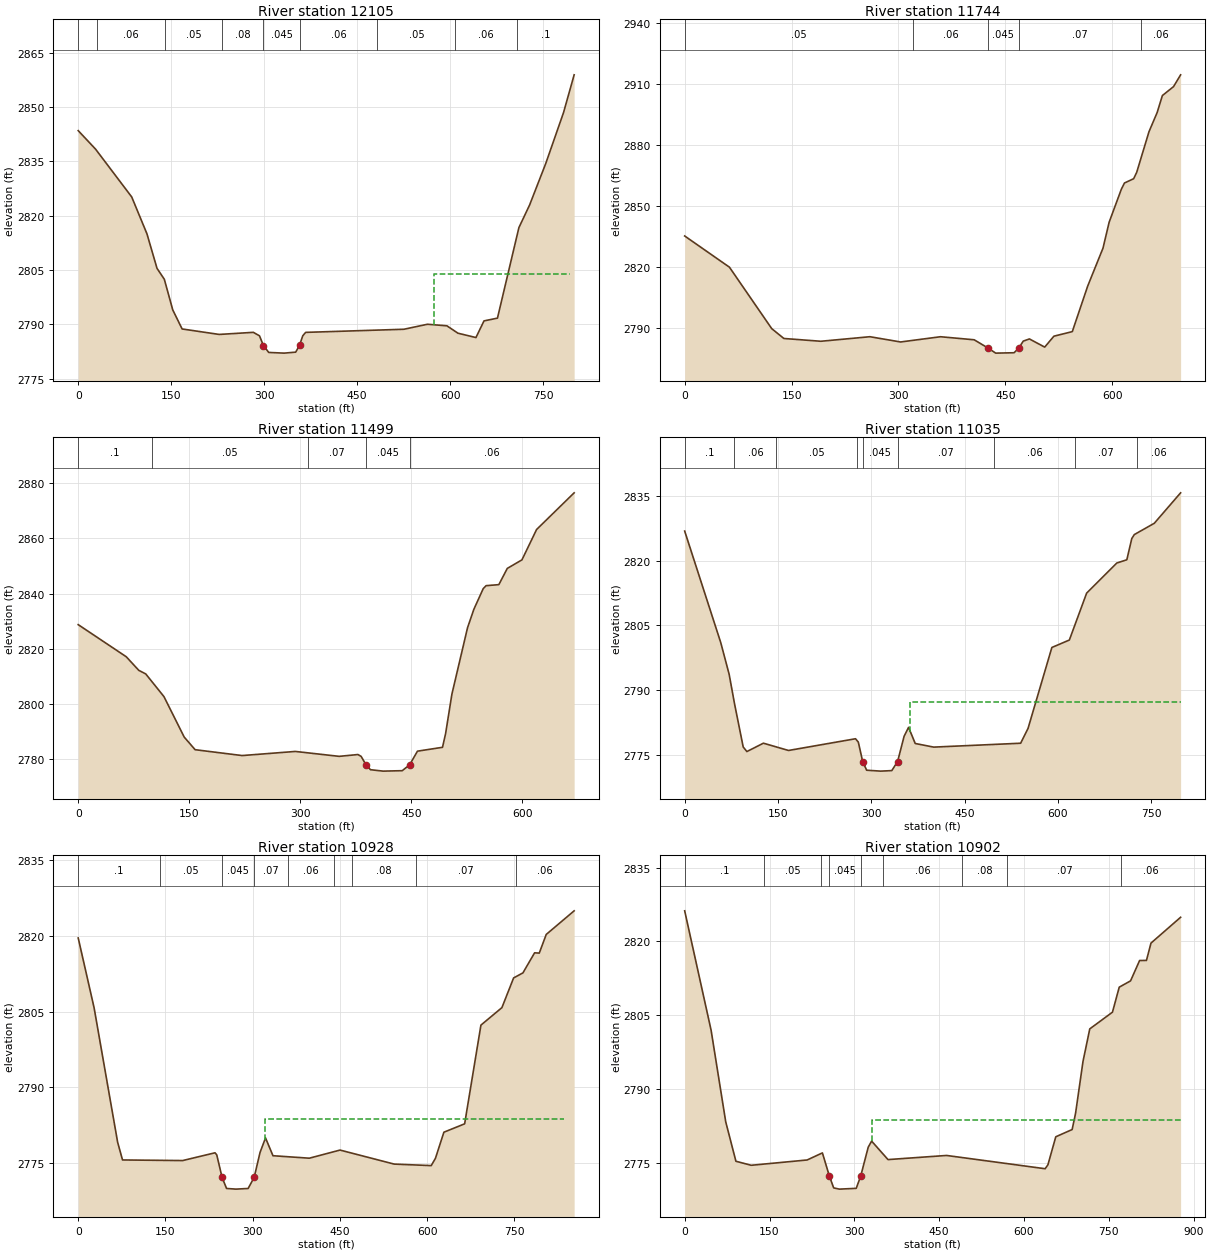
Type RM Length L Ch R = 1 ,12105   ,361.1,361.1,361.1
XS GIS Cut Line= 4
2382780.91286099661510.0622673422382859.38608075661640.850966952
2383178.38604731661874.9649079872383274.74984823662107.522576143
#Sta/Elev= 30
       0 2843.49      28 2838.38    86.3 2825.18   110.9 2814.99   127.1 2805.47
   138.9 2802.45   152.5 2793.99   167.6 2788.73   227.4 2787.22   282.5  2787.8
   292.4 2786.84   298.72784.166   307.3 2782.25   332.1 2782.06   350.8 2782.33
     3572784.229   362.2 2786.86   366.9 2787.79   525.3 2788.65   563.3 2790.03
   594.7  2789.6   612.5 2787.56   641.5 2786.36   654.5 2790.96   676.2 2791.72
   710.8 2816.72   728.1 2822.98   754.1 2834.42   782.8 2848.49   799.9  2858.9
#Mann= 9 ,-1,0
       0      .1       0      30     .06       0     140     .05       0
  232.52     .08       0   298.7    .045       0     357     .06       0
  482.52     .05       0  608.21     .06       0  708.21      .1       0
#XS Ineff= 1 ,-1
   574.3   793.8    2804
Permanent Ineff=
       F
Bank Sta=298.7,357
XS Rating Curve= 0 ,0
Exp/Cntr(USF)=0,0
Exp/Cntr=0.3,0.1

Type RM Length L Ch R = 1 ,11744   ,244.6,244.6,244.6
XS GIS Cut Line= 2
2382649.02453435661631.5617890142382905.64136164 662278.45004116
#Sta/Elev= 30
       0 2835.16    62.8 2819.79   122.2 2789.51   139.2 2784.68   191.1 2783.31
   259.9 2785.55     303 2782.96   358.9 2785.54   406.2 2784.04   425.8 2779.95
   436.4 2777.47   462.2 2777.66  468.67 2779.91   475.1 2783.38   483.7 2784.46
   505.2 2780.44   518.1 2785.81   543.9 2788.06   565.5 2810.47     587 2829.18
   595.6 2841.92   612.8 2858.24   617.1 2861.24     630 2863.35   634.3 2866.51
   651.5 2886.48     663 2895.97   670.3  2904.3     686 2908.71   695.9 2914.51
#Mann= 5 ,-1,0
       0     .05       0     320     .06       0   425.8    .045       0
  468.67     .07       0     640     .06       0
Bank Sta=425.8,468.67
XS Rating Curve= 0 ,0
Exp/Cntr(USF)=0,0
Exp/Cntr=0.3,0.1

Type RM Length L Ch R = 1 ,11499   ,464.2,464.2,464.2
XS GIS Cut Line= 3
2382453.72433762  661731.78041542382640.02291983662275.145859113
2382732.54392134  662298.1920286
#Sta/Elev= 30
       0 2828.77    64.9 2817.14    81.8 2812.22    91.2 2810.92   115.7 2802.74
   143.2 2788.03   157.9 2783.47   221.4 2781.35   293.3 2782.84   352.5 2781.06
   377.8 2781.72   382.1 2781.05  388.762777.972   394.7 2776.23   411.7 2775.71
   437.6 2775.87  447.522777.971   458.2 2782.94     492 2784.34   496.2 2789.33
   504.7  2803.6   525.8 2827.64   534.3 2834.29     547 2841.81   550.9 2842.89
   568.1 2843.26   579.5 2849.14   599.3 2852.24   619.1 2863.24   669.8 2876.52
#Mann= 5 ,-1,0
       0      .1       0     100     .05       0     310     .07       0
  388.76    .045       0  447.52     .06       0
Bank Sta=388.76,447.52
XS Rating Curve= 0 ,0
Exp/Cntr=0.3,0.1

Type RM Length L Ch R = 1 ,11035   ,106.8,106.8,106.8
XS GIS Cut Line= 4
2381979.19415002662021.632315335 2382054.5456642662082.989976881
2382263.37700349662493.1175040532382502.34894846662515.722958306
#Sta/Elev= 30
       0 2826.83      58 2800.96    71.5 2793.62      80 2786.89    94.1 2776.75
     100 2775.69   126.6 2777.63     167 2775.94   274.7 2778.66   279.2 2777.88
  286.192773.383   292.6 2771.36   315.1 2771.15     333 2771.27  342.362773.381
   352.8 2779.23     360  2781.3   370.7 2777.56   400.4 2776.72   540.2 2777.62
   552.1 2781.07   590.4 2799.83   618.5 2801.56   646.3 2812.44   694.8 2819.42
   710.9 2820.17   718.9  2825.1   722.9 2826.01   755.1 2828.64   797.4  2835.7
#Mann= 9 ,-1,0
       0      .1       0      80     .06       0  147.17     .05       0
  277.17     .07       0  286.19    .045       0  342.36     .07       0
  497.17     .06       0  627.41     .07       0  727.41     .06       0
#XS Ineff= 2 , 0
                          362.84         2787.18
Permanent Ineff=
       F       F
Bank Sta=286.19,342.36
XS Rating Curve= 0 ,0
Exp/Cntr(USF)=0,0
Exp/Cntr=0.3,0.1

Type RM Length L Ch R = 1 ,10928   ,25.7,25.7,25.7
XS GIS Cut Line= 4
2381921.75661911662113.5162731632381978.93904046662154.732112785
2382225.95129467662670.3246200012382436.06060477662655.369410306
#Sta/Elev= 30
       0 2819.61    27.3 2805.79    67.8 2779.13    76.2 2775.62   179.6  2775.5
   235.2 2777.04   238.2 2776.64   247.4 2772.16   255.1 2769.97   271.2 2769.84
   292.2 2769.97  302.58 2772.17   312.7 2777.12   322.1 2779.99   334.9 2776.46
   397.4 2775.97   450.2 2777.58   543.3  2774.8     607  2774.5   614.3 2775.95
   628.8 2781.12   664.5 2782.78   692.5 2802.34   728.6 2805.81   748.7 2811.69
   764.7 2812.69   784.8 2816.67   792.8 2816.61   804.8 2820.31   852.8 2824.99
#Mann= 9 ,-1,0
       0      .1       0  140.49     .05       0   247.4    .045       0
  302.58     .07       0  360.49     .06       0  440.49     .07       0
  470.49     .08       0  580.49     .07       0   752.2     .06       0
#XS Ineff= 1 ,-1
  320.58   834.8 2783.83
Permanent Ineff=
       F
Bank Sta=247.4,302.58
XS Rating Curve= 0 ,0
Exp/Cntr(USF)=0,0
Exp/Cntr=0.3,0.1

Type RM Length L Ch R = 1 ,10902   ,131.7,131.7,131.7
XS GIS Cut Line= 4
2381898.11247071662122.0196378042381955.29489207662163.235477426
2382202.30714627662678.8279846422382436.47428393662665.209320922
#Sta/Elev= 30
       0 2826.23    46.7 2801.95    72.6 2783.29    90.6 2775.28   117.6 2774.46
   216.5 2775.54   243.5 2776.98   255.82772.276   263.4 2769.86   273.5 2769.61
   303.3 2769.77   311.2 2772.26   324.5 2778.14   330.5 2779.38   359.5 2775.62
     463 2776.46   637.3 2773.76   642.2 2774.56   656.1 2780.26     685 2781.73
     691 2784.98   704.2 2795.58   716.2 2802.21   756.3 2805.61   768.3  2810.7
   788.3 2811.98   804.3 2816.12   816.4 2816.14   824.4 2819.66   876.8 2824.92
#Mann= 9 ,-1,0
       0      .1       0  140.49     .05       0  240.49     .07       0
   255.8    .045       0   311.2     .07       0  350.49     .06       0
  490.49     .08       0  570.49     .07       0   772.2     .06       0
#XS Ineff= 2 , 0
                          330.69         2783.61
Permanent Ineff=
       F       F
Bank Sta=255.8,311.2
XS Rating Curve= 0 ,0
Exp/Cntr(USF)=0,0
Exp/Cntr=0.3,0.1

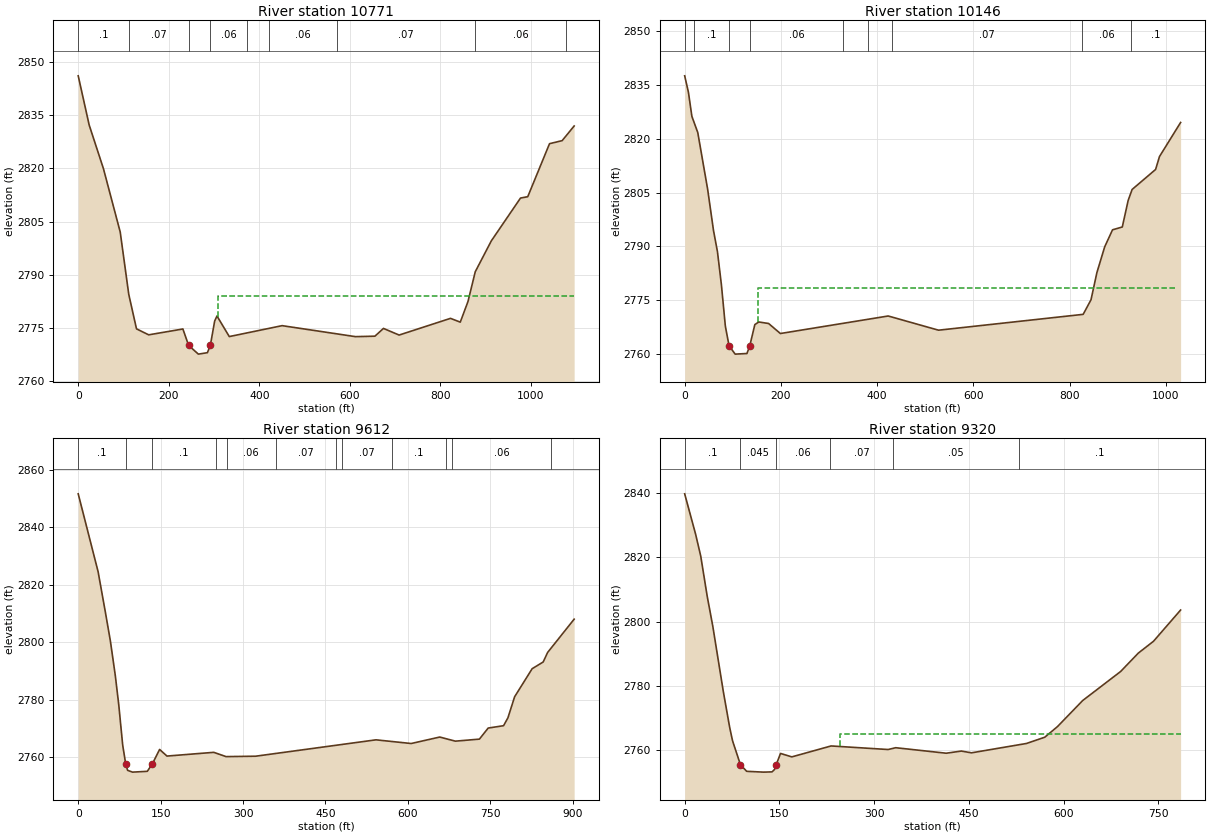
Type RM Length L Ch R = 1 ,10771   ,624.2,624.2,624.2
XS GIS Cut Line= 4
2381750.96071193662262.5463226642381849.01316424662316.757270832
2382305.93643671662892.3589810582382554.65187931662893.243274247
#Sta/Elev= 30
       0  2846.1    24.2 2832.24    55.8 2819.89    92.8 2802.05   111.7 2784.45
   128.8 2774.74   155.7 2773.05   231.3  2774.7  243.932770.063   265.5 2767.61
   285.4 2768.02  291.962770.107   301.5 2776.95   306.6 2778.36   333.8 2772.56
   450.5 2775.64   612.5 2772.54   655.5 2772.67   674.4 2774.86     709 2772.99
   822.5  2777.7   844.1 2776.63   861.2 2782.47   877.2 2790.84   912.6 2799.53
   977.2 2811.63   993.2 2812.01  1041.3 2826.96  1069.2 2827.82  1095.7 2831.95
#Mann= 9 ,-1,0
       0      .1       0  112.04     .07       0  243.93    .045       0
  291.96     .06       0  372.04     .07       0  422.04     .06       0
  572.04     .07       0  876.95     .06       0 1076.95      .1       0
#XS Ineff= 2 , 0
                           308.2         2784.01
Permanent Ineff=
       F       F
Bank Sta=243.93,291.96
XS Rating Curve= 0 ,0
Exp/Cntr=0.3,0.1

Type RM Length L Ch R = 1 ,10146   ,534.5,534.5,534.5
XS GIS Cut Line= 3
2381525.53711651662926.6142063392382285.55675111663087.019863712
2382535.32539097663041.402914511
#Sta/Elev= 30
       0 2837.62     7.8 2833.03      15  2826.3    27.2  2821.8    47.7    2806
    59.9 2794.47    68.1 2788.57    76.3 2779.35    84.5  2767.8    92.2 2762.31
   104.9 2759.96   129.4 2760.13  135.32 2762.28   145.8  2768.2     154 2768.93
   174.4 2768.51   198.9 2765.71     423  2770.6   527.6 2766.64   828.2 2771.06
   844.5 2775.14   856.7 2782.71   872.9  2789.9   889.2 2794.65   909.5 2795.44
   921.7 2802.86   929.9 2805.91   978.7 2811.49   986.8  2815.1  1030.7  2824.6
#Mann= 9 ,-1,0
       0     .05       0      20      .1       0    92.2    .045       0
  135.32     .06       0     330     .07       0     380     .06       0
     430     .07       0  826.76     .06       0  926.76      .1       0
#XS Ineff= 1 ,-1
  153.01  1019.4 2778.28
Permanent Ineff=
       F
Bank Sta=92.2,135.32
XS Rating Curve= 0 ,0
Exp/Cntr=0.3,0.1

Type RM Length L Ch R = 1 ,9612    ,291.4,291.4,291.4
XS GIS Cut Line= 3
2381623.89178701663516.0254969632382070.56951469663290.468501903
2382472.40521031 663312.91440676
#Sta/Elev= 30
       0 2851.67    36.2 2824.58    49.6 2810.32    58.6 2800.42    67.5 2788.44
    73.8  2778.3      81 2764.17    86.42757.741    89.9 2755.43    98.9  2754.8
   125.8 2755.08   135.12757.723   148.2 2762.69   161.6 2760.39   246.8 2761.69
   269.2  2760.2     323 2760.34   542.1 2766.04   606.2 2764.76   658.2 2767.01
   686.6 2765.58   730.4 2766.29   746.4 2770.14   774.4 2770.96   782.4 2773.74
   794.5 2781.02   826.5 2790.81   846.5 2793.13   854.6 2796.45   902.9 2808.04
#Mann= 12 ,-1,0
       0      .1       0    86.4    .045       0   135.1      .1       0
     250     .08       0     270     .06       0     360     .07       0
     470     .08       0     480     .07       0   570.4      .1       0
   670.4     .05       0   680.4     .06       0   860.4      .1       0
Bank Sta=86.4,135.1
XS Rating Curve= 0 ,0
Exp/Cntr=0.3,0.1

Type RM Length L Ch R = 1 ,9320    ,128,128,128
XS GIS Cut Line= 3
2381736.37230324663784.5233922192381959.63604896663672.891519362
 2382495.2032485663656.944108954
#Sta/Elev= 30
       0 2839.72    17.3 2827.18    25.4 2820.39    35.6 2807.95    44.5 2798.59
    61.1 2778.35    71.3 2767.05    75.8 2762.94    88.32755.491    98.2 2753.43
     125 2753.18   138.4 2753.26   142.5 2754.05  144.89 2755.49   151.8 2758.99
   169.7 2757.92   231.9 2761.32   322.2 2760.21   334.2 2760.77   414.2 2759.06
   438.2 2759.73   454.2 2759.18   541.3 2762.09   570.3 2764.04   590.3 2767.32
   630.3 2775.44   690.4 2784.47   718.4 2790.19   742.4 2793.86   785.4 2803.59
#Mann= 6 ,-1,0
       0      .1       0    88.3    .045       0  144.89     .06       0
     230     .07       0  329.62     .05       0  529.62      .1       0
#XS Ineff= 2 , 0
                           245.7            2765
Permanent Ineff=
       F       F
Bank Sta=88.3,144.89
XS Rating Curve= 0 ,0
Exp/Cntr(USF)=0,0
Exp/Cntr=0.3,0.1