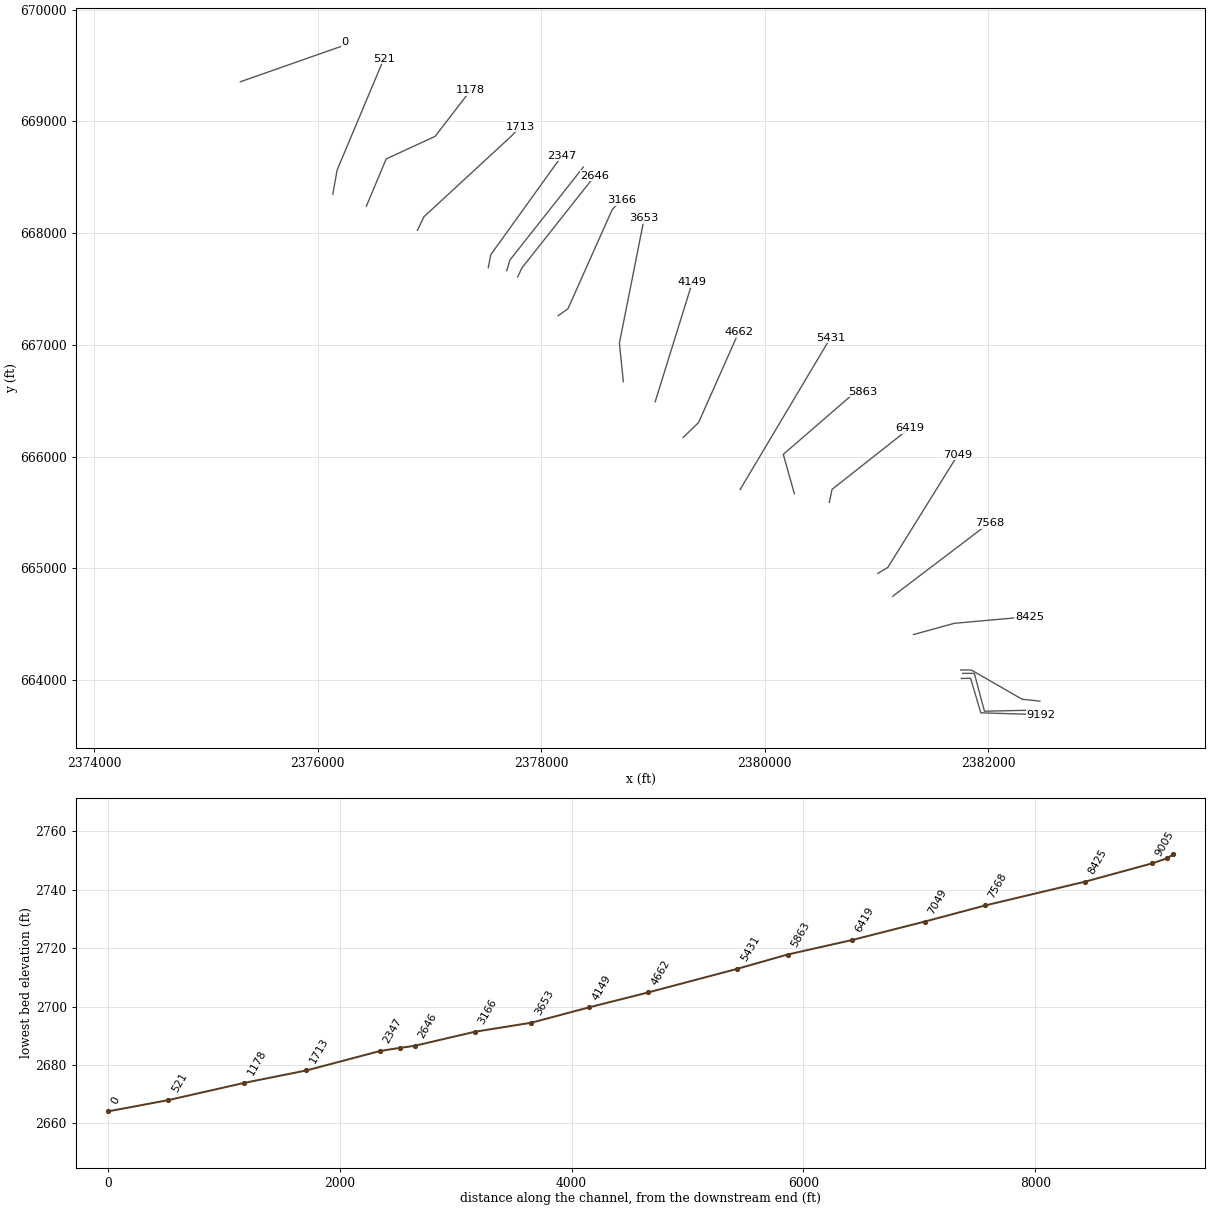
HEC-RAS study GNDYCK_1.prj: GNDYCK_1

--- GNDYCK_1.g01 (geometry) --- (continued)

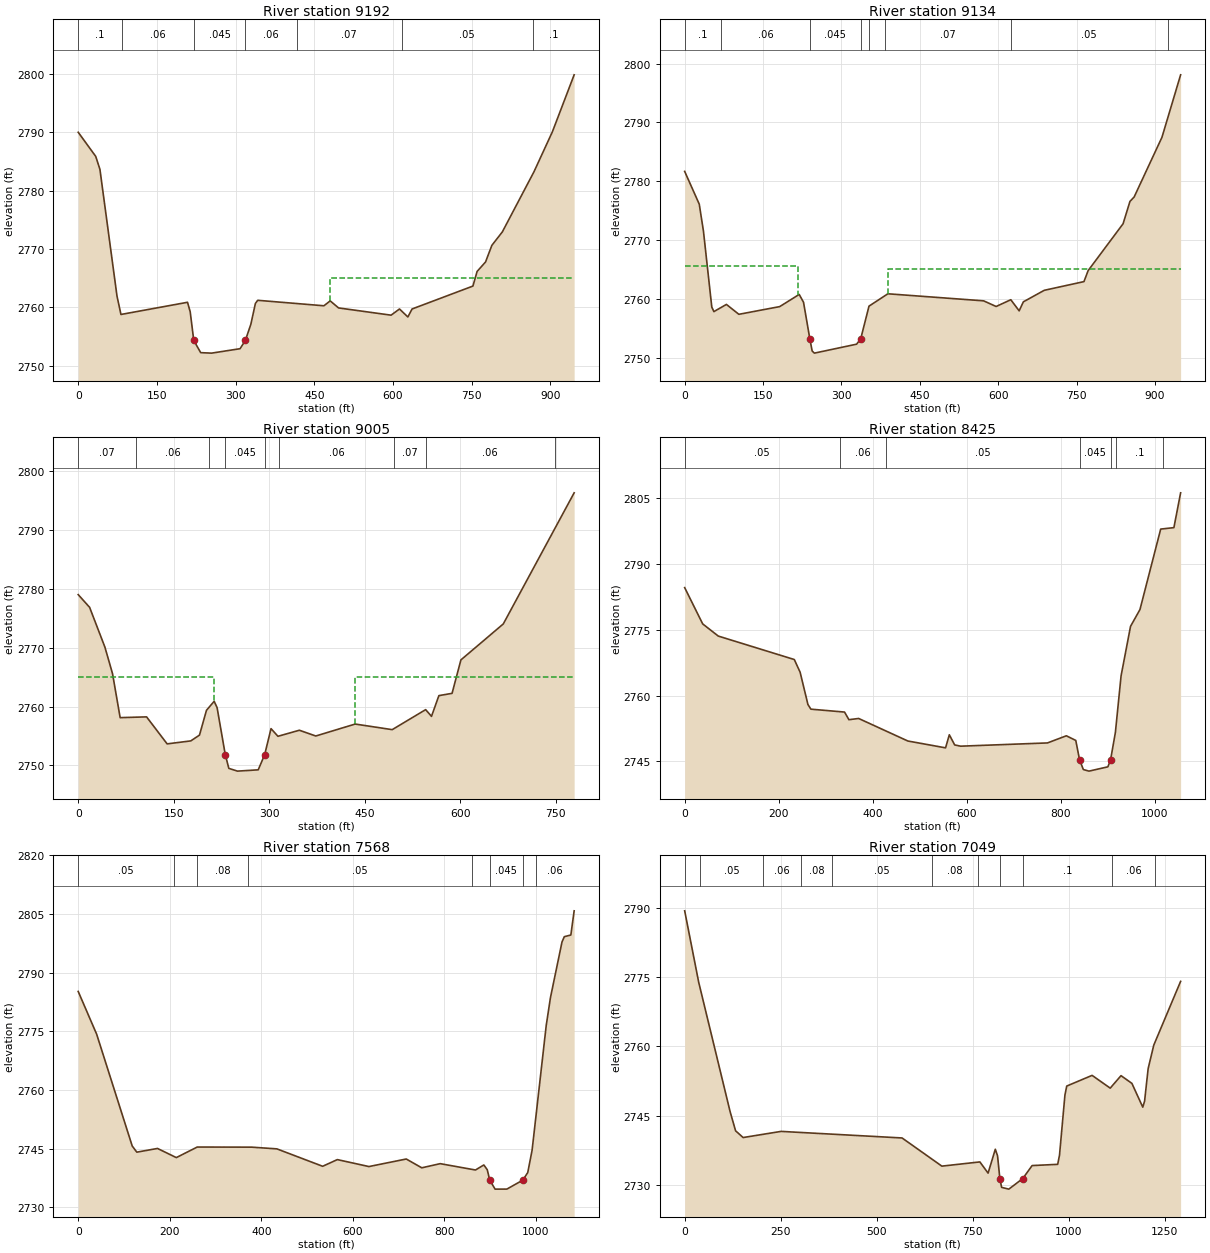
Type RM Length L Ch R = 1 ,9192    ,58.6,58.6,58.6
XS GIS Cut Line= 4
2381758.73599978664014.8856830932381842.35969091664016.819111081
2381934.14350943663707.4366766342382473.03602187663691.391831621
#Sta/Elev= 30
       0 2790.04    33.4  2785.9    41.4 2783.68      74 2761.91    81.5 2758.79
   208.4 2760.88   213.5 2759.25  220.29 2754.34   233.5 2752.24   254.3 2752.16
   308.6 2752.92   318.72754.345   329.1  2757.1   337.8 2760.68   342.2 2761.22
   468.4 2760.28   480.4 2761.12   496.4 2759.91   596.5 2758.67   612.5 2759.73
   628.5 2758.36   636.5 2759.73   752.5 2763.66   760.5 2766.17   776.6  2767.8
   788.6 2770.64   808.6 2772.95   869.1  2783.3   904.1 2790.14   945.5 2799.89
#Mann= 7 ,-1,0
       0      .1       0   83.65     .06       0  220.29    .045       0
   318.7     .06       0  416.36     .07       0  616.36     .05       0
  866.36      .1       0
#XS Ineff= 2 , 0
                          480.14         2765.01
Permanent Ineff=
       F       F
Bank Sta=220.29,318.7
XS Rating Curve= 0 ,0
Exp/Cntr=0.3,0.1

Type RM Length L Ch R = 1 ,9134    ,128.9,128.9,128.9
XS GIS Cut Line= 4
2381772.25042337664060.1944544562381875.92230413664060.791336468
2381966.36957668 663722.004890562382461.15607193663732.690965057
#Sta/Elev= 30
       0 2781.66    27.9 2776.09    35.9 2771.52    51.9 2758.59    55.9 2757.82
    79.9 2759.04   103.7 2757.36   181.9 2758.67   219.2 2760.74   227.5  2759.4
   239.6 2753.16     244 2751.12   248.2 2750.76     329 2752.28  336.82 2753.16
   352.8 2758.75   388.9 2760.85   572.2 2759.65   596.1 2758.69   624.2 2759.84
   640.2 2757.95   648.2 2759.48   688.2 2761.44   764.2 2762.92   772.2 2764.79
   839.1 2772.76   852.2 2776.55   860.2  2777.3   913.5 2787.46   949.2 2798.08
#Mann= 8 ,-1,0
       0      .1       0      70     .06       0   239.6    .045       0
  336.82     .06       0  353.67     .08       0  383.67     .07       0
  624.33     .05       0  924.33      .1       0
#XS Ineff= 2 , 0
          216.61 2765.53  389.17         2765.09
Permanent Ineff=
       F       F
Bank Sta=239.6,336.82
XS Rating Curve= 0 ,0
Exp/Cntr=0.3,0.1

Type RM Length L Ch R = 1 ,9005    ,579.8,579.8,579.8
XS GIS Cut Line= 4
2381754.31265382664091.1236192682381849.99711627664089.927563487
2382303.30225712663829.1874033142382462.82189514663812.094717187
#Sta/Elev= 30
       0 2779.04    17.9 2776.88    41.9 2770.13    53.9 2765.61    65.9 2758.13
   107.4 2758.26   139.7 2753.67   176.9 2754.18   190.5 2755.16   201.5 2759.38
   213.6 2760.91   218.2 2759.82  231.022751.847   236.6 2749.51   250.2 2749.04
   282.8 2749.26  292.892751.829   302.9 2756.26   313.8 2754.96   347.4 2755.99
   373.2 2755.01   435.1 2757.04   493.3 2756.09   545.8 2759.49     555 2758.35
   566.6 2761.87   587.3 2762.26   601.2 2767.94   667.8 2774.06   779.1 2796.34
#Mann= 9 ,-1,0
       0     .07       0      90     .06       0  205.69     .05       0
  231.02    .045       0  292.89     .05       0  315.69     .06       0
  495.69     .07       0  545.69     .06       0  748.64      .1       0
#XS Ineff= 2 , 0
           213.6    2765   434.7            2765
Permanent Ineff=
       F       F
Bank Sta=231.02,292.89
XS Rating Curve= 0 ,0
Exp/Cntr(USF)=0,0
Exp/Cntr=0.3,0.1

Type RM Length L Ch R = 1 ,8425    ,857.4,857.4,857.4
XS GIS Cut Line= 3
2381331.28824061664407.7455378722381696.42954068664508.393674215
2382370.39109015664568.686613701
#Sta/Elev= 30
       0 2784.61    38.3 2776.34    71.5 2773.56   233.3 2768.21   245.7 2765.31
   262.3 2757.95   268.6 2756.89   340.2 2756.23   349.5 2754.49   370.2 2754.77
   474.9 2749.63   555.2 2748.07   563.2 2751.05   574.6 2748.73   587.3 2748.45
   772.1 2749.19   812.2 2750.82   832.3 2749.76   840.3 2745.37   848.4 2743.12
   860.4 2742.76   900.6 2743.74   906.4 2745.35   916.6  2751.6   928.7 2764.49
   948.8 2775.77   968.9 2779.62    1013 2797.96  1041.1 2798.29  1055.4 2806.23
#Mann= 7 ,-1,0
       0     .05       0     330     .06       0  428.76     .05       0
   840.3    .045       0   906.4     .05       0  918.76      .1       0
 1018.76     .06       0
Bank Sta=840.3,906.4
XS Rating Curve= 0 ,0
Exp/Cntr=0.3,0.1

Type RM Length L Ch R = 1 ,7568    ,518.5,518.5,518.5
XS GIS Cut Line= 2
2381146.15075333664750.7737459592382009.39946215665406.087622059
#Sta/Elev= 30
       0 2785.19    40.3 2774.26     118 2745.68   128.1  2744.1   173.3 2745.05
   214.4 2742.71   260.1 2745.41   379.2 2745.38   434.2 2744.94   534.2 2740.49
   566.3  2742.2   635.3 2740.42   716.9 2742.35   750.8  2740.1   791.1 2741.16
   868.2 2739.54   886.4 2740.83   893.9 2739.61  899.382736.949     911 2734.65
   936.8 2734.66  971.642736.949   982.4 2738.89   991.9 2744.59  1022.8 2776.52
    1032  2783.6  1057.2 2797.81  1062.3 2799.19  1076.6 2799.62  1083.8  2805.8
#Mann= 8 ,-1,0
       0     .05       0     210     .06       0     260     .08       0
     370     .05       0     860      .1       0  899.38    .045       0
  971.64      .1       0    1000     .06       0
Bank Sta=899.38,971.64
XS Rating Curve= 0 ,0
Exp/Cntr=0.3,0.1

Type RM Length L Ch R = 1 ,7049    ,630.3,630.3,630.3
XS GIS Cut Line= 3
2381012.77092316664955.8348735442381101.81246033665008.573807574
2381728.78388602 666016.86691324
#Sta/Elev= 30
       0 2789.32    36.5 2773.88   118.3 2745.89   132.5 2741.77   152.1 2740.31
   250.9 2741.64   565.8 2740.22   669.4 2734.13   768.3 2735.04   789.7 2732.62
   808.5 2737.78   814.3 2736.37  820.352731.435   824.9 2729.54   843.7 2729.16
  879.842731.435   904.3 2734.25   970.9 2734.52   975.6 2736.51   989.7  2749.5
   994.4 2751.44  1060.4 2753.75  1107.6 2750.99  1135.7 2753.69    1164 2752.02
  1192.3 2746.88    1197 2748.17  1206.3 2755.21  1220.9 2760.28  1290.8 2774.07
#Mann= 11 ,-1,0
       0      .1       0      40     .05       0  203.49     .06       0
  303.49     .08       0  383.49     .05       0  643.49     .08       0
  763.49      .1       0  820.35    .045       0  879.84      .1       0
 1113.49     .06       0 1223.49      .1       0
Bank Sta=820.35,879.84
XS Rating Curve= 0 ,0
Exp/Cntr=0.3,0.1

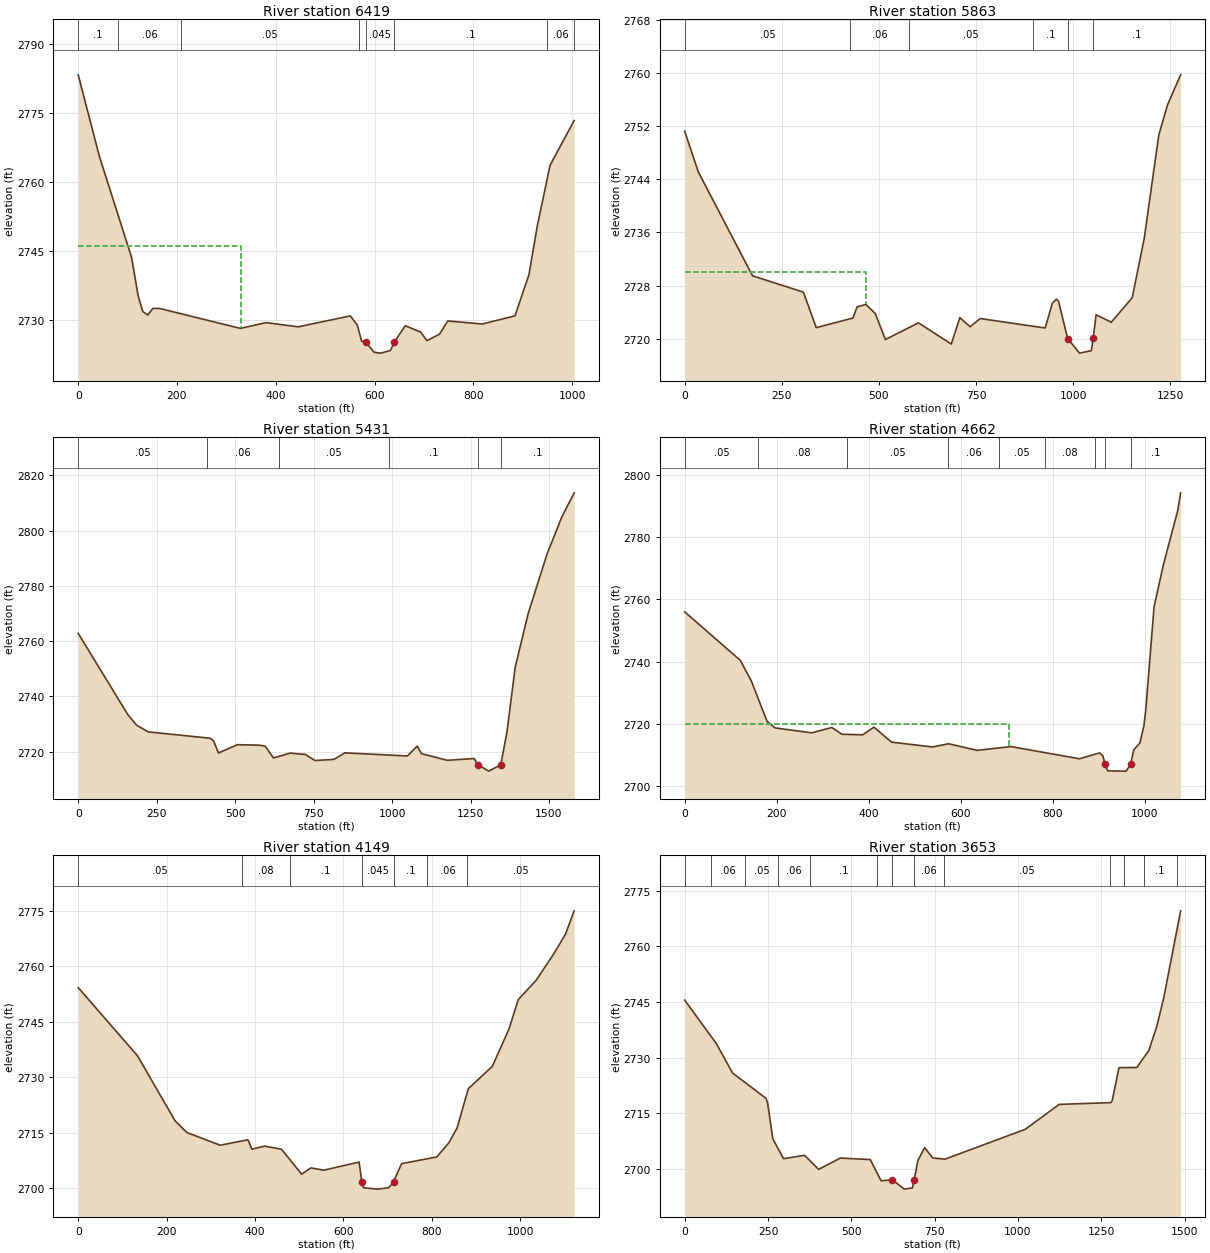
Type RM Length L Ch R = 1 ,6419    ,555.9,555.9,555.9
XS GIS Cut Line= 3
2380577.95273235665591.3901275852380602.52550553665707.310017292
2381298.23751177666255.554301105
#Sta/Elev= 30
       0 2783.33    42.7 2765.65   108.1 2743.62   121.5 2735.18   130.8 2731.83
   140.9 2731.09   151.2 2732.52   165.2 2732.51   328.3 2728.18   380.2 2729.44
   445.7 2728.52   551.1  2730.9   565.3 2728.87   573.9  2725.4   582.4 2725.21
   599.3 2722.97   612.7  2722.8   632.1 2723.36   640.1 2725.19   662.2 2728.76
   693.5 2727.38   706.3 2725.51   731.7 2726.93   748.4  2729.8   818.3 2729.13
   884.5 2730.91   912.8 2739.85   929.3 2750.26   955.5 2763.65  1004.3 2773.39
#Mann= 8 ,-1,0
       0      .1       0      80     .06       0   208.5     .05       0
   568.5      .1       0   582.4    .045       0   640.1      .1       0
   948.5     .06       0 1004.26      .1       0
#XS Ineff= 2 , 0
          330.05 2746.04
Permanent Ineff=
       F       F
Bank Sta=582.4,640.1
XS Rating Curve= 0 ,0
Exp/Cntr=0.3,0.1

Type RM Length L Ch R = 1 ,5863    ,431.9,431.9,431.9
XS GIS Cut Line= 4
2380265.43144485665667.2739639892380165.91710774666019.968696339
2380776.72724343666548.9776045792380873.67956875666579.237769491
#Sta/Elev= 30
       0 2751.24    35.2  2745.1   174.6 2729.48   305.4 2727.02   338.6 2721.68
     433 2723.12   443.5 2724.79   466.1 2725.17   490.5  2723.8   516.4 2719.88
   601.5  2722.4     686 2719.21   708.1 2723.18   734.6 2721.81   760.3 2723.05
   927.6 2721.62   946.2 2725.37   956.8 2725.96   962.1 2725.62   985.4 2720.04
    1016 2717.84  1046.5 2718.21 1051.172720.079  1058.7 2723.61  1097.7 2722.49
  1151.6 2726.18  1182.3 2735.05    1220 2750.68  1242.3 2755.19  1276.1 2759.73
#Mann= 6 ,-1,0
       0     .05       0  426.47     .06       0  576.47     .05       0
  896.47      .1       0   985.4    .045       0 1051.17      .1       0
#XS Ineff= 2 , 0
           466.1    2730
Permanent Ineff=
       F       F
Bank Sta=985.4,1051.17
XS Rating Curve= 0 ,0
Exp/Cntr=0.3,0.1

Type RM Length L Ch R = 1 ,5431    ,769,769,769
XS GIS Cut Line= 2
 2379779.5159524665705.1698567142380588.05480465667062.845069854
#Sta/Elev= 30
       0 2762.82   157.6 2733.49   186.2 2729.55   223.5 2727.16   420.7 2724.86
   431.3 2723.92   446.9 2719.53   507.5 2722.53   575.3 2722.36   595.9 2722.02
     622 2717.73   675.1 2719.47   724.1 2718.99   754.2  2716.8   814.6 2717.19
   849.6 2719.57  1048.8 2718.45  1080.1    2722  1094.1 2719.27  1176.4 2716.87
  1261.7 2717.51 1272.79  2715.3  1308.2 2712.96 1346.49 2715.27  1366.1  2727.1
  1392.3 2750.48  1433.9 2770.06  1494.4 2791.68  1541.1 2804.97  1580.2 2813.67
#Mann= 6 ,-1,0
       0     .05       0     410     .06       0     640     .05       0
     990      .1       0 1272.79    .045       0 1346.49      .1       0
Bank Sta=1272.79,1346.49
XS Rating Curve= 0 ,0
Exp/Cntr(USF)=0,0
Exp/Cntr=0.3,0.1

Type RM Length L Ch R = 1 ,4662    ,513.4,513.4,513.4
XS GIS Cut Line= 3
2379269.06403674666171.1516854532379407.92064752666305.019940058
2379767.33607468667114.065183611
#Sta/Elev= 30
       0 2755.97     121  2740.4   145.1 2733.74     179 2720.87   196.2 2718.74
   276.2 2717.15     320 2718.88   341.9 2716.69   387.2 2716.52   411.4 2718.98
   449.7 2714.17   538.7 2712.62   573.8 2713.65   635.7 2711.53   709.5 2712.74
   858.3 2708.83   902.1 2710.72   909.4 2709.72  913.672707.113   919.6 2704.95
   959.9 2704.87  969.422707.117   976.5 2711.75   989.7 2713.93   998.4 2719.43
  1002.4 2724.44  1020.5 2757.62  1040.8 2771.09  1072.1 2788.56  1078.2 2794.14
#Mann= 9 ,-1,0
       0     .05       0     160     .08       0  352.88     .05       0
  572.88     .06       0  682.88     .05       0  782.88     .08       0
  892.88      .1       0  913.67    .045       0  969.42      .1       0
#XS Ineff= 2 , 0
           705.2    2720
Permanent Ineff=
       F       F
Bank Sta=913.67,969.42
XS Rating Curve= 0 ,0
Exp/Cntr=0.3,0.1

Type RM Length L Ch R = 1 ,4149    ,495.9,495.9,495.9
XS GIS Cut Line= 2
2379019.14010361666490.5289712732379352.22741816667561.809793736
#Sta/Elev= 30
       0 2754.19     134 2735.78     219 2718.21   245.7 2715.03   321.1 2711.59
     384 2713.06   392.8 2710.52   421.7 2711.34   459.9  2710.5   505.4 2703.77
   526.4 2705.46   555.7 2704.84   635.3 2707.03  641.512701.776   645.2  2700.1
   677.2 2699.72   702.7  2700.1  713.472701.781   731.6 2706.62   811.2 2708.41
   838.8  2712.3   857.3 2716.28   882.4 2726.85   936.9 2732.93   974.6 2743.02
   995.5 2750.95  1035.9 2756.16  1075.1 2763.18  1102.2 2768.61  1121.9 2774.94
#Mann= 7 ,-1,0
       0     .05       0     370     .08       0     480      .1       0
  641.51    .045       0  713.47      .1       0     790     .06       0
     880     .05       0
Bank Sta=641.51,713.47
XS Rating Curve= 0 ,0
Exp/Cntr(USF)=0,0
Exp/Cntr=0.3,0.1

Type RM Length L Ch R = 1 ,3653    ,487.1,487.1,487.1
XS GIS Cut Line= 3
2378734.42324478666670.2509232662378698.90365775667015.209009384
2378921.30695791 668134.51742166
#Sta/Elev= 30
       0  2745.5    95.4 2733.71   143.7 2725.83   244.2 2718.97     249 2717.68
   264.3 2708.08   296.6  2702.7   359.7 2703.61   401.8 2699.81   467.1 2702.86
   556.8 2702.46   589.4 2696.73   623.52696.975   659.1 2694.48   683.2 2694.81
   688.82697.026   699.5 2702.17   719.9 2705.69   744.2 2702.89   781.1 2702.57
  1021.7 2710.62  1123.6 2717.35  1278.6 2717.83  1282.7 2718.33  1303.1 2727.27
  1356.6 2727.32  1392.8 2731.91  1417.3 2738.65  1437.7 2746.25    1488  2769.6
#Mann= 13 ,-1,0
       0     .05       0      80     .06       0     180     .05       0
     280     .06       0  376.78      .1       0  576.78     .07       0
   623.5    .045       0   688.8     .06       0  776.78     .05       0
 1276.78      .1       0 1316.78     .06       0 1376.78      .1       0
 1476.78     .05       0
Bank Sta=623.5,688.8
XS Rating Curve= 0 ,0
Exp/Cntr(USF)=0,0
Exp/Cntr=0.3,0.1

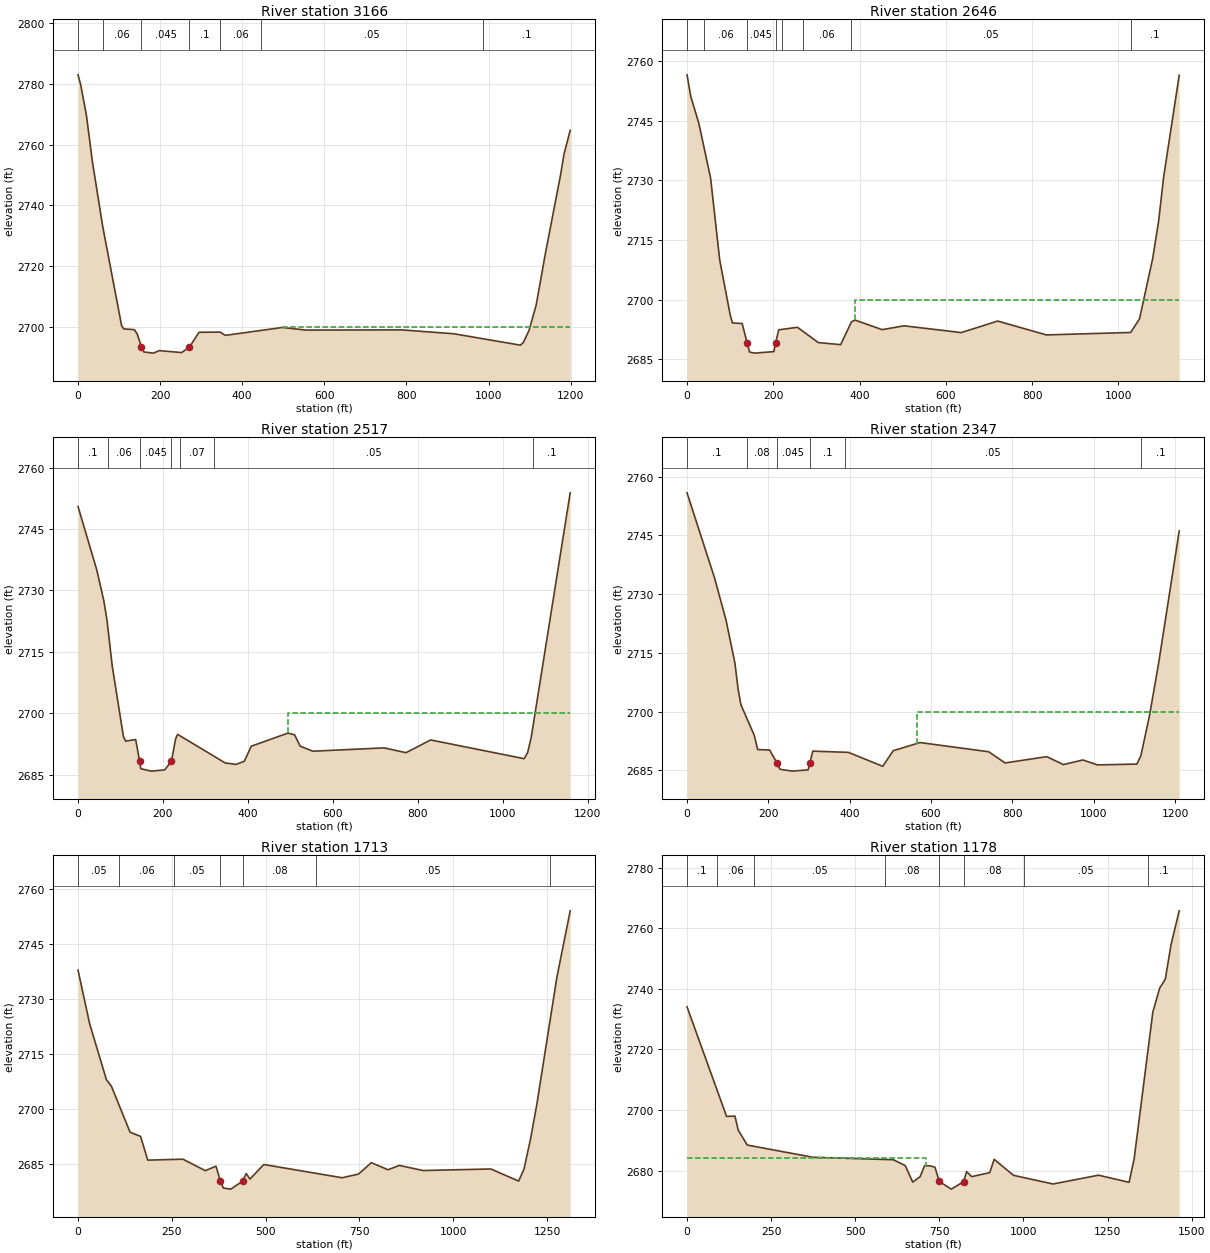
Type RM Length L Ch R = 1 ,3166    ,520.2,520.2,520.2
XS GIS Cut Line= 4
2378150.99753122667261.513574952 2378238.0953628667322.279503957
 2378635.0994323  668211.48759842378718.14620194668296.559899007
#Sta/Elev= 30
       0 2782.97     6.4 2779.77    20.4  2769.7    35.1 2754.33      60 2733.18
   106.2  2700.4   111.3 2699.35   137.2 2699.11   144.4 2697.62  154.492693.466
   160.4 2691.76   183.8 2691.38   197.8 2692.21   252.3 2691.56   271.5 2693.37
   294.7 2698.24   346.2  2698.3   359.1 2697.23   497.6 2699.82   556.2 2698.96
   788.4 2699.03     915 2697.76  1077.5 2694.01  1084.8 2694.88  1098.7 2698.88
  1115.9 2707.12  1138.5 2724.19  1175.3 2749.92  1183.8 2756.83  1198.9  2764.7
#Mann= 7 ,-1,0
       0      .1       0      60     .06       0  154.49    .045       0
   271.5      .1       0   346.2     .06       0   446.2     .05       0
   986.2      .1       0
#XS Ineff= 1 ,-1
   497.61198.896    2700
Permanent Ineff=
       F
Bank Sta=154.49,271.5
XS Rating Curve= 0 ,0
Exp/Cntr(USF)=0,0
Exp/Cntr=0.3,0.1

Type RM Length L Ch R = 1 ,2646    ,128.5,128.5,128.5
XS GIS Cut Line= 3
2377788.42748816667607.8793702812377826.91257653667688.900608955
2378479.13354785668513.291712459
#Sta/Elev= 30
       0 2756.59     8.7 2751.14    27.4 2744.37    54.6 2730.63    75.8 2709.94
   100.3 2696.04   105.4 2694.15   127.8 2694.01  139.62 2689.01   144.9 2686.84
   156.3 2686.56   201.3 2686.94  205.132689.043   212.5 2692.42     256 2693.06
   304.3 2689.22   356.1 2688.69   381.2 2694.45   389.8 2694.87   452.2 2692.47
   503.2 2693.43   635.8 2691.73   720.1 2694.63   833.1 2691.14  1028.5 2691.76
  1048.9 2695.19  1079.5  2710.4  1093.1 2719.69    1105 2731.01  1140.9 2756.48
#Mann= 8 ,-1,0
       0      .1       0      40     .06       0  139.62    .045       0
  205.13     .06       0   219.7     .07       0   269.7     .06       0
   379.7     .05       0  1029.7      .1       0
#XS Ineff= 1 ,-1
   389.81140.893    2700
Permanent Ineff=
       F
Bank Sta=139.62,205.13
XS Rating Curve= 0 ,0
Exp/Cntr(USF)=0,0
Exp/Cntr=0.3,0.1

Type RM Length L Ch R = 1 ,2517    ,170.4,170.4,170.4
XS GIS Cut Line= 3
2377690.66335838667663.9034644512377719.55943529667759.794192794
2378375.83146854668590.261889199
#Sta/Elev= 30
       0 2750.53      44 2735.07    60.7 2727.54    68.2 2722.73    80.7 2711.42
     107 2694.22   112.1 2693.18   135.7 2693.57  145.142688.235   147.8 2686.43
   172.8 2685.85   203.9 2686.15  219.792688.237   229.7 2693.73   234.5 2694.83
   346.6 2687.84   372.2  2687.5   391.5 2688.26   407.8 2691.94   494.5 2695.15
   509.8 2694.72     523 2691.95   552.7 2690.72   720.5 2691.53   772.1 2690.36
   830.2 2693.47  1050.2 2688.89  1058.4 2690.36    1067 2694.17  1158.6 2753.87
#Mann= 7 ,-1,0
       0      .1       0      70     .06       0  145.14    .045       0
  219.79     .06       0  240.15     .07       0  320.15     .05       0
 1070.15      .1       0
#XS Ineff= 2 , 0
                           494.5            2700
Permanent Ineff=
       F       F
Bank Sta=145.14,219.79
XS Rating Curve= 0 ,0
Exp/Cntr(USF)=0,0
Exp/Cntr=0.3,0.1

Type RM Length L Ch R = 1 ,2347    ,633.6,633.6,633.6
XS GIS Cut Line= 3
2377525.10846247667690.926139922 2377547.3893031667806.381405032
2378185.43155766668693.563968508
#Sta/Elev= 30
       0 2755.87    67.5 2734.19      96  2723.3   117.6 2712.47   125.9 2705.54
   132.6 2701.71   165.4 2693.91   173.7 2690.29   203.3 2690.16  221.232686.837
   228.5 2685.26     259 2684.78   297.8  2685.1   302.12686.871   309.3 2689.89
   396.9 2689.57   481.3 2686.01   507.1    2690     573 2692.08   741.8 2689.73
   782.2 2686.87   884.7 2688.48   925.5 2686.45   973.4 2687.63  1009.5 2686.37
  1106.4 2686.58  1116.3 2688.75  1137.6 2699.11  1160.3 2712.66  1210.4 2746.12
#Mann= 6 ,-1,0
       0      .1       0  147.59     .08       0  221.23    .045       0
   302.1      .1       0  387.59     .05       0 1117.59      .1       0
#XS Ineff= 2 , 0
                           564.4            2700
Permanent Ineff=
       F       F
Bank Sta=221.23,302.1
XS Rating Curve= 0 ,0
Exp/Cntr(USF)=0,0
Exp/Cntr=0.3,0.1

Type RM Length L Ch R = 1 ,1713    ,535.1,535.1,535.1
XS GIS Cut Line= 4
2376891.11726985668025.1387494512376949.85766789668146.670607461
2377731.71262109668867.7596316562377808.68279783668950.806401297
#Sta/Elev= 30
       0 2737.82    31.1 2723.15    75.7 2707.95    88.9  2706.2   138.7 2693.64
   166.7 2692.51   185.9 2686.03   279.6 2686.29   339.3 2683.16   367.7 2684.38
  379.432680.355   387.5 2678.42   407.3 2678.13   438.5 2680.28   448.3 2682.38
   458.3 2680.87   495.1 2684.84     704 2681.23   747.6 2682.23   781.8 2685.34
   826.3 2683.41   856.4 2684.59   919.7  2683.2  1100.4 2683.62  1174.4 2680.32
  1188.6 2683.56    1206 2691.75  1222.6 2701.06  1276.3 2735.83  1311.8 2753.97
#Mann= 7 ,-1,0
       0     .05       0     110     .06       0  254.98     .05       0
  379.43    .045       0   438.5     .08       0  634.98     .05       0
 1258.59      .1       0
Bank Sta=379.43,438.5
XS Rating Curve= 0 ,0
Exp/Cntr(USF)=0,0
Exp/Cntr=0.3,0.1

Type RM Length L Ch R = 1 ,1178    ,657.2,657.2,657.2
XS GIS Cut Line= 4
2376433.88694324668240.8675564272376611.68355032  668663.9784695
2377049.43560596668865.3935885562377368.00766048669279.259319167
#Sta/Elev= 30
       0 2734.05   117.5  2697.9   142.5 2697.98   152.2 2693.33   179.2 2688.43
   373.5 2684.41   613.6 2683.58   648.8 2681.64   670.8  2676.2   692.9 2677.98
   706.1  2681.6   723.7 2681.56   736.9 2681.12   749.92676.421   785.3 2673.88
   821.92676.311   831.1 2679.67   846.2    2678   899.8 2679.32     913 2683.71
   970.8 2678.42  1088.1 2675.58  1223.2 2678.48  1314.1 2676.13  1329.2 2683.92
  1384.7  2732.3  1404.9 2740.19  1421.8 2743.23  1438.9 2754.62  1463.1 2765.76
#Mann= 8 ,-1,0
       0      .1       0      90     .06       0     200     .05       0
  588.95     .08       0   749.9    .045       0   821.9     .08       0
 1000.82     .05       0 1370.82      .1       0
#XS Ineff= 2 , 0
             711    2684
Permanent Ineff=
       F       F
Bank Sta=749.9,821.9
XS Rating Curve= 0 ,0
Exp/Cntr(USF)=0,0
Exp/Cntr=0.3,0.1

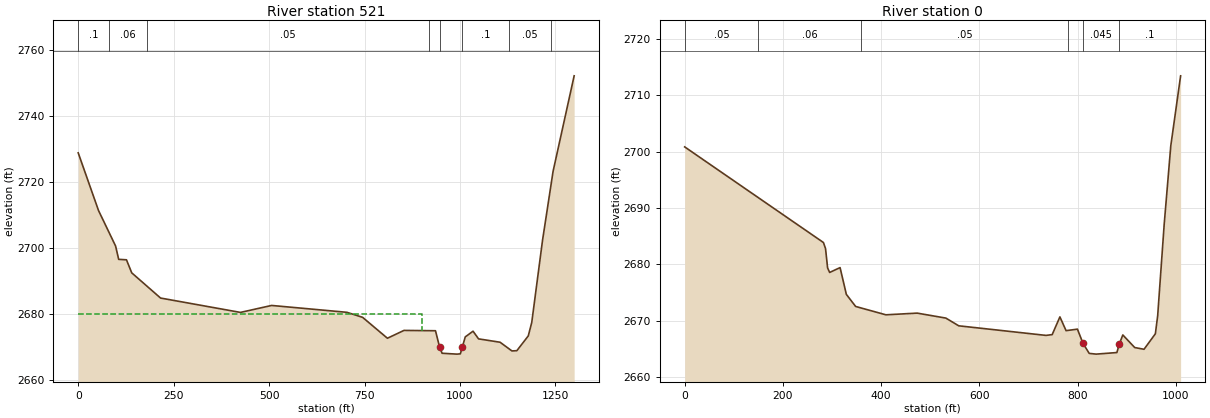
Type RM Length L Ch R = 1 ,521     ,520.9,520.9,520.9
XS GIS Cut Line= 3
2376133.83328401668348.8039762782376172.38162627668564.478962627
2376590.80408811669560.070434499
#Sta/Elev= 30
       0 2728.91    53.2 2711.44    97.9  2700.7     106 2696.66   126.4 2696.52
   140.2 2692.57   215.7 2684.94     425 2680.59   506.6  2682.7   703.8 2680.62
   744.9  2679.1   809.9 2672.77   853.3 2675.14   935.8 2675.04  946.612670.064
   953.1 2668.22   992.2 2667.96  1000.9 2668.05 1006.182670.106  1013.8 2673.18
  1034.2  2674.9  1048.6 2672.58    1105 2671.56    1136 2668.93  1148.9    2669
  1178.8 2673.47  1187.9 2677.51  1216.2 2702.44  1243.8 2723.31    1299 2752.23
#Mann= 8 ,-1,0
       0      .1       0      80     .06       0     180     .05       0
  919.09      .1       0  946.61    .045       0 1006.18      .1       0
 1129.09     .05       0 1239.09      .1       0
#XS Ineff= 2 , 0
           900.7    2680
Permanent Ineff=
       F       F
Bank Sta=946.61,1006.18
XS Rating Curve= 0 ,0
Exp/Cntr(USF)=0,0
Exp/Cntr=0.3,0.1

Type RM Length L Ch R = 1 ,0       ,628.6,628.6,628.6
XS GIS Cut Line= 3
2375305.56187368669354.0030577182376208.27295452669670.525066078
2376240.35122262669712.972548781
#Sta/Elev= 30
       0 2700.83   282.5 2683.88   286.8 2682.81     291 2679.38   295.2 2678.57
   316.4 2679.43   329.2 2674.68   348.1 2672.54   409.7 2671.06   473.3 2671.36
   531.8 2670.48     558 2669.11   735.8 2667.41   748.3 2667.55     764 2670.69
   776.6 2668.25   799.7 2668.52   811.1 2665.99   823.7 2664.22   837.8 2664.09
     880 2664.37   885.1 2665.91   892.1 2667.49   916.3 2665.26   935.3 2664.95
   958.4  2667.7   963.1  2670.9   976.3 2687.04   989.8 2701.03  1009.8 2713.43
#Mann= 6 ,-1,0
       0     .05       0     150     .06       0     360     .05       0
     780      .1       0   811.1    .045       0   885.1      .1       0
Bank Sta=811.1,885.1
XS Rating Curve= 0 ,0
Exp/Cntr=0.3,0.1
LCMann Table=0

Chan Stop Cuts=-1
Use User Specified Reach Order=0
Composite Channel Slope=5